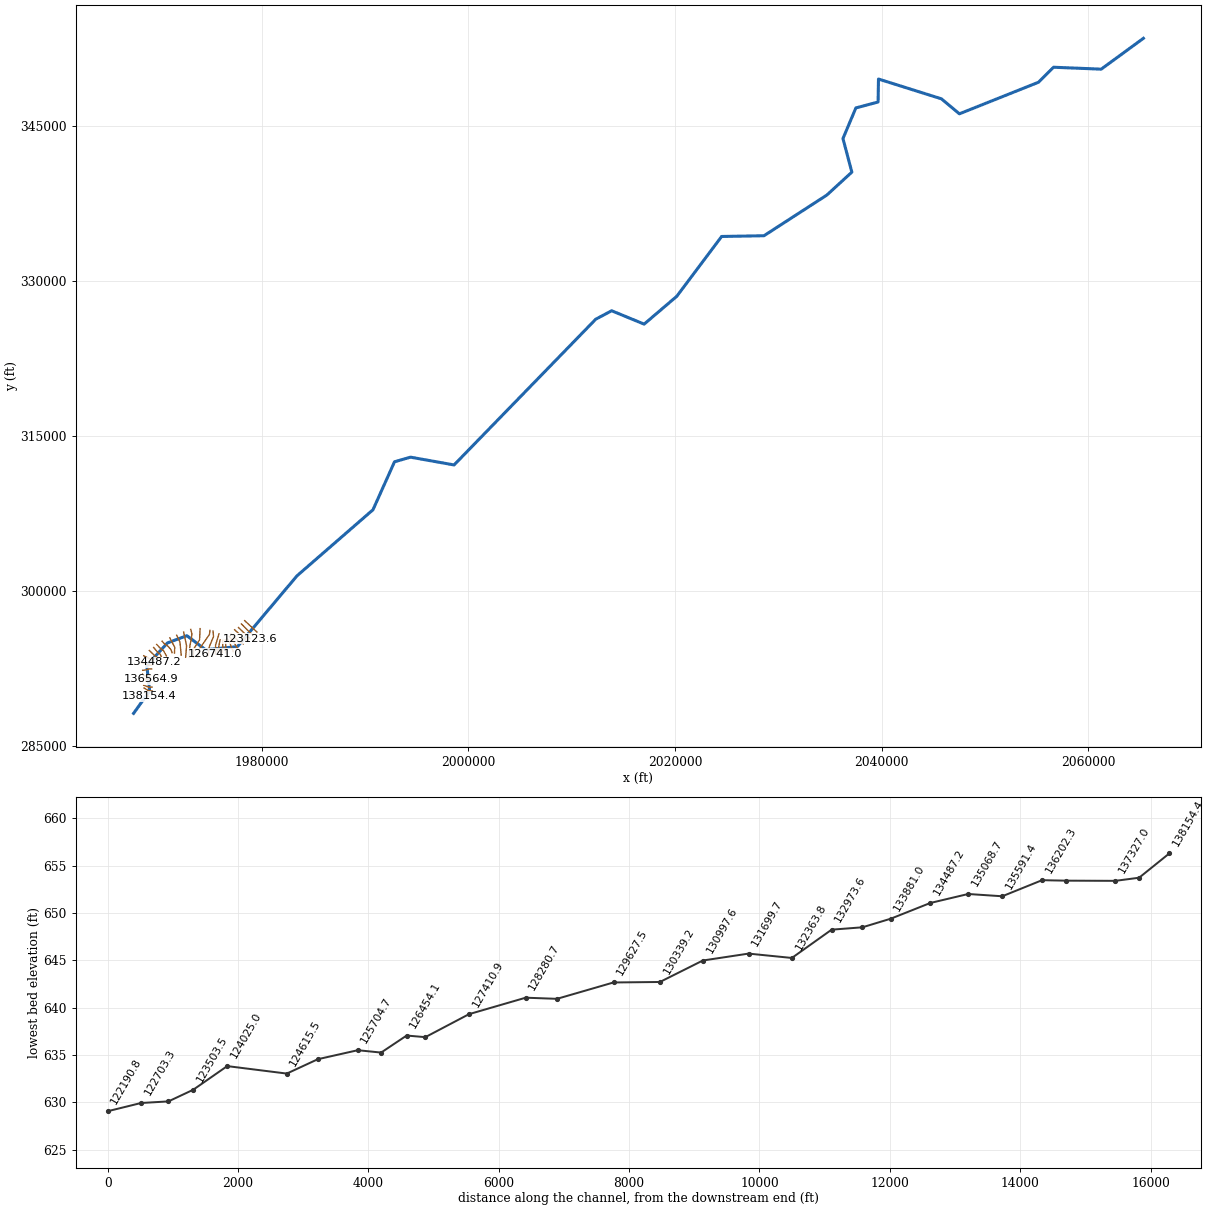
HEC-RAS study BaldEagle.prj: Bald Eagle Cr. for the WCDS Project

--- BaldEagle.f02 (steady flow) ---

Flow Title=Steady Flow Data
Version=Version 3.0.0  Dec 2000
Number of Profiles= 8
Profile Names=.5 year,1 year,2 year,5 year,10 year,25 year,50 year,100 year
River Rch & RM=Bald Eagle,Loc Hav         ,138154.4
    2000    3000    5000   10000   15000   20000   25000   30000
Boundary for River Rch & Prof#=Bald Eagle,Loc Hav         , 1
Up Type= 0
Dn Type= 4
Dn Rating Curve # Pts= 7
       0   529.2    1000     535    3000     540   16500   557.3   27000   562.1
   32500   564.1   47000   568.6
Boundary for River Rch & Prof#=Bald Eagle,Loc Hav         , 2
Up Type= 0
Dn Type= 0
Boundary for River Rch & Prof#=Bald Eagle,Loc Hav         , 3
Up Type= 0
Dn Type= 0
Boundary for River Rch & Prof#=Bald Eagle,Loc Hav         , 4
Up Type= 0
Dn Type= 0
Boundary for River Rch & Prof#=Bald Eagle,Loc Hav         , 5
Up Type= 0
Dn Type= 0
Boundary for River Rch & Prof#=Bald Eagle,Loc Hav         , 6
Up Type= 0
Dn Type= 0
Boundary for River Rch & Prof#=Bald Eagle,Loc Hav         , 7
Up Type= 0
Dn Type= 0
Boundary for River Rch & Prof#=Bald Eagle,Loc Hav         , 8
Up Type= 0
Dn Type= 0
Gate Openings=Bald Eagle      ,Loc Hav         ,81500   ,Gate #1     ,
      10       1      10       1      10       1      10       1      10       1
      10       1      10       1      10       1
DSS Import GetInterval= 0
DSS Import GetPeak= 0
DSS Import FillOption= 0

--- BaldEagle.u02 (unsteady flow) ---

Flow Title=Flow Hydrograph 2
Program Version=6.30
Use Restart= 0
Initial Flow Loc=Bald Eagle      ,Loc Hav         ,138154.4,2000
Boundary Location=Bald Eagle      ,Loc Hav         ,138154.4,        ,                ,                ,                ,                                ,
Interval=1HOUR
Flow Hydrograph= 150
 1075.53 1301.64 1676.94 2199.12 2864.95 3670.34 4610.32 5679.08 6870.05 8175.88
 9588.5211099.2612698.7914377.2316124.2617929.0819780.5921667.3623577.75   25500
27422.2529332.6431219.4133070.9234875.7436622.7738301.2139900.7441411.4842824.12
44129.9545320.9246389.6847329.6648135.0548800.8849323.0649698.3649924.48   50000
49924.4849698.3649323.0648800.8848135.0547329.6646389.6845320.9244129.9542824.12
41411.4839900.7438301.2136622.7734875.7433070.9231219.4129332.6427422.2526133.62
24907.8423741.8422632.7121577.6720574.0819619.4518711.3617847.57 17025.916244.31
15500.8414793.62 14120.913480.9912872.2812293.2611742.4911218.57 10720.210246.14
  9795.2 9366.26 8958.23  8570.1  8200.9 7849.71 7515.65 7197.88  6895.6 6608.07
 6334.56 6074.39 5826.91  5591.5 5367.57 5154.56 4951.94  4759.2 4575.86 4401.47
 4235.58 4077.77 3927.67 3784.89 3649.07 3519.87 3396.97 3280.07 3168.87 3063.09
 2962.48 2866.76 2775.72 2689.12 2606.74 2528.38 2453.84 2382.93 2315.49 2251.33
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Stage Hydrograph TW Check=0
Use DSS=False
Use Fixed Start Time=False
Is Critical Boundary=False
Boundary Location=Bald Eagle      ,Loc Hav         ,81500   ,        ,                ,                ,                ,                                ,
Gate Name=Gate #1
Gate Use DSS=False
Gate Time Interval=1HOUR
Gate Use Fixed Start Time=False
Gate Openings= 150
       6    6.23    6.45    6.68     6.9    7.13    7.35    7.58     7.8    8.03
    8.25    8.48     8.7    8.93    9.15    9.38     9.6    9.83   10.05   10.28
    10.5   10.73   10.95   11.18    11.4   11.63   11.85   12.08    12.3   12.53
   12.75   12.98    13.2   13.43   13.65   13.88    14.1   14.33   14.55   14.78
      15   14.83   14.66   14.49   14.32   14.15   13.98   13.81   13.64   13.47
   13.31   13.14   12.97    12.8   12.63   12.46   12.29   12.12   11.95   11.78
   11.61   11.44   11.27    11.1   10.93   10.76   10.59   10.42   10.25   10.08
    9.92    9.75    9.58    9.41    9.24    9.07     8.9    8.73    8.56    8.39
    8.22    8.05    7.88    7.71    7.54    7.37     7.2    7.03    6.86    6.69
    6.53    6.36    6.19    6.02    5.85    5.68    5.51    5.34    5.17       5
       5       5       5       5       5       5       5       5       5       5
       5       5       5       5       5       5       5       5       5       5
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Boundary Location=Bald Eagle      ,Loc Hav         ,659.942 ,        ,                ,                ,                ,                                ,
Rating Curve= 7
   529.2       0     535    1000     540    3000   557.3   16500   562.1   27000
   564.1   32500   568.6   47000
Use DSS=False
Use Fixed Start Time=False
Is Critical Boundary=False
Precipitation Mode=Disable
Wind Mode=No Wind Forces
Air Density Mode=Specified
Met BC=Precipitation|Mode=None
Met BC=Precipitation|Expanded View=0
Met BC=Precipitation|Constant Units=mm/hr
Met BC=Precipitation|Point Interpolation=
Met BC=Precipitation|Gridded Source=DSS
Met BC=Evapotranspiration|Mode=None
Met BC=Evapotranspiration|Expanded View=0
Met BC=Evapotranspiration|Point Interpolation=Nearest
Met BC=Evapotranspiration|Gridded Source=DSS
Met BC=Wind Speed|Expanded View=0
Met BC=Wind Speed|Point Interpolation=Nearest
Met BC=Wind Speed|Gridded Source=DSS
Met BC=Wind Direction|Expanded View=0
Met BC=Wind Direction|Point Interpolation=Nearest
Met BC=Wind Direction|Gridded Source=DSS
Met BC=Wind Velocity X|Expanded View=0
Met BC=Wind Velocity X|Point Interpolation=Nearest
Met BC=Wind Velocity X|Gridded Source=DSS
Met BC=Wind Velocity Y|Expanded View=0
Met BC=Wind Velocity Y|Point Interpolation=Nearest
Met BC=Wind Velocity Y|Gridded Source=DSS
Met BC=Air Density|Mode=Constant
Met BC=Air Density|Expanded View=0
Met BC=Air Density|Constant Value=1.225
Met BC=Air Density|Constant Units=kg/m3
Met BC=Air Density|Point Interpolation=Nearest
Met BC=Air Density|Gridded Source=DSS
Met BC=Air Temperature|Expanded View=0
Met BC=Air Temperature|Point Interpolation=Nearest
Met BC=Air Temperature|Gridded Source=DSS
Met BC=Humidity|Expanded View=0
Met BC=Humidity|Point Interpolation=Nearest
Met BC=Humidity|Gridded Source=DSS
Met BC=Air Pressure|Mode=Constant
Met BC=Air Pressure|Expanded View=0
Met BC=Air Pressure|Constant Value=1013.2
Met BC=Air Pressure|Constant Units=mb
Met BC=Air Pressure|Point Interpolation=Inv Distance
Met BC=Air Pressure|Gridded Source=DSS
Non-Newtonian Method= 0 ,
Non-Newtonian Constant Vol Conc=0
Non-Newtonian Yield Method= 0 ,
Non-Newtonian Yield Coef=0, 0
User Yeild=   0
Non-Newtonian Sed Visc= 0 ,
Non-Newtonian Obrian B=0
User Viscosity=0
User Viscosity Ratio=0
Herschel-Bulkley Coef=0, 0
Clastic Method= 0 ,
Coulomb Phi=0
Voellmy X=0
Non-Newtonian Hindered FV= 0
Non-Newtonian FV K=0
Non-Newtonian ds=0
Non-Newtonian Max Cv=0
Non-Newtonian Bulking Method= 0 ,
Non-Newtonian High C Transport= 0 ,
Lava Activation= 0
Temperature=1300,15,,15,14,980
Heat Ballance=1,1200,0.5,1,70,0.95
Viscosity=1000,,,
Profile Coefficient=4,1.3,
Lava Param=,2500,

--- BaldEagle.g01 (geometry) ---

Geom Title=Existing Conditions - GIS Data
Program Version=3.10

River Reach=Bald Eagle      ,Loc Hav
Reach XY= 30
      1967609.38       288126.34        1969162.       290296.16
      1968887.13       292762.63      1970889.75       294943.97
      1972765.13       295643.84      1974573.75       294280.47
        1977661.        294589.5      1983420.38       301436.53
       1990774.5       307828.81      1992858.63       312472.09
       1994404.5       312918.47      1998621.63       312165.69
        2012330.       326268.47      2013869.38       327086.34
      2017013.13       325792.44       2020166.5       328480.91
       2024510.5       334273.81       2028609.5       334344.84
      2034689.63       338279.03        2037112.       340501.03
      2036252.13       343747.84      2037500.13       346710.75
      2039651.88       347285.81      2039689.25       349508.34
      2045787.13       347590.72       2047519.5       346142.34
      2055172.25       349196.34        2056631.         350650.
      2061241.13       350463.09      2065322.25       353446.47

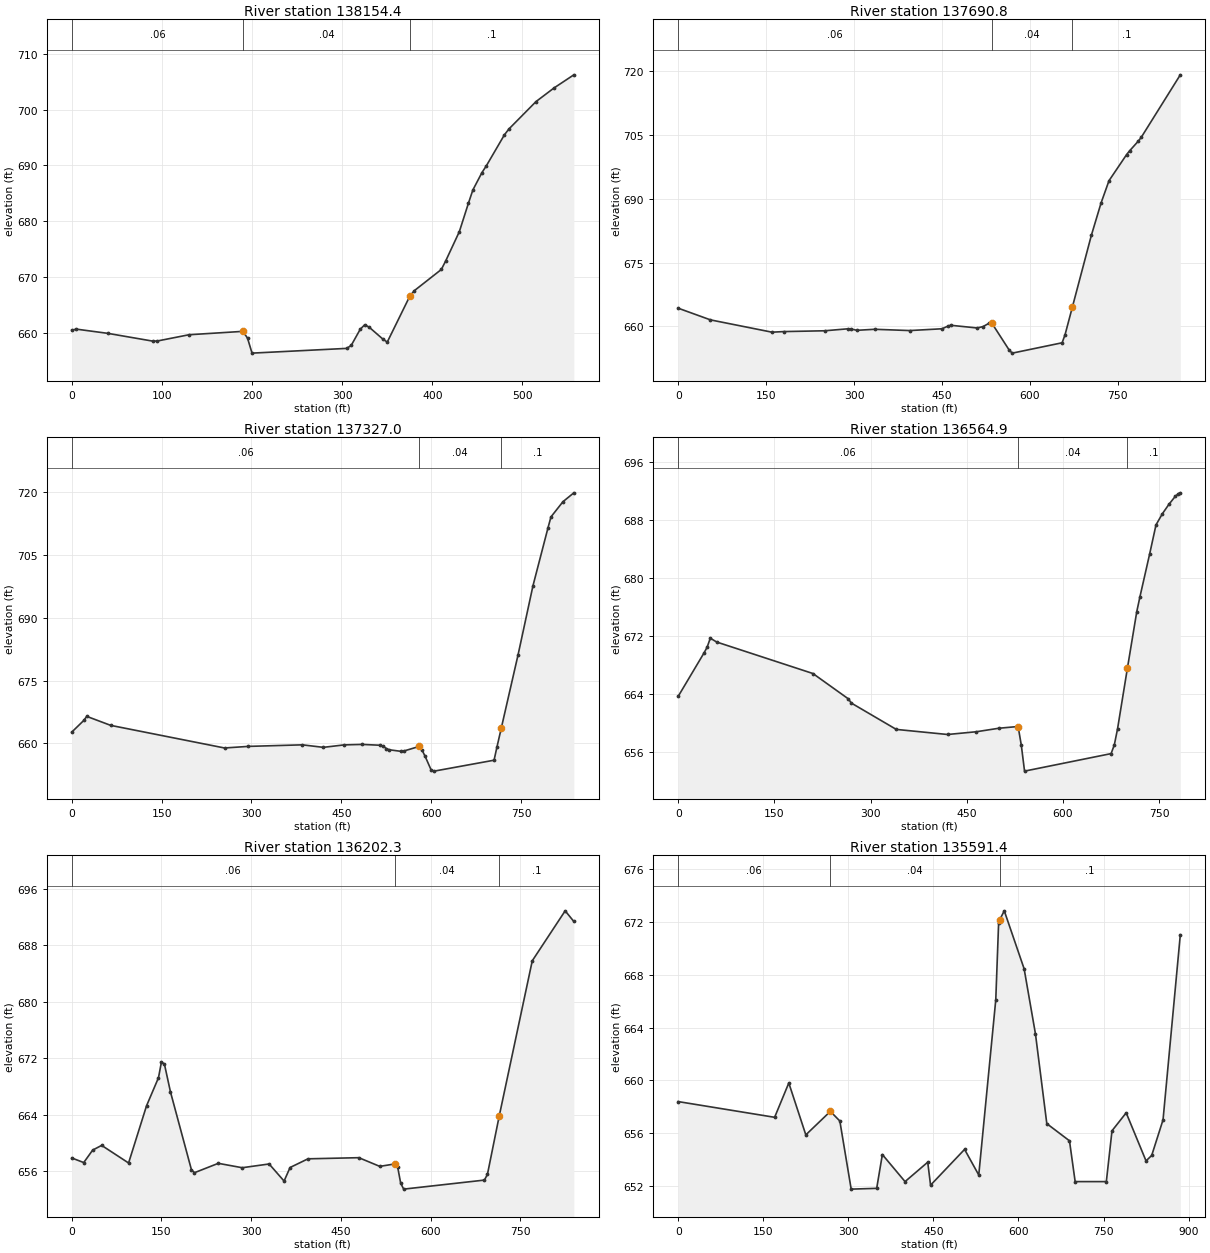
Type RM Length L Ch R = 1 ,138154.4,358.43,463.64,517.64
XS GIS Cut Line= 2
      1968668.17       290166.79      1969067.87       289778.85
#Sta/Elev= 30
       0  660.41       5  660.61      40  659.85      90  658.45      95  658.48
     130   659.6     190  660.21     195  658.98     200   656.3     305  657.15
     310  657.68     320  660.58  324.99  661.39     330  660.95     345  658.84
     350  658.28     375  666.52     380  667.51     410  671.32     415  672.91
     430  678.12     440  683.19     445   685.6     455   688.7     460  689.95
     480   695.5     485  696.55  514.99  701.46     535  703.91  557.01  706.27
#Mann= 3 , 0 , 0
       0     .06       0     190     .04       0     375      .1       0
Bank Sta=190,375
XS Rating Curve= 0
Exp/Cntr=0.3,0.1

Type RM Length L Ch R = 1 ,137690.8,305.71,363.84,382.83
XS GIS Cut Line= 4
      1968627.02       290584.12      1969009.09       290343.13
      1969273.59       290290.23      1969408.78       290290.23
#Sta/Elev= 30
       0  664.28      55  661.54     160  658.65  180.01  658.79     250  658.98
  290.01  659.45     295  659.39     305  659.09     335  659.33     395  659.03
     450  659.45  460.01  660.06     465  660.27     510  659.64     520  659.96
     530  660.72     535  660.79     565  654.38     570  653.73     655  656.16
     660  658.06  672.56  664.59     705  681.46  721.46  689.01     735  694.24
     765  700.36     770  701.23     785  703.53     790  704.42  856.65   719.1
#Mann= 3 , 0 , 0
       0     .06       0     535     .04       0  672.56      .1       0
Bank Sta=535,672.56
XS Rating Curve= 0
Exp/Cntr=0.3,0.1

Type RM Length L Ch R = 1 ,137327.0,732.93,762.02,765.36
XS GIS Cut Line= 4
      1968585.88        290854.5      1968868.02       290736.95
       1969085.5       290672.29      1969391.15       290672.29
#Sta/Elev= 30
       0  662.72      20   665.5      25  666.48      65  664.33  254.99  658.93
     295  659.31     385  659.68     420  659.08     455  659.67     485  659.78
     515  659.58     520  659.38  524.99   658.8     530   658.5     550  658.12
     555  658.23     580   659.3     585  658.36     590  656.91     600  653.66
     605   653.4     705  656.01     710  659.27  717.24  663.79     745  681.14
     770  697.71     795   711.5     800  714.13     820  717.76  838.19  719.88
#Mann= 3 , 0 , 0
       0     .06       0     580     .04       0  717.24      .1       0
Bank Sta=580,717.24
XS Rating Curve= 0
Exp/Cntr=0.3,0.1

Type RM Length L Ch R = 1 ,136564.9,349.61,362.64,370.75
XS GIS Cut Line= 3
      1968521.22       291524.58      1968903.29       291424.66
      1969291.23       291430.54
#Sta/Elev= 28
       0  663.72      40  669.65      45  670.46   50.01  671.71      60  671.18
     210  666.85     265  663.38     270  662.78     340  659.16     420  658.46
     465  658.84     500  659.32  530.01  659.56  535.01  656.96     540  653.42
     675  655.83     680  657.03     685  659.22  700.46  667.61     715  675.36
     720  677.43     735  683.26     745   687.3     755  688.84     765  690.11
     775  691.22     780   691.6   782.9  691.71
#Mann= 3 , 0 , 0
       0     .06       0  530.01     .04       0  700.46      .1       0
Bank Sta=530.01,700.46
XS Rating Curve= 0
Exp/Cntr=0.3,0.1

Type RM Length L Ch R = 1 ,136202.3,590.5,610.86,647.38
XS GIS Cut Line= 3
      1968468.32        291918.4      1968715.19       291753.82
      1969255.96       291800.84
#Sta/Elev= 30
       0  657.88      20  657.23      35     659      50  659.66      95  657.17
     125  665.26     145  669.24     150  671.49     155  671.14     165  667.24
     200  656.24     205  655.79     245  657.12  285.01   656.5  330.01  657.03
     355  654.61     365  656.53     395  657.76     480  657.92     515  656.69
  539.89  657.03     545  656.56     550   654.3     555  653.47     690  654.75
     695  655.55  714.84  663.86     770  685.79     825  692.86  839.51  691.35
#Mann= 3 , 0 , 0
       0     .06       0  539.89     .04       0  714.84      .1       0
Bank Sta=539.89,714.84
XS Rating Curve= 0
Exp/Cntr=0.3,0.1

Type RM Length L Ch R = 1 ,135591.4,601.41,522.71,423.08
XS GIS Cut Line= 4
      1968485.96       292294.59      1968820.99       292335.73
      1969114.89        292423.9      1969355.88       292429.78
#Sta/Elev= 30
       0   658.4     170  657.21  194.99  659.81     225  655.88  268.29  657.66
     285  656.93  304.99  651.77  349.99  651.83  359.99  654.39  399.99  652.34
     440  653.81     445  652.07     505  654.78  529.99  652.84     560  666.11
     565   671.9  567.13  672.19  574.99  672.85     610  668.46  629.99  663.53
     650  656.73  689.99  655.43  699.99  652.34  754.99  652.34  764.99  656.19
  789.99  657.55  824.99  653.91  834.99  654.32     855  657.02  885.45  671.04
#Mann= 3 , 0 , 0
       0     .06       0  268.29     .04       0  567.13      .1       0
Levee=0,,,-1,574.99,,0,0
Bank Sta=268.29,567.13
XS Rating Curve= 0
Exp/Cntr=0.3,0.1

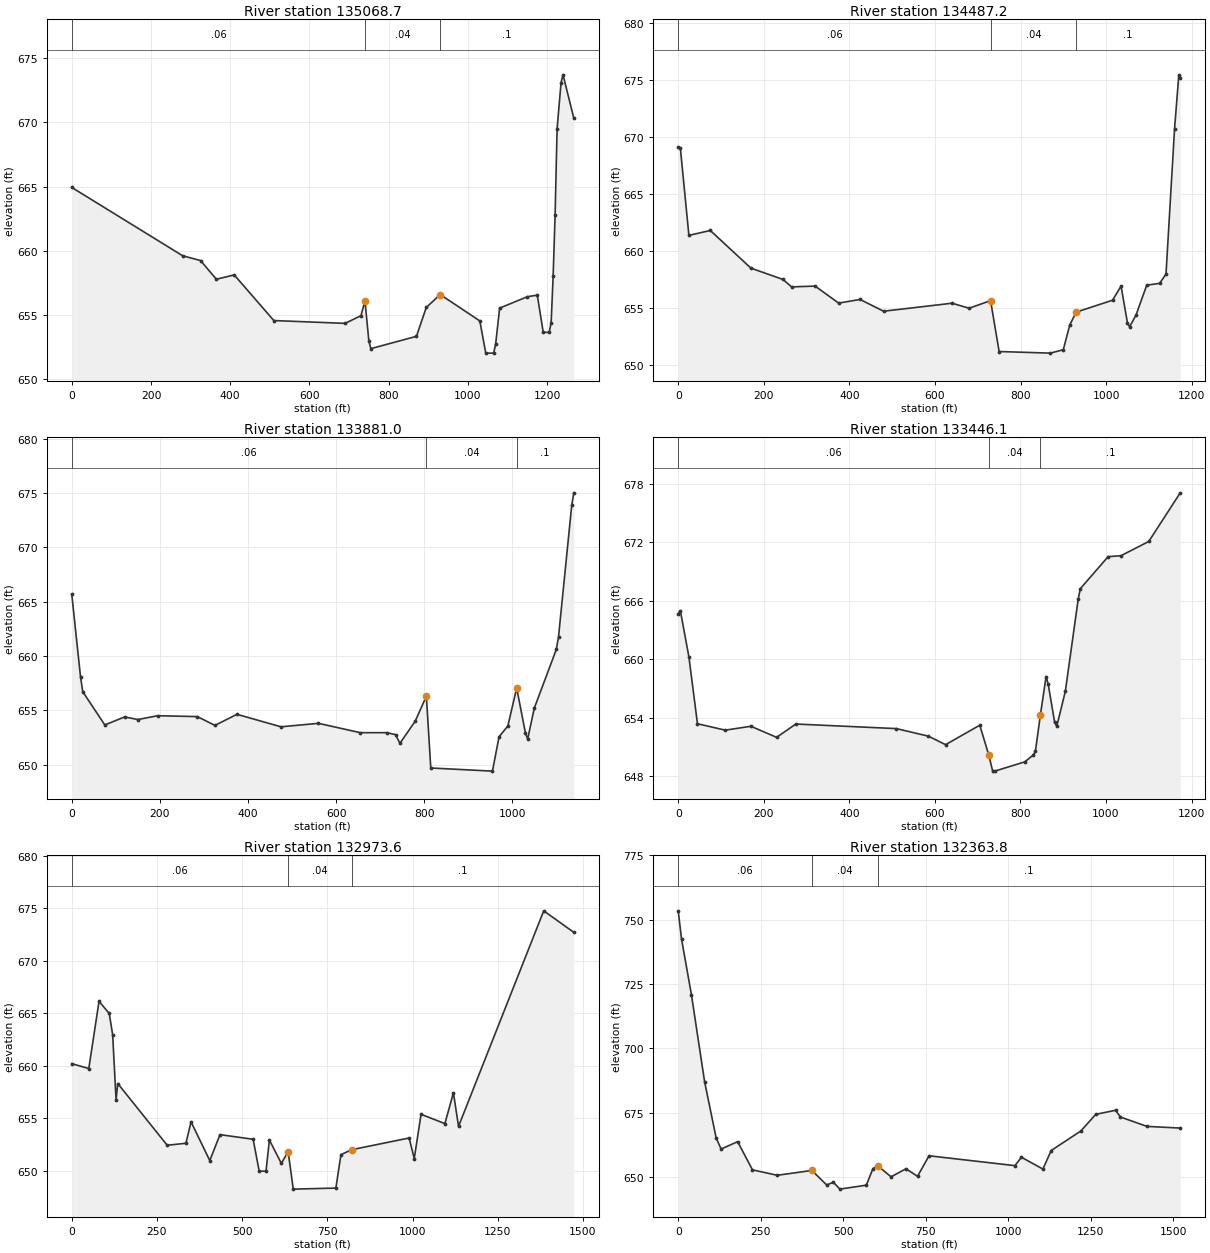
Type RM Length L Ch R = 1 ,135068.7,630.3,581.51,462.03
XS GIS Cut Line= 3
      1968177.37       293091.04      1969106.07       292785.39
      1969394.09       292814.78
#Sta/Elev= 30
       0  664.93  279.99   659.6     325  659.23  364.99  657.77     410  658.11
  509.99  654.55  689.99  654.33     730  654.93     740  656.09  749.99  652.93
  754.99  652.36     870  653.32  894.78  655.57  929.99  656.58 1029.99  654.52
 1044.99  652.01    1065  652.01    1070  652.75 1079.99  655.52 1149.99  656.41
 1174.99  656.53    1190  653.63    1205  653.63 1209.99  654.37    1215  658.01
    1220   662.8 1224.99  669.49 1234.99   673.1    1240  673.71 1267.22  670.33
#Mann= 3 , 0 , 0
       0     .06       0     740     .04       0  929.99      .1       0
Bank Sta=740,929.99
XS Rating Curve= 0
Exp/Cntr=0.3,0.1

Type RM Length L Ch R = 1 ,134487.2,605.29,606.25,590.87
XS GIS Cut Line= 3
       1968594.7       293702.34      1969164.85       293402.57
      1969564.55       293055.77
#Sta/Elev= 30
       0  669.08       5  669.03   24.99  661.37      75   661.8     170   658.5
  244.99  657.51  264.99  656.86  319.99  656.93  374.99  655.44     425  655.76
     480  654.73     640  655.43  679.99  654.99     730  655.66     750   651.2
  869.99  651.06  899.99  651.36  914.99  653.51  929.99  654.65    1015  655.69
 1034.99  656.93 1049.99  653.69    1055  653.37    1070   654.4 1094.99  657.01
 1124.99  657.17 1139.99  657.97    1160   670.7 1169.99  675.43 1173.33  675.19
#Mann= 3 , 0 , 0
       0     .06       0     730     .04       0  929.99      .1       0
Bank Sta=730,929.99
XS Rating Curve= 0
Exp/Cntr=0.3,0.1

Type RM Length L Ch R = 1 ,133881.0,465.19,434.84,425.17
XS GIS Cut Line= 3
      1969135.46       294207.84      1969670.35       293696.46
      1969993.63       293461.35
#Sta/Elev= 30
       0  665.68      20  658.03      25  656.71      75  653.65  120.01  654.39
     150  654.15     195   654.5     285  654.42     325  653.61     375  654.63
  475.01  653.48     560   653.8     655  652.94     715  652.94     735  652.76
     745  651.96     780  654.02     805  656.31  815.01  649.69     955   649.4
     970  652.56  990.01  653.56    1010  657.05    1030  652.89    1035  652.36
    1050   655.2    1100   660.6    1105  661.76    1135  673.88 1139.74  675.02
#Mann= 3 , 0 , 0
       0     .06       0     805     .04       0    1010      .1       0
Bank Sta=805,1010
XS Rating Curve= 0
Exp/Cntr=0.3,0.1

Type RM Length L Ch R = 1 ,133446.1,442.14,472.56,494.87
XS GIS Cut Line= 4
      1969546.91       294507.61      1969934.85       294043.26
      1970205.24       293825.78      1970287.53       293620.05
#Sta/Elev= 30
       0  664.63       5  664.98      25  660.23      45  653.36     110   652.7
     170   653.1  230.01  651.96     275  653.33     510  652.86     585  652.08
  625.01  651.21     705  653.21  726.26   650.1     735  648.51     740  648.49
     810  649.44     830  650.14     835  650.52  846.56  654.23     860  658.21
     865  657.41     880   653.5     885   653.1  905.01   656.7     935  666.13
  940.01  667.24    1005  670.53 1035.01  670.63 1100.01  672.09 1173.65  677.09
#Mann= 3 , 0 , 0
       0     .06       0  726.26     .04       0  846.56      .1       0
Bank Sta=726.26,846.56
XS Rating Curve= 0
Exp/Cntr=0.3,0.1

Type RM Length L Ch R = 1 ,132973.6,602.1,609.75,637.11
XS GIS Cut Line= 4
      1969843.75       294798.57      1970208.18       294410.63
      1970502.07       294199.02      1970784.21       293693.52
#Sta/Elev= 30
       0  660.19      50  659.73      80  666.13     110  664.97     120  662.94
     130  656.75     135   658.3     280  652.42     335  652.61     350  654.65
     405  650.96     435  653.43  532.27  652.99     550  649.95     570  649.95
  579.99  652.92     615  650.69     635  651.81     650  648.24  774.99  648.34
     790  651.53  822.11     652     990  653.11    1005  651.15    1025  655.37
    1095  654.48    1120  657.42    1135  654.22    1385  674.75 1473.32   672.7
#Mann= 3 , 0 , 0
       0     .06       0     635     .04       0  822.11      .1       0
Levee=-1,80,,0,,,0,0
Bank Sta=635,822.11
XS Rating Curve= 0
Exp/Cntr=0.3,0.1

Type RM Length L Ch R = 1 ,132363.8,749.24,664.14,507.86
XS GIS Cut Line= 5
      1970366.88       295115.97        1970602.       294845.59
       1970919.4       294645.74      1971225.05       294298.95
      1971336.73        293993.3
#Sta/Elev= 30
       0  753.43    9.99  742.53      40  720.86   79.99  686.96     115  665.13
  129.99  660.83     180   663.7     225  652.75     300  650.63     405  652.51
     450  646.86     470  647.93     490  645.25  569.99   646.8     590  653.22
     605  654.25  644.99  650.02     690  653.17     725  650.24  759.99  658.21
 1019.99  654.38    1040  657.64 1104.99  653.04    1130  660.26    1220  667.86
 1264.99  674.32 1324.99   675.9    1340  673.27 1419.99  669.64 1521.06  668.98
#Mann= 3 , 0 , 0
       0     .06       0     405     .04       0     605      .1       0
Bank Sta=405,605
XS Rating Curve= 0
Exp/Cntr=0.3,0.1

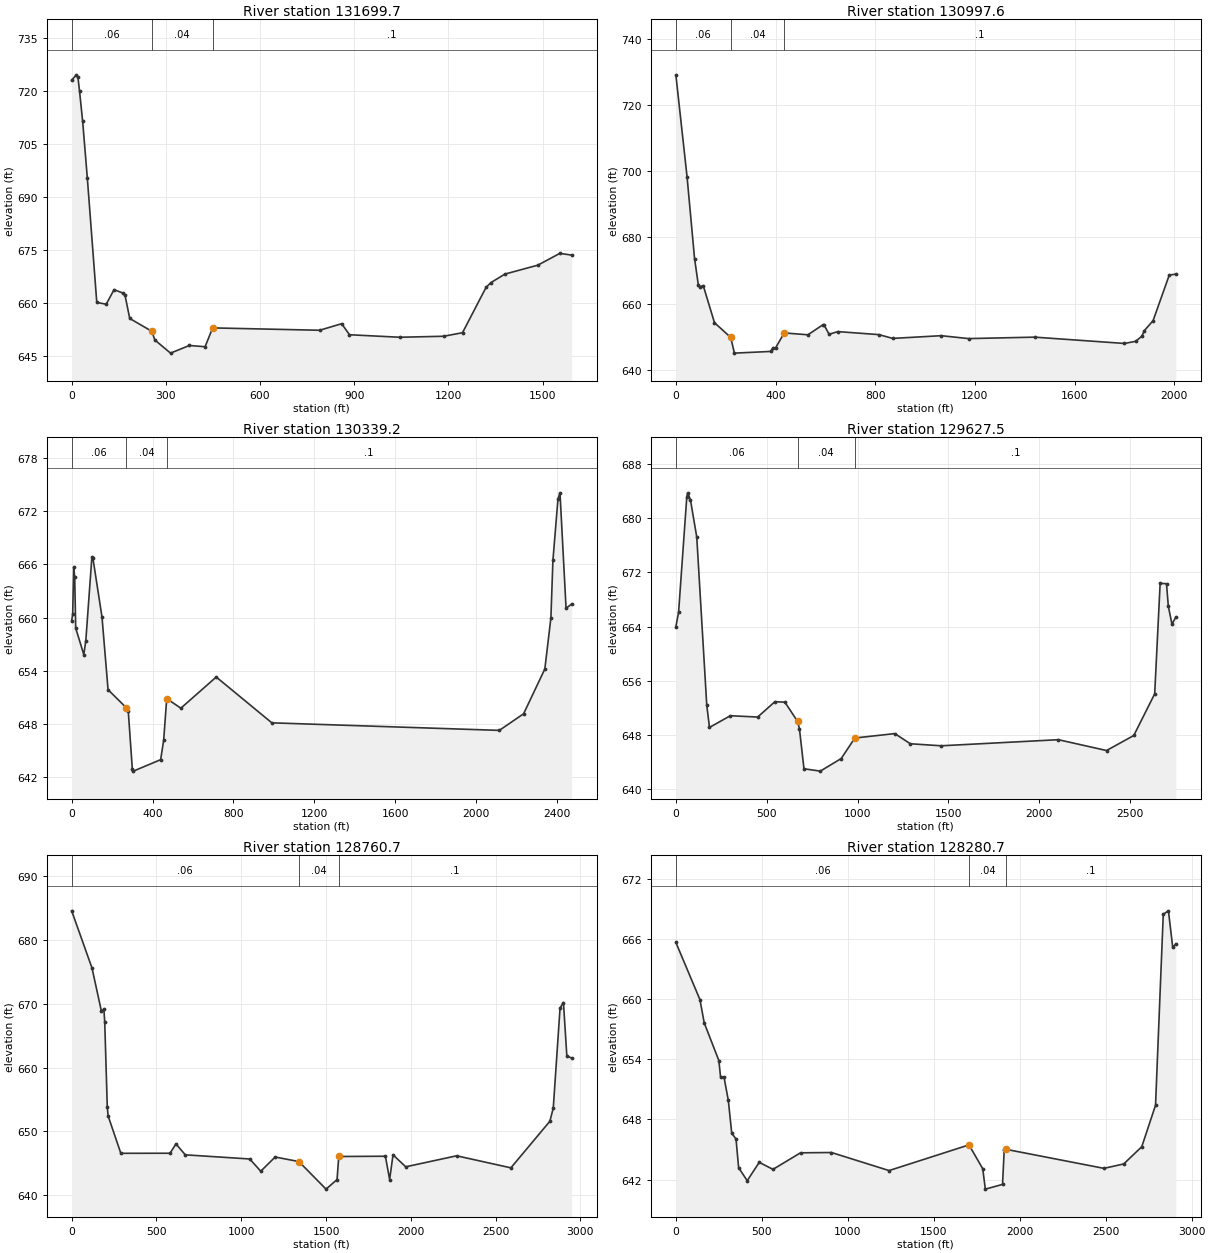
Type RM Length L Ch R = 1 ,131699.7,702.76,702.06,725.61
XS GIS Cut Line= 3
      1971113.37       295433.38      1971589.48       294522.31
      1971565.97       293958.03
#Sta/Elev= 30
       0  723.08      15  724.58      20  723.91      25  720.01      35   711.4
      50  695.21      80  660.09     110  659.57     135  663.69     165  662.68
     170  662.07     185  655.53     255  651.92     265  649.43     315  645.71
     375  647.88     425  647.52  449.15  652.86     790  652.19     860  654.05
     885  650.92    1045  650.21    1185  650.49    1245   651.5    1320  664.34
    1335  665.67    1380  668.11    1485  670.64    1555  673.98 1592.74  673.49
#Mann= 3 , 0 , 0
       0     .06       0     255     .04       0  449.15      .1       0
Bank Sta=255,449.15
XS Rating Curve= 0
Exp/Cntr=0.3,0.1

Type RM Length L Ch R = 1 ,130997.6,698.14,658.4,583.48
XS GIS Cut Line= 3
      1971777.57       295686.13      1972094.98       295027.81
      1972218.41       293758.18
#Sta/Elev= 30
       0  729.25   45.01  698.32   75.01  673.62      90  665.73      95  665.04
  110.01   665.4     155  654.19     220  649.74     235  644.98     380  645.49
     390  646.61     400  646.55     435   651.1     530  650.53     590  653.56
     595  653.46     615  650.69     650   651.5     815  650.58  870.01  649.44
    1065  650.26    1175  649.38    1440  649.82    1800  647.91    1845  648.55
    1870  650.11 1880.01   651.8    1915  654.81 1980.01  668.63 2006.46  668.89
#Mann= 3 , 0 , 0
       0     .06       0     220     .04       0     435      .1       0
Bank Sta=220,435
XS Rating Curve= 0
Exp/Cntr=0.3,0.1

Type RM Length L Ch R = 1 ,130339.2,753.78,711.7,428.92
XS GIS Cut Line= 3
      1972453.53       295991.78      1972735.67       294681.01
       1972647.5       293552.45
#Sta/Elev= 30
       0  659.66       5  660.36      10  665.65      15  664.59      20  658.82
      60  655.84      70  657.41     100  666.83     105  666.71     150  660.07
     180  651.88  270.28  649.85     280  649.44     300  642.94     305  642.71
     440     644     455  646.19     470  650.88     540   649.8     715  653.31
     990  648.15    2115   647.3    2235  649.17    2340  654.21    2370  659.96
    2380  666.44    2405  673.37 2415.01  674.06 2445.01  661.05 2472.79  661.54
#Mann= 3 , 0 , 0
       0     .06       0  270.28     .04       0     470      .1       0
Levee=-1,100,,0,,,0,0
Bank Sta=270.28,470
XS Rating Curve= 0
Exp/Cntr=0.3,0.1

Type RM Length L Ch R = 1 ,129627.5,792.27,866.78,581.35
XS GIS Cut Line= 5
      1973135.37       296256.28      1973252.92       295838.95
      1973211.78       295403.99      1973058.95       294681.01
       1972994.3        293540.7
#Sta/Elev= 30
       0  663.96   14.99   666.1      60  683.09   64.99  683.74      80  682.75
     115  677.21     170  652.41     185  649.11     300  650.84  449.99  650.64
  544.99  652.91  599.99  652.84  670.01  649.99  679.99  648.92     705  643.01
     795  642.66     910  644.52     985  647.55 1204.99   648.2 1289.99   646.7
    1460   646.4 2104.99   647.3    2370   645.7    2520  647.92 2634.99  654.07
 2664.99  670.37    2700  670.33 2709.99  667.01 2729.99  664.35 2751.57   665.4
#Mann= 3 , 0 , 0
       0     .06       0  670.01     .04       0     985      .1       0
Bank Sta=670.01,985
XS Rating Curve= 0
Exp/Cntr=0.3,0.1

Type RM Length L Ch R = 1 ,128760.7,690.64,480.04,527.21
XS GIS Cut Line= 5
       1974043.5       296329.76      1973996.48       295242.35
      1973490.98       294466.47      1973396.93       294078.53
      1973396.93       293543.64
#Sta/Elev= 30
       0  684.59     120  675.61     175  668.89     190  669.15     195   667.1
  210.01  653.85     215  652.41     290  646.55     580  646.56     615  648.02
  670.01  646.31    1050  645.66 1115.01  643.74 1200.01  645.97    1340  645.25
    1500  640.93 1565.01  642.43    1575  646.05 1850.01  646.09    1875  642.44
    1895  646.31    1970  644.43    2270  646.16 2590.01  644.27 2820.01  651.58
 2840.01  653.66 2880.01  669.36 2900.01   670.2 2920.01  661.83 2948.52  661.49
#Mann= 3 , 0 , 0
       0     .06       0    1340     .04       0    1575      .1       0
Bank Sta=1340,1575
XS Rating Curve= 0
Exp/Cntr=0.3,0.1

Type RM Length L Ch R = 1 ,128280.7,624.03,869.82,966.85
XS GIS Cut Line= 5
       1975001.6       296153.42      1974948.69       295765.48
      1973996.48       294384.18      1973867.16       294078.53
      1973826.02       293573.03
#Sta/Elev= 30
       0  665.64     140  659.94     165  657.62     250  653.87  259.99  652.23
     280  652.21     305  649.91     325  646.63     350  646.04     365  643.19
     415  641.89     485  643.72     565  643.02  724.99  644.67  904.99   644.7
    1240   642.9    1705  645.46    1785  643.08    1800  641.05    1900  641.52
 1909.99  644.98 1919.47  645.02    2490  643.12    2605  643.56    2710  645.28
    2790  649.41    2835  668.45    2865  668.79    2890  665.14 2908.29   665.5
#Mann= 3 , 0 , 0
       0     .06       0    1705     .04       0 1919.47      .1       0
Bank Sta=1705,1919.47
XS Rating Curve= 0
Exp/Cntr=0.3,0.1

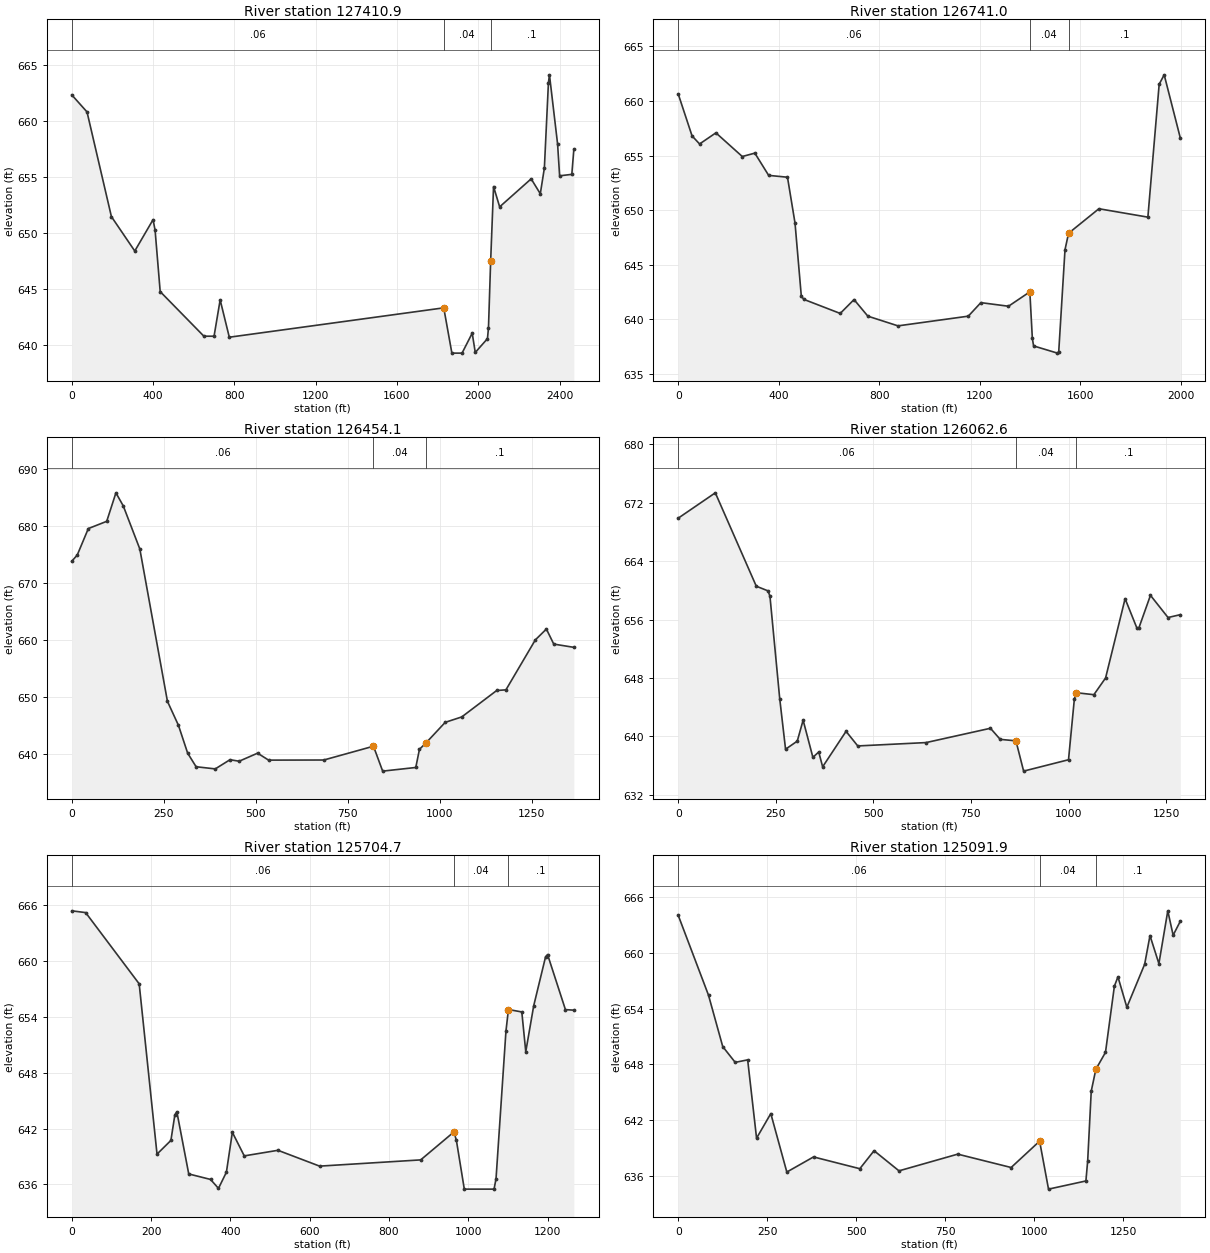
Type RM Length L Ch R = 1 ,127410.9,525.47,669.85,687.62
XS GIS Cut Line= 4
      1975301.37       296088.76      1975342.51         295548.
      1974931.06       294566.39      1974837.01       293708.22
#Sta/Elev= 30
       0  662.35      75  660.83  194.99  651.49  309.99  648.42  399.99  651.22
  409.99  650.26  434.99   644.8  649.99  640.82  699.99  640.82  729.99  644.06
  774.99  640.73    1830  643.35 1869.99  639.31 1919.99  639.31    1970  641.09
    1985  639.37    2045   640.6    2050  641.56 2060.71  647.51 2074.99  654.17
 2104.99  652.36 2259.99  654.86 2304.99  653.53 2324.99  655.82 2344.99  663.44
 2349.99  664.14    2390  657.97    2400  655.13    2460  655.26 2469.99  657.49
#Mann= 3 , 0 , 0
       0     .06       0    1830     .04       0 2060.71      .1       0
Levee=0,,,-1,2349.99,,0,0
Bank Sta=1830,2060.71
XS Rating Curve= 0
Exp/Cntr=0.3,0.1

Type RM Length L Ch R = 1 ,126741.0,333.52,286.93,256.77
XS GIS Cut Line= 4
      1975868.58        295827.2      1975727.52       295333.46
       1975545.3       294751.54      1975533.54       293875.74
#Sta/Elev= 30
       0  660.64   55.01   656.8      85  656.06     150  657.08     255  654.91
  305.01  655.22     360  653.18     435  653.01     465  648.81     490  642.12
     500  641.81     645  640.52     700  641.79     755  640.27     875  639.38
    1155  640.27 1205.01  641.51 1315.01  641.18    1400   642.5    1410  638.23
    1415  637.54    1510  636.88    1515  636.99 1540.01  646.36 1554.14  647.87
    1675  650.12 1870.01  649.35    1915  661.54    1935   662.4 1999.16  656.61
#Mann= 3 , 0 , 0
       0     .06       0    1400     .04       0 1554.14      .1       0
Levee=0,,,-1,1935,,0,0
Bank Sta=1400,1554.14
XS Rating Curve= 0
Exp/Cntr=0.3,0.1

Type RM Length L Ch R = 1 ,126454.1,377.59,391.45,384.49
XS GIS Cut Line= 4
      1975986.14       295245.29      1975909.73       294916.13
      1975786.29       294140.24      1975792.17       293899.25
#Sta/Elev= 30
       0  673.87      15  674.98      45  679.61      95  680.88     120  685.88
  140.01  683.58     185  676.02     260   649.3     290  645.08     315   640.2
  337.91  637.82     390  637.44  430.01  639.05  455.01  638.79     505   640.2
     535  638.98     685     639     820  641.42     845  637.05     935  637.69
     945  640.88  962.47  641.98    1015  645.61    1060  646.56    1155   651.2
 1180.01  651.31    1260  660.08    1290  661.98 1310.01  659.34 1364.62  658.77
#Mann= 3 , 0 , 0
       0     .06       0     820     .04       0  962.47      .1       0
Bank Sta=820,962.47
XS Rating Curve= 0
Exp/Cntr=0.3,0.1

Type RM Length L Ch R = 1 ,126062.6,285.47,357.95,390.57
XS GIS Cut Line= 3
      1976238.89       295210.02      1976244.77        294498.8
      1976133.09       293934.52
#Sta/Elev= 30
       0   669.9      95  673.37     200  660.58     230  659.94     235  659.21
     260  645.19     275  638.25     305  639.36     320  642.23     345  637.14
     360  637.87     370  635.84     430   640.7     460   638.7     635  639.16
     800  641.12     825   639.6  865.28   639.4     885  635.25    1000  636.81
    1015  645.13    1020  645.99    1065  645.72    1095  648.01    1145  658.87
    1175  654.88    1180  654.82    1210  659.33    1255  656.29 1286.47  656.68
#Mann= 3 , 0 , 0
       0     .06       0  865.28     .04       0    1020      .1       0
Bank Sta=865.28,1020
XS Rating Curve= 0
Exp/Cntr=0.3,0.1

Type RM Length L Ch R = 1 ,125704.7,473.48,612.79,661
XS GIS Cut Line= 3
      1976485.76       295251.17      1976550.42       294345.97
      1976562.18       293987.42
#Sta/Elev= 30
       0  665.39   35.01   665.2     170  657.55  215.01  639.26  250.01  640.73
     260  643.48     265  643.81  295.01  637.13  350.01  636.54     370  635.58
     390  637.32  405.01   641.6  435.01  639.07     520  639.67  625.01  637.97
  880.01  638.64  963.74  641.64  970.01  640.74     990   635.5    1065   635.5
    1070  636.61 1095.01  652.46 1101.26  654.79 1135.01  654.53    1145  650.26
    1165  655.19    1195  660.46    1200  660.69 1245.01  654.78 1266.25  654.72
#Mann= 3 , 0 , 0
       0     .06       0  963.74     .04       0 1101.26      .1       0
Bank Sta=963.74,1101.26
XS Rating Curve= 0
Exp/Cntr=0.3,0.1

Type RM Length L Ch R = 1 ,125091.9,428.97,476.36,494.42
XS GIS Cut Line= 3
       1976662.1        295374.6      1976932.48       294904.37
      1977255.77        294099.1
#Sta/Elev= 30
       0  664.05      85  655.45     125  649.91  159.99  648.21     195  648.48
     220  640.04  259.99  642.69     305  636.39     380  638.02     510  636.75
     550  638.69     620  636.52     785  638.32     935  636.88 1014.99  639.72
 1039.99  634.55    1145  635.43    1150   637.6    1160  645.11 1172.97  647.46
    1200  649.29    1225  656.42    1235  657.43    1260  654.15    1310  658.78
    1325  661.87    1350  658.85    1375  664.54    1390  661.91 1410.16  663.42
#Mann= 3 , 0 , 0
       0     .06       0 1014.99     .04       0 1172.97      .1       0
Bank Sta=1014.99,1172.97
XS Rating Curve= 0
Exp/Cntr=0.3,0.1

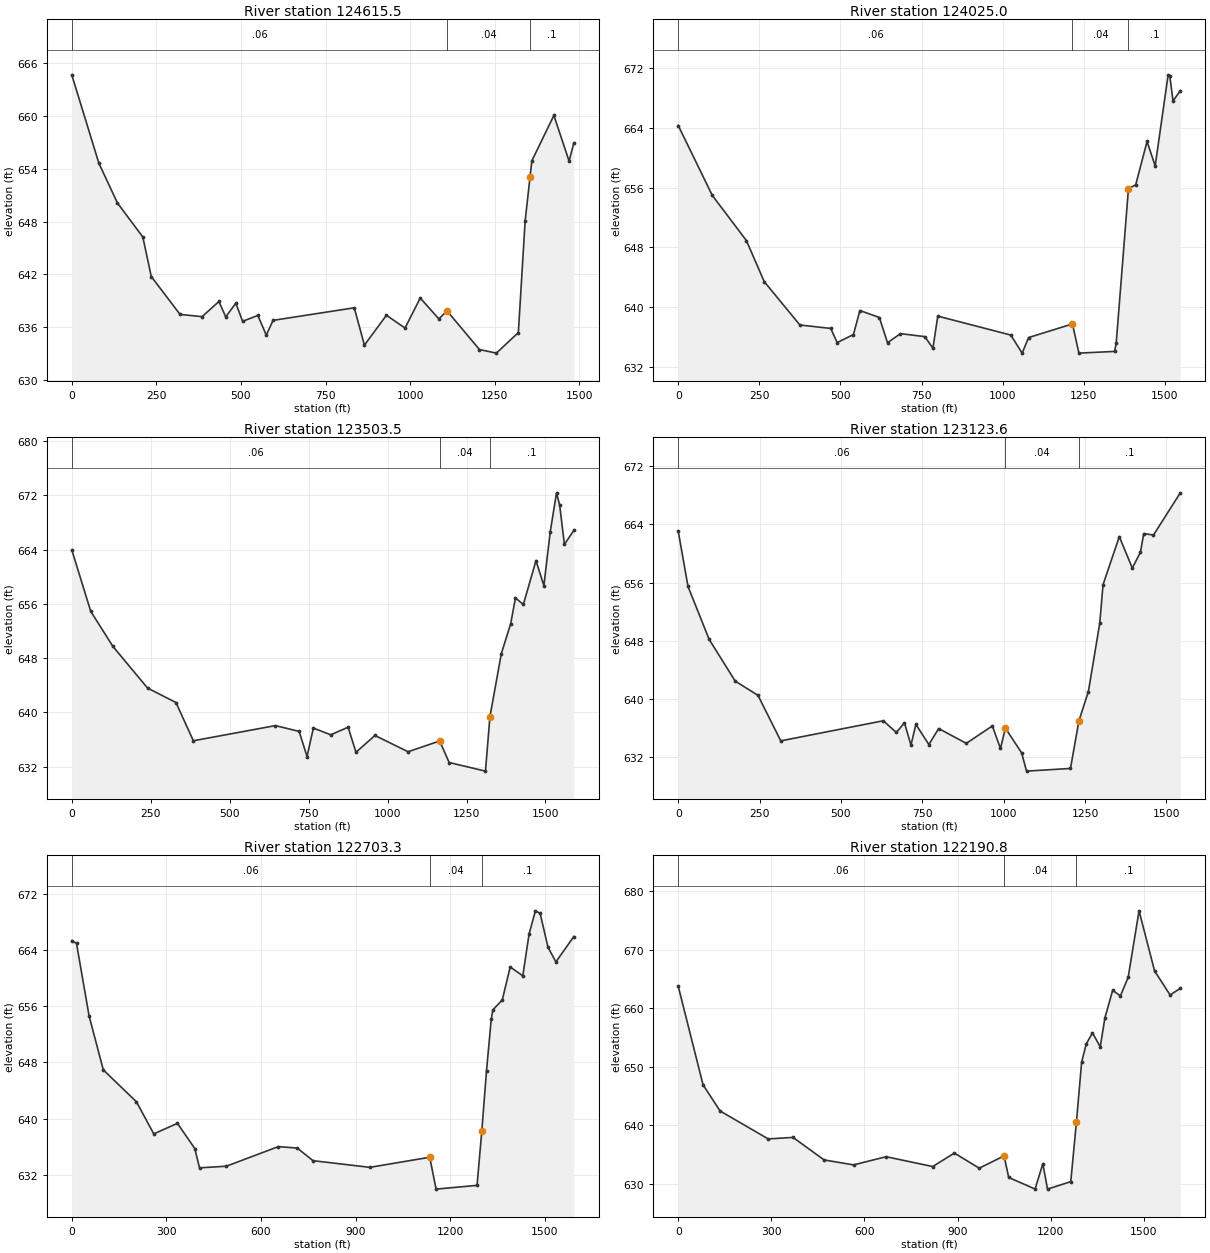
Type RM Length L Ch R = 1 ,124615.5,441.73,914.18,662.11
XS GIS Cut Line= 3
      1976859.01       295589.14      1977323.36       295001.35
      1977693.67       294366.54
#Sta/Elev= 30
       0  664.71      80  654.66  134.99  650.12     210  646.25     235  641.75
     320  637.44     385  637.18  434.99  638.91     455  637.16     485  638.71
     505  636.65  549.99  637.32     575  635.08     595  636.76  834.99  638.19
     865  633.94  929.99  637.34     985  635.89    1030   639.3    1085  636.93
 1109.14  637.84    1205  633.44    1255  633.03 1319.99  635.37 1339.99  648.04
  1354.6  653.12    1360  654.93 1424.99  660.09 1469.99  654.88    1484  656.96
#Mann= 3 , 0 , 0
       0     .06       0 1109.14     .04       0  1354.6      .1       0
Bank Sta=1109.14,1354.6
XS Rating Curve= 0
Exp/Cntr=0.3,0.1

Type RM Length L Ch R = 1 ,124025.0,572.63,521.51,485.35
XS GIS Cut Line= 3
      1977035.35        295812.5      1977834.74       295048.38
      1978228.56       294848.53
#Sta/Elev= 30
       0  664.32     105  654.95  209.99  648.91     265   643.4  374.99  637.59
     470  637.13  489.99  635.23     540  636.31  559.99  639.53     620  638.59
     645  635.21  684.99  636.43  759.99  636.03     785  634.48  799.99  638.78
 1024.99  636.24    1060  633.82    1080  635.91 1214.99  637.73 1234.99  633.82
 1344.99  634.05 1349.99  635.19 1387.62  655.85    1410  656.38    1445  662.18
 1469.99   658.9 1509.99  671.11 1514.99  671.01 1524.99  667.61 1547.48  668.98
#Mann= 3 , 0 , 0
       0     .06       0 1214.99     .04       0 1387.62      .1       0
Bank Sta=1214.99,1387.62
XS Rating Curve= 0
Exp/Cntr=0.3,0.1

Type RM Length L Ch R = 1 ,123503.5,421.82,379.84,377.71
XS GIS Cut Line= 2
      1977382.14       296218.08       1978563.6       295154.18
#Sta/Elev= 30
       0  663.98      60  654.91     130  649.74     240  643.58  330.01  641.44
     385   635.8  645.01  638.04     720  637.18     745  633.47     765  637.68
     820  636.68     875   637.8     900  634.11     960  636.58    1065  634.18
    1165  635.77    1195  632.59    1310  631.32 1324.06  639.31    1360  648.61
    1390   653.1    1405  656.88    1430  655.91    1470  662.38    1495  658.69
    1515   666.6    1535  672.39 1545.01  670.57    1560  664.78 1589.88  666.85
#Mann= 3 , 0 , 0
       0     .06       0    1165     .04       0 1324.06      .1       0
Bank Sta=1165,1324.06
XS Rating Curve= 0
Exp/Cntr=0.3,0.1

Type RM Length L Ch R = 1 ,123123.6,443.87,420.36,415.79
XS GIS Cut Line= 2
      1977752.45       296435.56      1978869.25       295371.66
#Sta/Elev= 30
       0  663.06      30  655.46      95  648.19     175  642.46     245   640.5
     315  634.25     630  637.01     670   635.4     695  636.73     715  633.66
     730  636.52     770  633.74     800  635.94     885  633.91     965   636.3
  989.99   633.2    1005     636    1055   632.6    1070  630.09    1205  630.46
 1230.87  636.98    1260  641.02    1295  650.42    1305   655.7    1355  662.31
 1394.99  657.99    1420  660.17    1430  662.73    1460  662.53 1542.44  668.33
#Mann= 3 , 0 , 0
       0     .06       0    1005     .04       0 1230.87      .1       0
Bank Sta=1005,1230.87
XS Rating Curve= 0
Exp/Cntr=0.3,0.1

Type RM Length L Ch R = 1 ,122703.3,487.95,512.48,505.87
XS GIS Cut Line= 2
       1978043.4       296779.42      1979166.08       295650.86
#Sta/Elev= 30
       0  665.39      15  665.01   55.01  654.62  100.01  646.94  205.01  642.39
     260  637.81     335  639.31     390  635.72     405  632.96  490.01  633.19
  655.01  635.99     715  635.78  765.01  633.98     945  633.03    1135  634.47
 1155.01  629.92 1285.01  630.46 1300.01  638.19    1315  646.84 1330.01  654.19
    1335   655.5    1365  656.93 1390.01  661.63    1430  660.37 1450.01  666.36
    1470  669.65 1485.01  669.28    1510  664.44    1535  662.36 1591.87  665.98
#Mann= 3 , 0 , 0
       0     .06       0    1135     .04       0 1300.01      .1       0
Bank Sta=1135,1300.01
XS Rating Curve= 0
Exp/Cntr=0.3,0.1

Type RM Length L Ch R = 1 ,122190.8,423.09,436.79,441.86
XS GIS Cut Line= 2
      1978357.87       297099.76       1979545.2        296000.6
#Sta/Elev= 30
       0  663.72      80  646.87     135   642.4     290  637.63     370  637.89
     470  634.04  564.99  633.19  669.99  634.59     820  632.91     890  635.21
  969.99  632.63    1050  634.73    1065  631.04 1149.99  629.07    1175   633.4
    1190  629.05    1265  630.33 1283.23  640.53 1300.01  650.76    1315  653.88
    1335  655.75 1360.01  653.37    1375  658.31    1400  663.02 1424.99  662.08
    1450  665.25    1485  676.61    1535  666.35    1585  662.23 1617.99  663.36
#Mann= 3 , 0 , 0
       0     .06       0    1050     .04       0 1283.23      .1       0
Bank Sta=1050,1283.23
XS Rating Curve= 0
Exp/Cntr=0.3,0.1