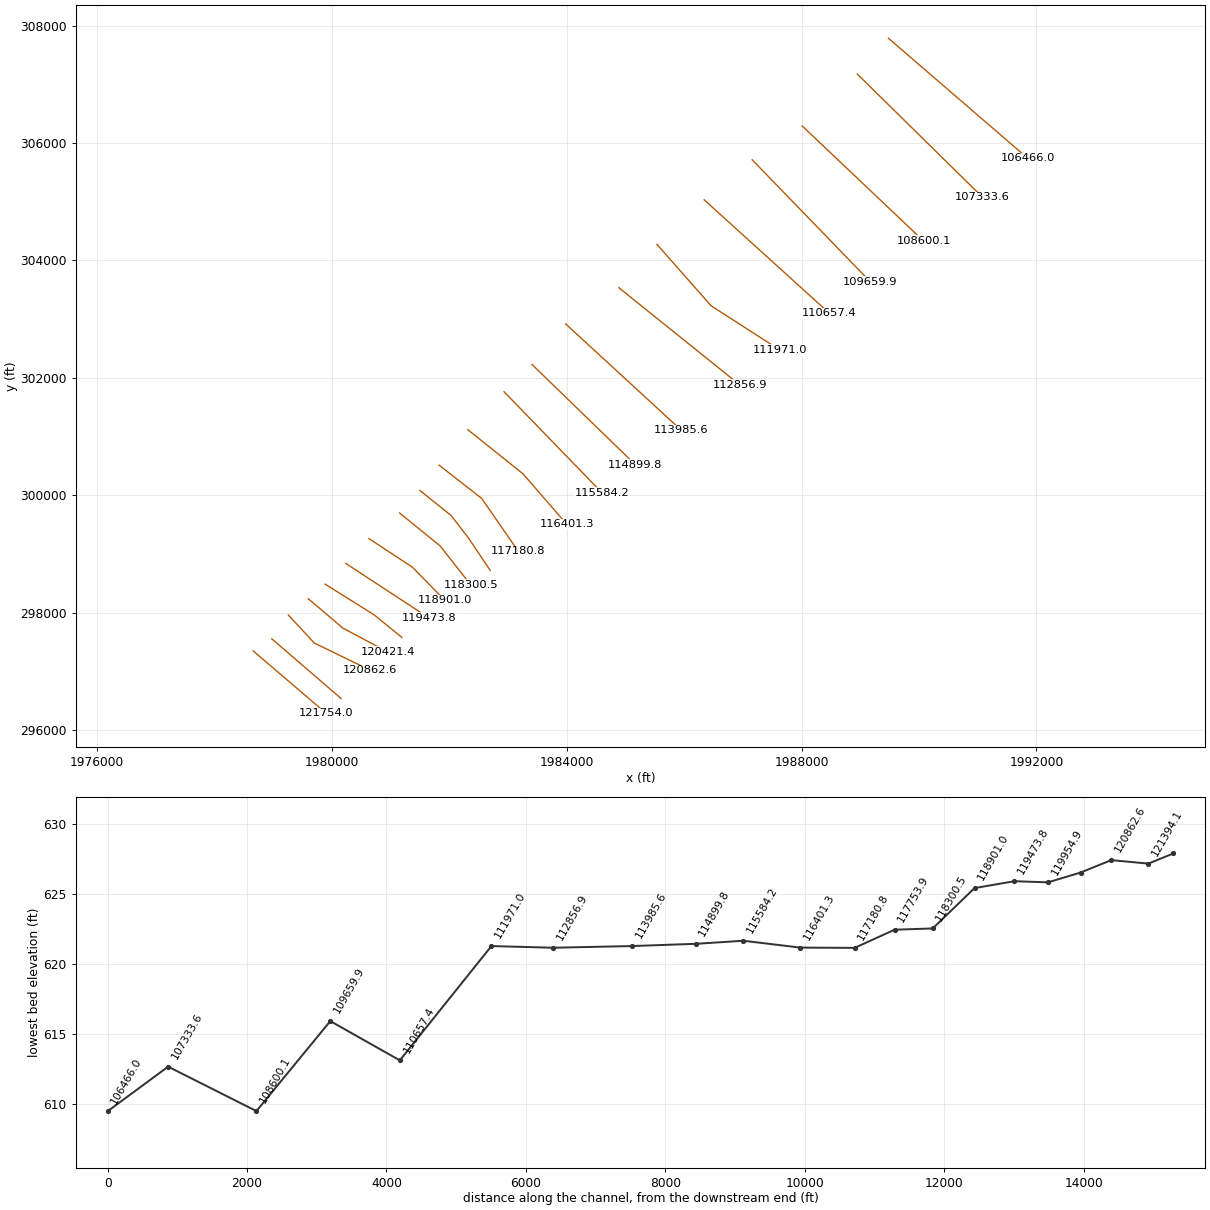
HEC-RAS study BaldEagle.prj: Bald Eagle Cr. for the WCDS Project

--- BaldEagle.g01 (geometry) --- (continued)

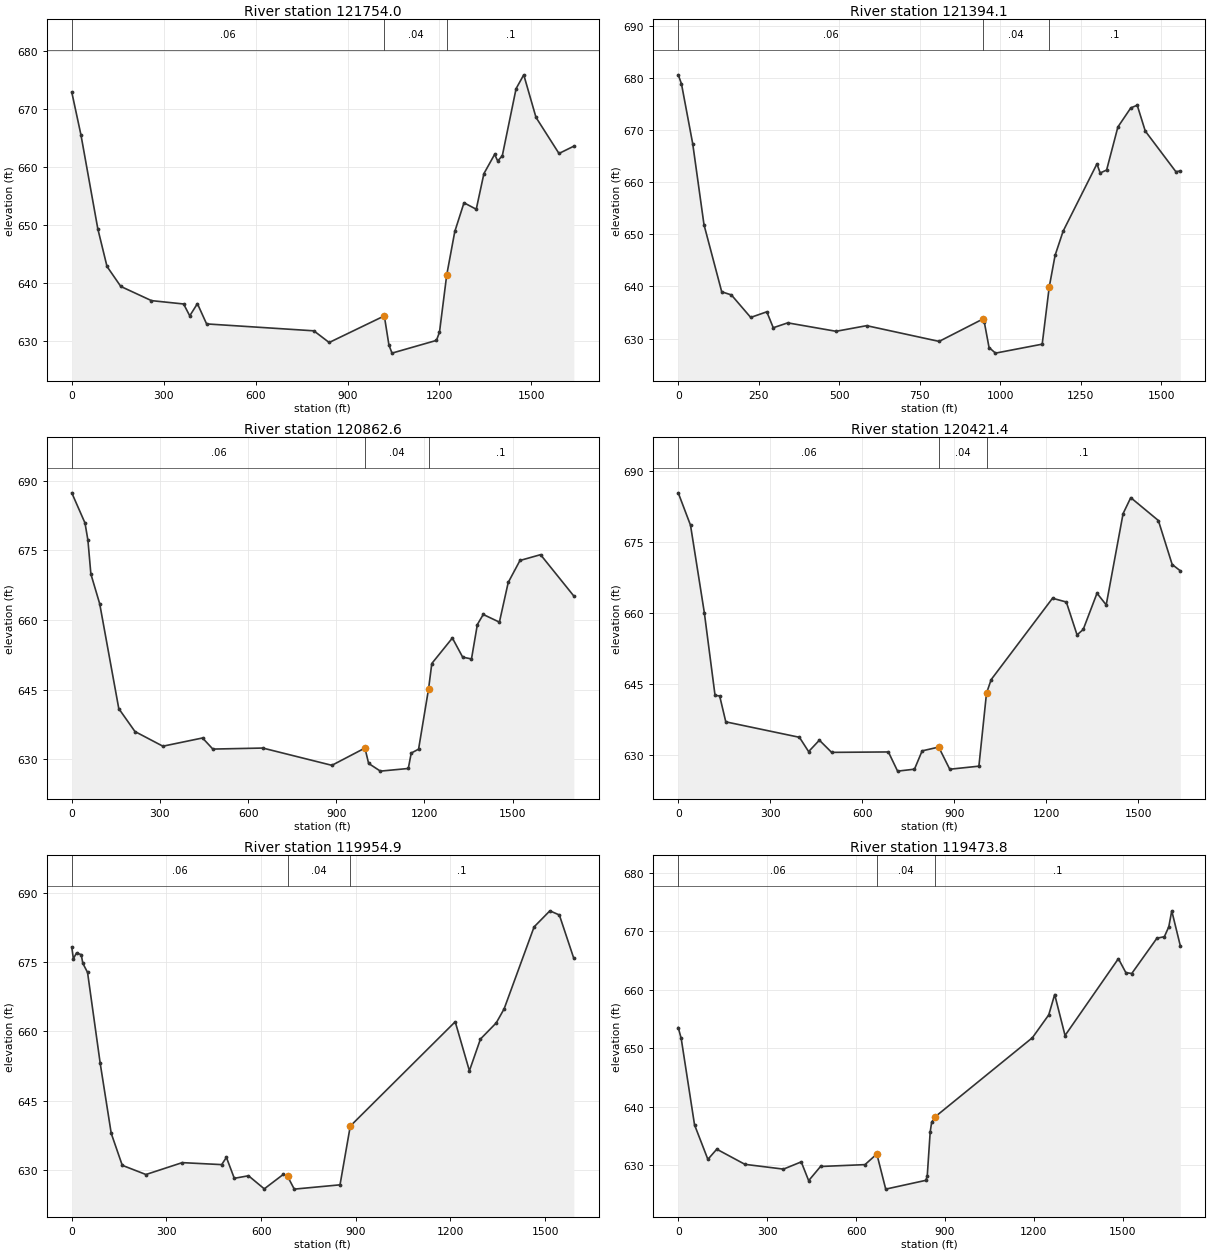
Type RM Length L Ch R = 1 ,121754.0,361.03,359.88,359.74
XS GIS Cut Line= 2
      1978660.58       297349.57      1979906.69       296285.67
#Sta/Elev= 30
       0  672.86      30  665.49      85  649.33     115  642.85  160.01  639.41
     260  636.97     365  636.39     385  634.35  410.01  636.45     440  632.96
     790  631.77     840  629.76    1020  634.34    1035  629.34    1045  627.93
    1190  630.12    1200  631.52 1223.63  641.38    1250  648.87    1280  653.81
    1320   652.7 1344.99  658.83    1380  662.15    1390  661.01 1404.99   661.9
    1450  673.46    1475  675.84    1515  668.51    1590   662.3  1638.5  663.56
#Mann= 3 , 0 , 0
       0     .06       0    1020     .04       0 1223.63      .1       0
Bank Sta=1020,1223.63
XS Rating Curve= 0
Exp/Cntr=0.3,0.1

Type RM Length L Ch R = 1 ,121394.1,462.9,531.56,619.74
XS GIS Cut Line= 2
      1978977.99        297555.3      1980159.44       296538.42
#Sta/Elev= 30
       0  680.61      10  678.89      45  667.37      80  651.84     135  638.97
     165  638.37     225  634.05     275  635.13     295  632.07     340  633.01
     490  631.39     585  632.47     810  629.45  945.01  633.72     950  633.25
  964.99  628.28     985   627.2    1130  628.92  1151.8  639.87    1170  645.96
    1195  650.61    1300  663.52    1310  661.77    1330  662.34    1365   670.6
    1405  674.26    1425  674.78    1450  669.82    1545  662.02  1558.8  662.16
#Mann= 3 , 0 , 0
       0     .06       0  945.01     .04       0  1151.8      .1       0
Bank Sta=945.01,1151.8
XS Rating Curve= 0
Exp/Cntr=0.3,0.1

Type RM Length L Ch R = 1 ,120862.6,506.39,441.14,441.89
XS GIS Cut Line= 3
      1979260.13       297960.87      1979700.97       297484.76
      1980653.19       297020.41
#Sta/Elev= 30
       0  687.39      45  680.89   54.99  677.17      65  669.91      95   663.5
     160  640.91     215  635.98  309.99  632.82  444.99  634.59  479.99   632.2
     650  632.42  884.99   628.7  997.46  632.42    1010  629.11    1050  627.45
    1145  628.02    1155  631.34    1180  632.18 1214.07   645.2 1224.99  650.63
    1295  656.12    1330     652    1360  651.61    1380  659.03    1400  661.19
 1454.99  659.54    1485  668.09    1525  672.82    1595  674.07 1708.27  665.16
#Mann= 3 , 0 , 0
       0     .06       0  997.46     .04       0 1214.07      .1       0
Bank Sta=997.46,1214.07
XS Rating Curve= 0
Exp/Cntr=0.3,0.1

Type RM Length L Ch R = 1 ,120421.4,459.43,466.56,457
XS GIS Cut Line= 3
      1979601.04       298237.13      1980188.83       297737.51
      1980952.96       297331.94
#Sta/Elev= 30
       0  685.46      40  678.61      85  660.12  120.01  642.58     135  642.48
     155  636.99     395  633.72     425  630.69  460.01  633.11     500  630.53
     685  630.62     715  626.56  770.01  626.97     795  630.85  849.03  631.65
     885  626.96     980  627.61 1004.83  643.05 1020.01  645.93    1220  663.15
    1265  662.35    1300  655.39    1320  656.54    1365  664.21    1395  661.74
    1450  681.06    1475  684.44    1565   679.6 1610.01  670.29 1636.53  668.96
#Mann= 3 , 0 , 0
       0     .06       0  849.03     .04       0 1004.83      .1       0
Bank Sta=849.03,1004.83
XS Rating Curve= 0
Exp/Cntr=0.3,0.1

Type RM Length L Ch R = 1 ,119954.9,480.65,481.08,509.04
XS GIS Cut Line= 3
      1979886.12       298486.94      1980720.78       297963.81
      1981191.01       297581.75
#Sta/Elev= 30
       0  678.25       5  675.69      15  676.94      30  676.57      35  674.71
      50  672.73      90  653.11     125  637.93     160  631.01     235  629.02
     350  631.59     475  631.16     490  632.73     515   628.2     560  628.75
     610  625.92     670  629.03  683.62  628.65     705  625.86     850  626.79
  882.49  639.49    1215  662.06    1260  651.45    1295  658.32    1345  661.81
 1370.01  664.85    1465  682.58    1515  686.05    1545  685.15 1590.93  675.74
#Mann= 3 , 0 , 0
       0     .06       0  683.62     .04       0  882.49      .1       0
Bank Sta=683.62,882.49
XS Rating Curve= 0
Exp/Cntr=0.3,0.1

Type RM Length L Ch R = 1 ,119473.8,572.82,572.79,549.82
XS GIS Cut Line= 2
      1980238.79       298839.62      1981655.37       297910.91
#Sta/Elev= 30
       0  653.57   10.01   651.7   55.01  636.93     100  631.03     130  632.77
  225.01  630.18     355  629.36  415.01   630.6  440.01  627.39  480.01  629.81
  630.01  630.13     670  631.95  700.01  625.94  835.01  627.44     840  628.11
  850.01  635.71  855.01  637.38  867.77  638.35 1195.01  651.84 1250.01  655.74
 1270.01  659.22 1305.01  652.21 1485.01  665.35    1510  662.97 1530.01  662.81
    1615  668.85 1640.01   669.1 1655.01   670.8 1665.01  673.53 1693.87  667.55
#Mann= 3 , 0 , 0
       0     .06       0     670     .04       0  867.77      .1       0
Bank Sta=670,867.77
XS Rating Curve= 0
Exp/Cntr=0.3,0.1

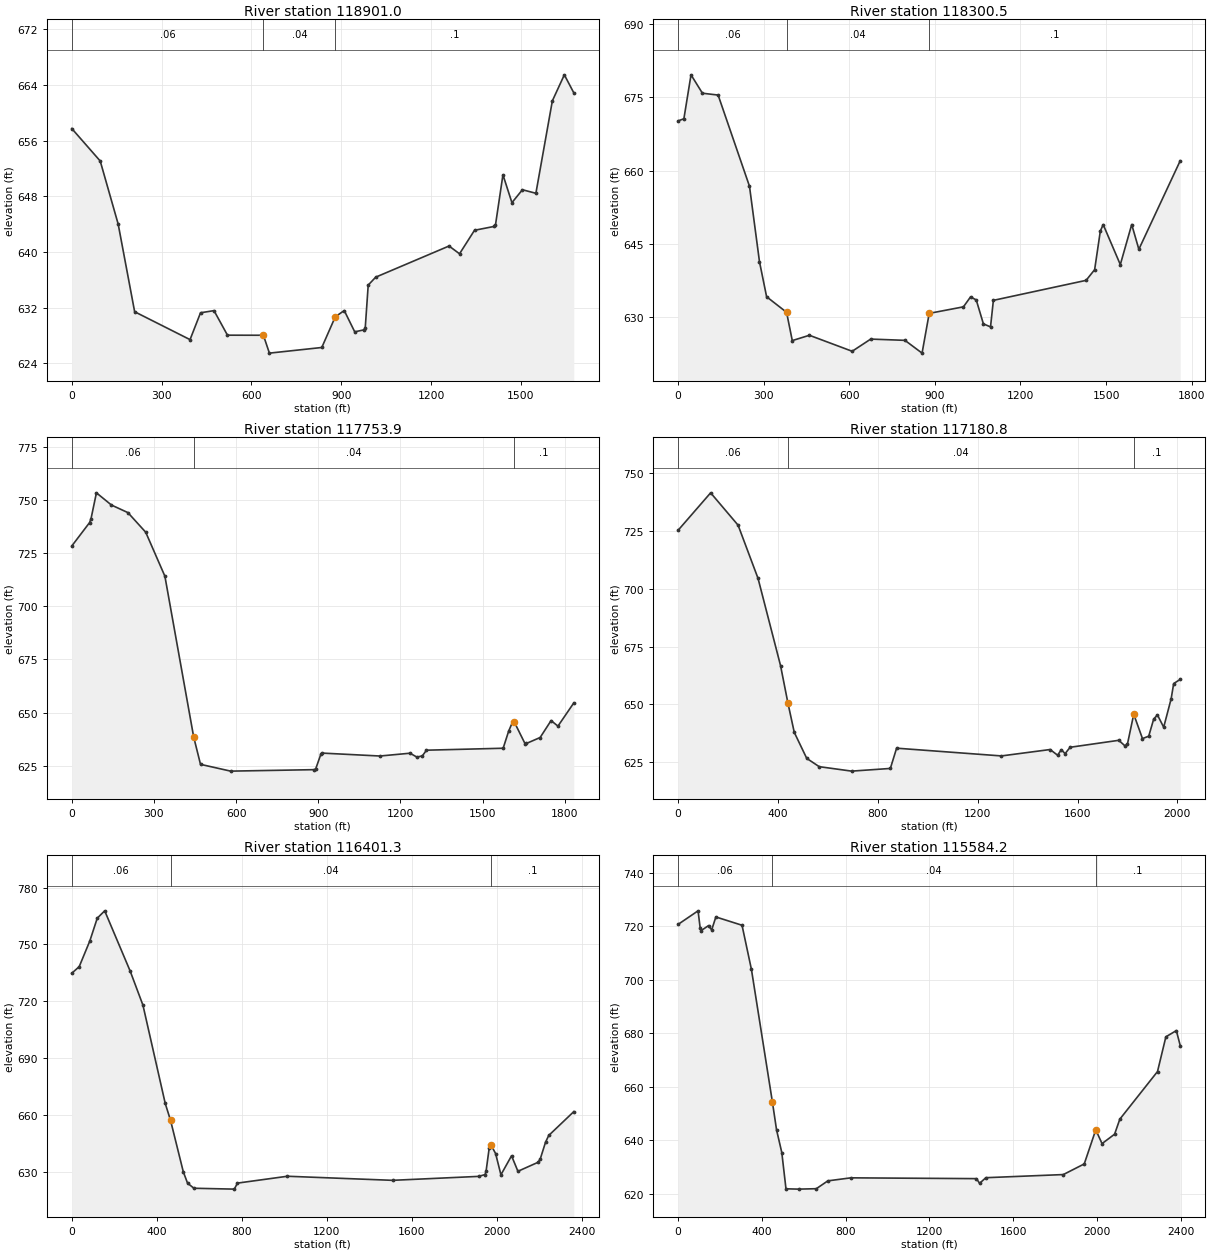
Type RM Length L Ch R = 1 ,118901.0,657.47,600.49,606.85
XS GIS Cut Line= 3
      1980632.61       299262.82      1981373.23       298774.96
      1981925.75       298210.68
#Sta/Elev= 30
       0  657.74      95  653.07     155     644     210   631.4  395.01  627.39
     430  631.25     475  631.56     520  628.03     640  628.02     660  625.45
     835  626.26     880  630.67     910  631.57     945  628.51     975  628.79
     980  629.01  990.01  635.23    1015  636.37    1260  640.85    1295  639.73
    1345  643.11    1410  643.66    1415  643.86    1440  651.09    1470  647.08
    1505  648.94    1550  648.43 1605.01  661.72    1645  665.46  1676.6  662.87
#Mann= 3 , 0 , 0
       0     .06       0     640     .04       0     880      .1       0
Bank Sta=640,880
XS Rating Curve= 0
Exp/Cntr=0.3,0.1

Type RM Length L Ch R = 1 ,118300.5,520.94,546.6,459.51
XS GIS Cut Line= 3
      1981155.75       299697.79      1981843.46       299139.39
        1982369.         298471.
#Sta/Elev= 30
       0  670.18      20  670.61      45  679.62      85  675.85     140  675.47
     250  656.77     285  641.31     310  634.12     380  630.93     400  625.13
     460  626.22     610  622.94     675  625.44     795  625.18     855  622.56
  879.99  630.71    1000  632.05 1024.99  634.09    1045  633.46    1070  628.56
    1095  627.94    1105  633.38    1430  637.48    1460  639.67 1479.99   647.6
    1490  648.92    1550  640.71    1590  648.93    1615  643.85    1760     662
#Mann= 3 , 0 , 0
       0     .06       0     380     .04       0  879.99      .1       0
Bank Sta=380,879.99
XS Rating Curve= 0
Exp/Cntr=0.3,0.1

Type RM Length L Ch R = 1 ,117753.9,543.22,573.1,586.42
XS GIS Cut Line= 4
       1981499.6       300082.79      1982034.49        299653.7
      1982328.38       299271.64      1982698.69       298719.12
#Sta/Elev= 30
       0  728.39      65  739.41      70  741.05      90  753.42     145  747.66
     205  744.11     270  734.88     340  714.19     445  638.61  470.01  625.66
     580  622.47     885  623.16     890  623.32     910  630.62     915  630.95
    1125  629.58    1235   630.9    1260  629.07 1280.01  629.65    1295  632.32
    1575  633.24    1595  641.26    1610   645.8 1615.01  645.75    1655  635.35
    1660  635.49    1710  638.29    1750  646.26    1775  643.64 1832.89  654.57
#Mann= 3 , 0 , 0
       0     .06       0     445     .04       0 1615.01      .1       0
Bank Sta=445,1615.01
XS Rating Curve= 0
Exp/Cntr=0.3,0.1

Type RM Length L Ch R = 1 ,117180.8,782.54,779.51,923.5
XS GIS Cut Line= 3
      1981828.76       300511.88      1982551.74        299947.6
       1983174.8       299048.28
#Sta/Elev= 30
       0  725.33     130  741.48  240.01  727.49     320  704.47  410.01  666.81
     440  650.41  465.01  637.94  515.01  626.68     565   623.1     695  621.17
     850  622.33  875.01  631.09 1295.01  627.74    1490  630.51 1520.01  628.05
 1535.01  630.45 1550.01  628.72 1570.01  631.48 1765.01  634.49 1790.01  632.08
    1800  632.97 1825.01  645.76    1860  635.24 1885.01  636.27 1905.01   643.7
    1920  645.46 1945.01  640.15 1975.01  652.51 1985.01  659.03 2011.19  660.82
#Mann= 3 , 0 , 0
       0     .06       0     440     .04       0 1825.01      .1       0
Bank Sta=440,1825.01
XS Rating Curve= 0
Exp/Cntr=0.3,0.1

Type RM Length L Ch R = 1 ,116401.3,887.99,817.13,775.89
XS GIS Cut Line= 3
      1982316.63        301117.3      1983257.09       300364.93
        1984002.         299506.
#Sta/Elev= 30
       0  734.86      35  738.33      85  751.87     120  763.87     155  767.73
     275  735.98     335  718.06     440  666.28     465  657.36     525   630.3
     545  624.33     575  621.65     765  621.19     780  624.36    1015  627.97
    1510  625.82    1915   627.9    1945  628.84    1950  630.53    1965  643.01
 1974.64  644.17 1994.99   639.9    2020  628.74    2070  638.75 2100.01  630.58
    2195  635.33    2205  637.03    2230  645.89    2245  649.44    2363     662
#Mann= 3 , 0 , 0
       0     .06       0     465     .04       0 1974.64      .1       0
Bank Sta=465,1974.64
XS Rating Curve= 0
Exp/Cntr=0.3,0.1

Type RM Length L Ch R = 1 ,115584.2,671.15,684.36,731.47
XS GIS Cut Line= 2
      1982933.81       301763.87      1984603.13       300041.64
#Sta/Elev= 30
       0  720.63      95  725.68     105  719.27     110  718.31     145  720.16
     160  718.55     180  723.39     305  720.29     350  703.76     450  654.31
     470  643.81     495  635.36     515   621.8     575  621.68     660  621.84
     715  624.77     825   625.9    1425   625.6    1440  623.85 1470.01  625.95
    1840  627.12    1940   631.1    1995  643.83    2025  638.69    2085  642.21
    2110  647.83    2290  665.62    2330   678.6    2380  680.92 2398.48  675.35
#Mann= 3 , 0 , 0
       0     .06       0     450     .04       0    1995      .1       0
Bank Sta=450,1995
XS Rating Curve= 0
Exp/Cntr=0.3,0.1

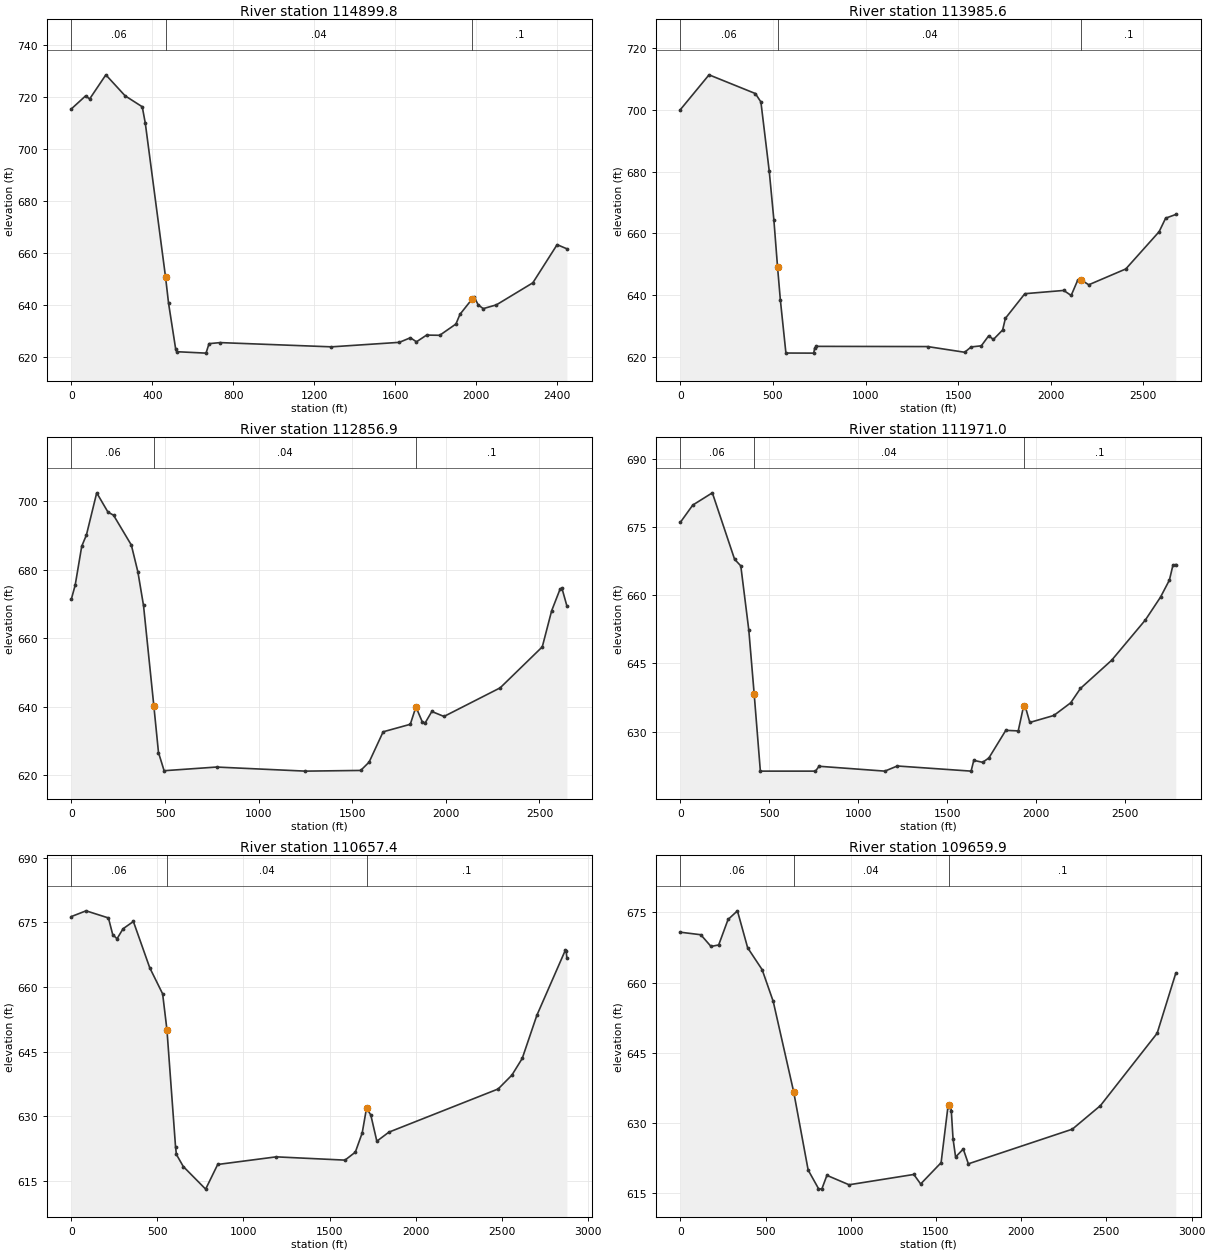
Type RM Length L Ch R = 1 ,114899.8,901.83,914.18,1006.65
XS GIS Cut Line= 2
      1983409.92       302228.22      1985167.41       300523.63
#Sta/Elev= 30
       0  715.49      70  720.47      90  719.29     170  728.57     265  720.51
     350  716.27  364.99  709.95     465  650.75     480  640.62     515  623.08
     520  622.01     665  621.46     680  625.11     735  625.51 1284.99  623.88
    1620  625.61    1675  627.37    1705  625.82    1755   628.4    1820  628.33
    1900  632.67    1920   636.4 1980.71  642.36    1990  643.08    2010  640.03
    2035  638.59 2099.99  640.04 2279.99  648.52    2400  663.21 2448.35  661.61
#Mann= 3 , 0 , 0
       0     .06       0     465     .04       0 1980.71      .1       0
Bank Sta=465,1980.71
XS Rating Curve= 0
Exp/Cntr=0.3,0.1

Type RM Length L Ch R = 1 ,113985.6,1115.1,1128.67,1236.81
XS GIS Cut Line= 2
      1983983.01       302918.87       1985952.1       301108.48
#Sta/Elev= 30
       0  700.02     155  711.29     405  705.24     435  702.52     480  680.15
     505   664.4     525  649.03     540  638.51  570.01  621.33     720   621.3
     725   622.8     735  623.49    1335  623.42    1535  621.58    1570   623.3
    1625  623.67    1665  626.92    1690  625.71    1740  628.78    1755  632.56
    1860  640.52    2070  641.57 2110.01  639.94    2145  644.84 2163.42  644.99
    2205   643.4    2405  648.52    2585  660.58    2620  664.94 2674.85  666.13
#Mann= 3 , 0 , 0
       0     .06       0     525     .04       0 2163.42      .1       0
Bank Sta=525,2163.42
XS Rating Curve= 0
Exp/Cntr=0.3,0.1

Type RM Length L Ch R = 1 ,112856.9,967.42,885.95,879.35
XS GIS Cut Line= 2
      1984888.21       303536.05      1986951.34       301878.48
#Sta/Elev= 30
       0  671.47      20  675.47      55  686.83      80  690.11     135  702.42
  194.99   696.8     225  695.88     320  687.17  354.99  679.32     385  669.53
  439.99  640.31  464.99  626.61     495   621.3     775  622.37 1249.99  621.18
    1545  621.38    1590  623.81 1664.99  632.66    1810  634.85    1840  639.93
    1875  635.44    1890  635.31 1924.99  638.59 1989.99  637.14 2289.99  645.49
    2515  657.45 2564.99  667.98    2610  674.31    2620  674.58 2646.52  669.39
#Mann= 3 , 0 , 0
       0     .06       0  439.99     .04       0    1840      .1       0
Bank Sta=439.99,1840
XS Rating Curve= 0
Exp/Cntr=0.3,0.1

Type RM Length L Ch R = 1 ,111971.0,1123.83,1313.57,1116.57
XS GIS Cut Line= 3
      1985537.71       304273.72      1986460.54       303227.46
      1987630.24       302475.09
#Sta/Elev= 30
       0  676.02      70  679.83     180  682.52  304.99  667.91     340  666.45
     385  652.34     415  638.37     450   621.3     760   621.3     780  622.37
    1150   621.3    1220  622.43 1634.99   621.3    1650  623.67    1700  623.24
    1735   624.2    1830  630.27    1900  630.15    1930  635.58    1940  635.46
    1965  632.01    2100  633.54    2195  636.33 2249.99   639.5    2425  645.68
 2614.99  654.56    2700  659.58    2750  663.33    2770  666.63 2785.87  666.75
#Mann= 3 , 0 , 0
       0     .06       0     415     .04       0    1930      .1       0
Bank Sta=415,1930
XS Rating Curve= 0
Exp/Cntr=0.3,0.1

Type RM Length L Ch R = 1 ,110657.4,1070.91,997.52,929.31
XS GIS Cut Line= 2
      1986342.98       305031.97      1988476.66       303098.15
#Sta/Elev= 30
       0  676.38      85   677.7     215  676.05     240  672.17     265  671.22
     300  673.54     360  675.23     455   664.5     530  658.44     555  650.12
     605  622.96  610.01  621.17     650  618.37     780  613.12  850.01  618.84
    1190  620.61    1590  619.85    1650   621.7    1690  626.17    1715   631.9
    1740  630.31    1775  624.24 1845.01  626.34    2480  636.36    2560  639.58
    2620  643.45    2705  653.45    2870  668.51    2875  668.49 2879.63  666.67
#Mann= 3 , 0 , 0
       0     .06       0     555     .04       0    1715      .1       0
Bank Sta=555,1715
XS Rating Curve= 0
Exp/Cntr=0.3,0.1

Type RM Length L Ch R = 1 ,109659.9,1058.87,1059.82,1098.85
XS GIS Cut Line= 3
      1987160.01       305713.81      1987724.29        305131.9
        1989170.         303638.
#Sta/Elev= 30
       0  670.74     120   670.2     180   667.7     225  668.02     280  673.45
     335   675.3     395  667.42     480  662.75     545  655.98  665.01  636.69
     750     620  810.57  616.05     830  615.93     860  618.87     990  616.86
    1370  619.06    1410  617.03    1530  621.57    1570  633.46    1575  633.87
    1585  633.93 1590.01  632.57    1600  626.69    1615  622.78 1660.01  624.49
    1690  621.33    2300  628.72    2465  633.75 2797.56  649.18    2907     662
#Mann= 3 , 0 , 0
       0     .06       0  665.01     .04       0    1575      .1       0
Bank Sta=665.01,1575
XS Rating Curve= 0
Exp/Cntr=0.3,0.1

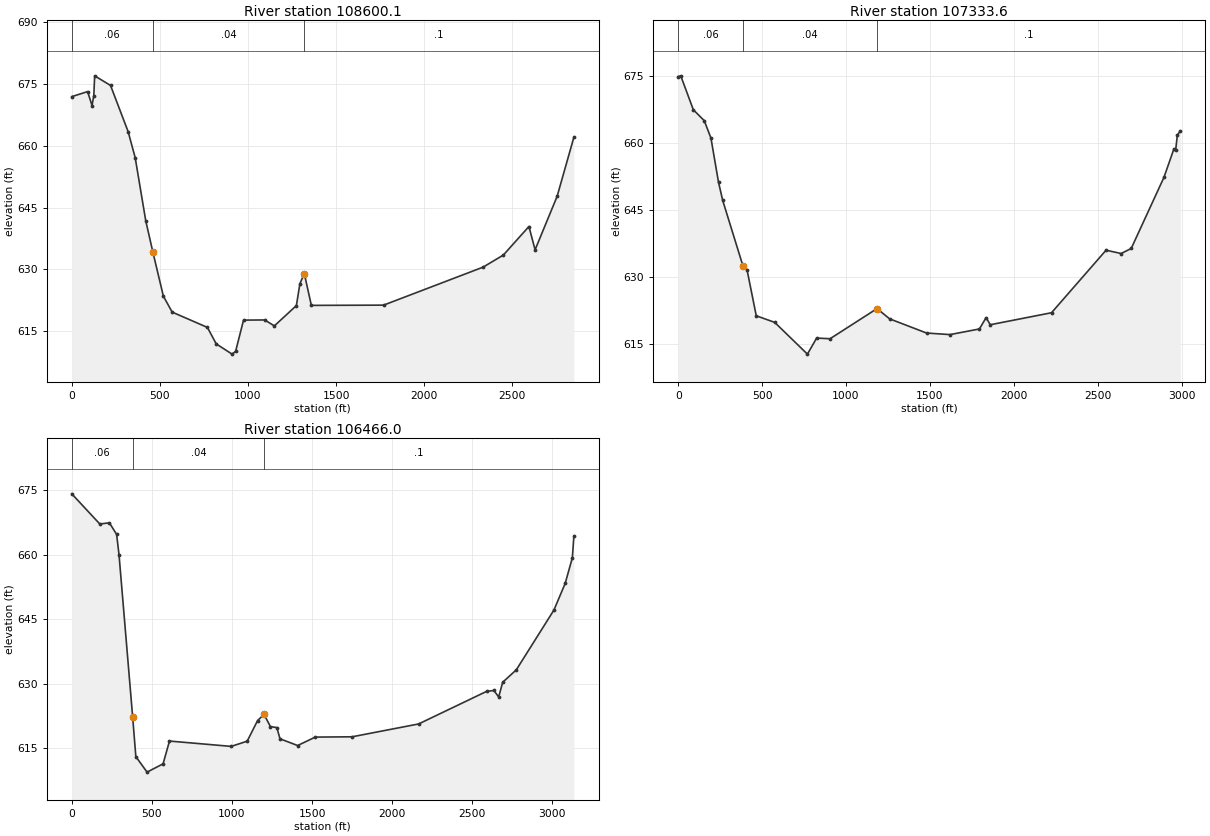
Type RM Length L Ch R = 1 ,108600.1,1299.23,1266.45,1255.15
XS GIS Cut Line= 2
      1988009.36       306292.78        1990080.         304330.
#Sta/Elev= 30
       0  671.88      90   673.1     115  669.71     125  672.11     130  676.92
     220  674.59     320  663.39     360  657.09     420  641.79     460  634.28
  520.01  623.53     570  619.67     770  615.96     820  611.97     910  609.49
     930  610.16  975.01  617.73 1095.01  617.77    1150  616.33    1275  621.25
    1295  626.56 1320.01  629.01    1360   621.3 1770.01  621.36 2335.01  630.57
 2450.01   633.5    2595  640.41 2630.01  634.77 2755.01  647.71    2850     662
#Mann= 3 , 0 , 0
       0     .06       0     460     .04       0 1320.01      .1       0
Bank Sta=460,1320.01
XS Rating Curve= 0
Exp/Cntr=0.3,0.1

Type RM Length L Ch R = 1 ,107333.6,826.39,867.68,932.05
XS GIS Cut Line= 2
      1988949.83       307174.46       1991083.5       305076.06
#Sta/Elev= 30
       0  674.91   14.99  675.07   89.99  667.46     155  665.02     195  661.11
  239.99  651.22     265  647.14  384.99  632.54  409.99   631.6     465  621.27
     575  619.79     770  612.67     825  616.27  904.99  616.12    1185  622.88
    1260  620.58    1480   617.4    1620  617.05    1795  618.31    1835  620.85
    1860  619.26    2225  621.95 2549.99  635.97    2640  635.23    2700  636.36
    2895  652.29    2955  658.74    2965  658.41    2975  661.79 2992.63   662.7
#Mann= 3 , 0 , 0
       0     .06       0  384.99     .04       0    1185      .1       0
Bank Sta=384.99,1185
XS Rating Curve= 0
Exp/Cntr=0.3,0.1

Type RM Length L Ch R = 1 ,106466.0,1160.36,1287.33,1476.96
XS GIS Cut Line= 2
      1989481.78       307782.82      1991856.44       305737.32
#Sta/Elev= 30
       0  674.15     175  667.14     235  667.41     280  664.72  294.99  659.98
  379.99  622.33  399.99  613.09     470  609.48     570  611.41  609.99   616.7
  994.99  615.46 1094.99  616.67 1159.99  621.46    1200  622.91 1239.99  620.07
    1280  619.83 1299.99  617.22 1409.99  615.66 1519.99  617.62 1749.99  617.69
 2164.99  620.67 2589.99  628.25    2635  628.45    2665  626.95 2689.99  630.36
    2775  633.25 3009.99  647.15 3079.99  653.32 3124.99   659.3 3134.18  664.24
#Mann= 3 , 0 , 0
       0     .06       0  379.99     .04       0    1200      .1       0
Bank Sta=379.99,1200
XS Rating Curve= 0
Exp/Cntr=0.3,0.1