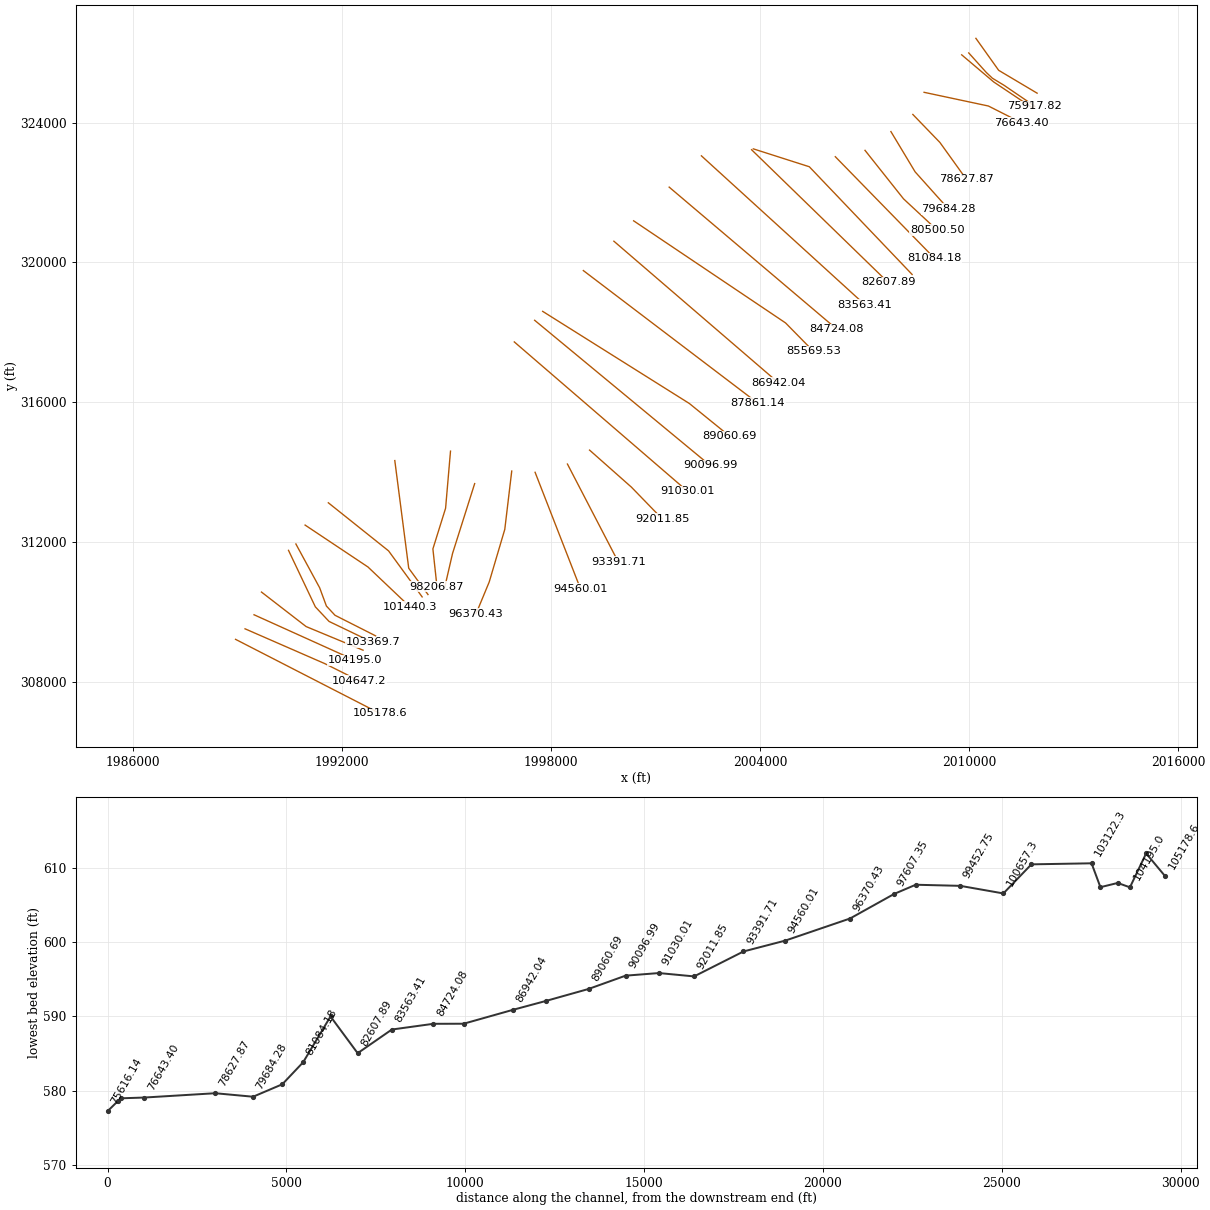
HEC-RAS study BaldEagle.prj: Bald Eagle Cr. for the WCDS Project

--- BaldEagle.g01 (geometry) --- (continued)

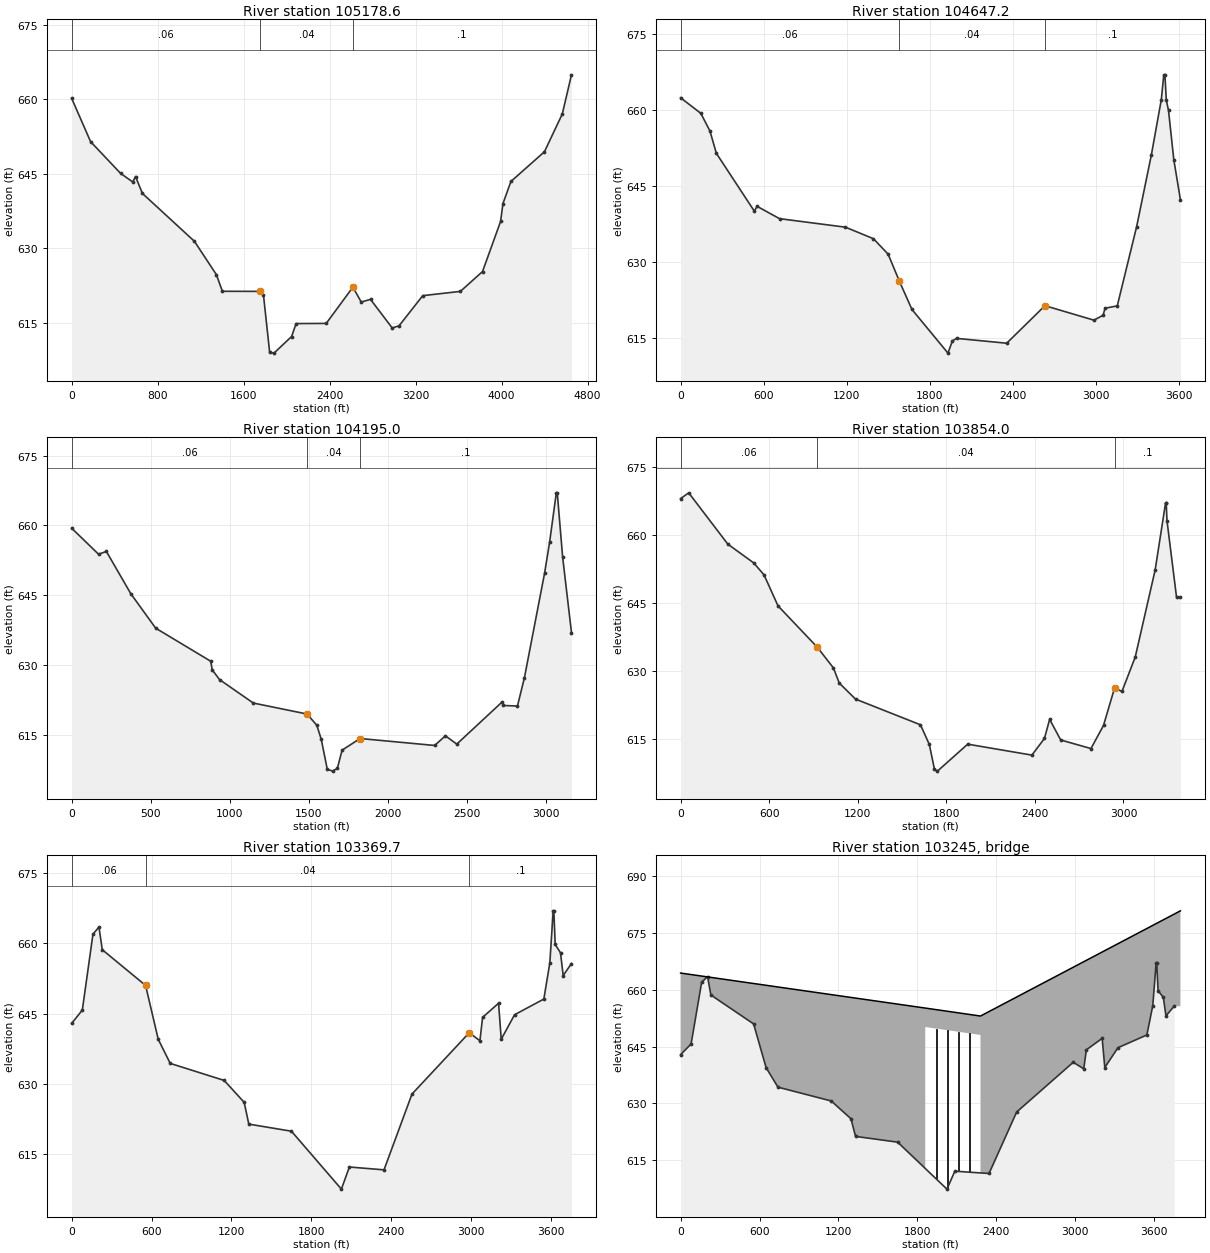
Type RM Length L Ch R = 1 ,105178.6,511.24,531.4,560.31
XS GIS Cut Line= 2
      1988945.95       309213.35      1993084.92       307095.11
#Sta/Elev= 30
       0  660.23     176   651.5  455.99  645.08     568  643.37     594  644.46
     658  641.06    1142   631.4    1346  624.69    1402  621.32    1752   621.3
    1784  620.62 1841.99  608.98    1882  608.85 2045.99   612.2    2088  614.81
    2368  614.84 2615.99  622.15    2694  619.15    2780  619.69 2981.99  613.92
    3046  614.37    3266  620.44    3616   621.3    3822   625.3    3990   635.4
    4012     639    4086  643.46    4398  649.46    4564  657.07 4649.52  664.97
#Mann= 3 , 0 , 0
       0     .06       0    1752     .04       0 2615.99      .1       0
Bank Sta=1752,2615.99
XS Rating Curve= 0
Exp/Cntr=0.3,0.1

Type RM Length L Ch R = 1 ,104647.2,452.39,452.23,468.16
XS GIS Cut Line= 3
      1989218.58       309514.68      1991509.65       308517.56
      1992503.01       308023.82
#Sta/Elev= 30
       0  662.46     146  659.38  212.01  655.87  257.99  651.47     532  640.02
     552  640.97     714  638.53    1190  636.84    1392  634.56    1498   631.5
    1580   626.1    1670  620.55    1930  611.91    1962  614.33    1992  614.83
    2354  613.87    2630   621.3    2984  618.43    3050  619.42    3064   620.8
 3151.99  621.26    3292  636.96 3397.99  651.11    3470  662.09    3488     667
    3496     667    3506  661.98    3522  659.94    3560  650.23 3607.95  642.28
#Mann= 3 , 0 , 0
       0     .06       0    1580     .04       0    2630      .1       0
Levee=0,,,-1,3488,,0,0
Bank Sta=1580,2630
XS Rating Curve= 0
Exp/Cntr=0.3,0.1

Type RM Length L Ch R = 1 ,104195.0,312.92,341.04,357.86
XS GIS Cut Line= 2
      1989476.86       309916.45      1992361.94       308617.49
#Sta/Elev= 30
       0  659.42     170  653.85     220  654.43     374   645.4     532  637.99
     880  630.91     890  629.05     936  626.97    1150  621.94    1490  619.59
    1552  617.18    1580  614.17    1618  607.76    1652  607.35    1682  607.95
    1712  611.85    1826  614.34    2298  612.85    2366  614.92    2438  613.14
    2726  622.21    2732  621.42    2822   621.3 2866.01  627.36    2994  649.82
    3026  656.53    3068     667    3074     667    3108  653.22 3164.01  637.06
#Mann= 3 , 0 , 0
       0     .06       0    1490     .04       0    1826      .1       0
Levee=0,,,-1,3068,,0,0
Bank Sta=1490,1826
XS Rating Curve= 0
Exp/Cntr=0.3,0.1

Type RM Length L Ch R = 1 ,103854.0,2158.97,484.25,341.75
XS GIS Cut Line= 3
      1989690.44       310566.01      1990971.82       309578.52
      1992605.87       308902.56
#Sta/Elev= 30
       0  668.06   55.01  669.33  320.01  658.01     495  653.88  565.01  651.24
  660.01  644.39  925.01  635.31    1035  630.72    1075  627.36    1185  623.83
 1625.01  618.16    1685  613.82    1720  608.31    1740  607.94    1945  613.89
 2380.01  611.47    2465  615.16 2500.01  619.36 2575.01  614.81    2780  612.92
 2865.01  618.02    2940  626.29    2990  625.52 3080.01  633.11    3215  652.33
    3285     667    3290     667    3295  663.21 3360.01  646.25 3386.08  646.36
#Mann= 3 , 0 , 0
       0     .06       0  925.01     .04       0    2940      .1       0
Levee=0,,,-1,3285,,0,0
Bank Sta=925.01,2940
XS Rating Curve= 0
Exp/Cntr=0.3,0.1

Type RM Length L Ch R = 1 ,103369.7,332.28,247.45,218.78
XS GIS Cut Line= 4
      1990466.32       311759.22      1991236.33        310142.8
      1991630.15       309725.47      1992882.14       309125.92
#Sta/Elev= 30
       0  642.88   80.01  645.73     160  662.01     205  663.52  230.01  658.66
  555.01  651.02     650  639.47     740  634.31    1145  630.66    1295  625.97
    1330   621.3    1650  619.78    2025  607.37    2085  612.11    2345   611.5
    2555  627.74    2985  640.88    3065  639.16 3084.99  644.17 3204.99   647.2
    3225  639.49 3324.99  644.73    3545   648.1    3590  655.88    3615     667
    3620     667    3630   659.8    3670  658.01    3690  653.14  3752.4  655.71
#Mann= 3 , 0 , 0
       0     .06       0  555.01     .04       0    2985      .1       0
Levee=-1,205,,-1,3615,,0,0
Bank Sta=555.01,2985
XS Rating Curve= 0
Exp/Cntr=0.3,0.1

Type RM Length L Ch R = 3 ,103245  ,,,
Bridge Culvert-0,0,-1,-1, 0
Deck Dist Width WeirC Skew NumUp NumDn MinLoCord MaxHiCord MaxSubmerge Is_Ogee
100,42,2.6,0, 6, 6, , , 0.95, 0, 2,2,,
       0    1860    1860    2280    2280    3800
  664.46  655.21  655.21   653.1   653.1   680.9
     600     600  650.21   648.1     600     600
       0    1860    1860    2280    2280    3800
  664.46  655.21  655.21   653.1   653.1   680.9
     600     600  650.21   648.1     600     600
Pier Skew, UpSta & Num, DnSta & Num=  ,1943.5, 4 ,1943.5, 4 , 0 , 0 , 0 ,,
       8       8       6       6
     600     620     620     653
       8       8       6       6
     600     620     620     653
Pier Skew, UpSta & Num, DnSta & Num=  ,2028, 4 ,2028, 4 , 0 , 0 , 0 ,,
       8       8       6       6
     600     620     620     653
       8       8       6       6
     600     620     620     653
Pier Skew, UpSta & Num, DnSta & Num=  ,2112.5, 4 ,2112.5, 4 , 0 , 0 , 0 ,,
       8       8       6       6
     600     620     620     653
       8       8       6       6
     600     620     620     653
Pier Skew, UpSta & Num, DnSta & Num=  ,2197, 4 ,2197, 4 , 0 , 0 , 0 ,,
       8       8       6       6
     600     620     620     653
       8       8       6       6
     600     620     620     653
Abutment Skew #Up #Dn= , 2 , 2
  1859.9    1939
     650   611.7
  1859.9    1939
     650   611.7
Abutment Skew #Up #Dn= , 2 , 2
    2201  2280.1
   611.5     648
    2201  2280.1
   611.5     648
BR Coef=-1 , 0 , 0 ,, 0 ,,,0.8,-1,,1,
WSPro=,,,, 1 ,,,, 0 ,,,, 0 ,,,,-1 ,-1 ,-1 , 0 , 0 , 0 , 0 , 0
BC Design=,, 0 ,, 0 ,,,,,,
BC HTab HWMax=665

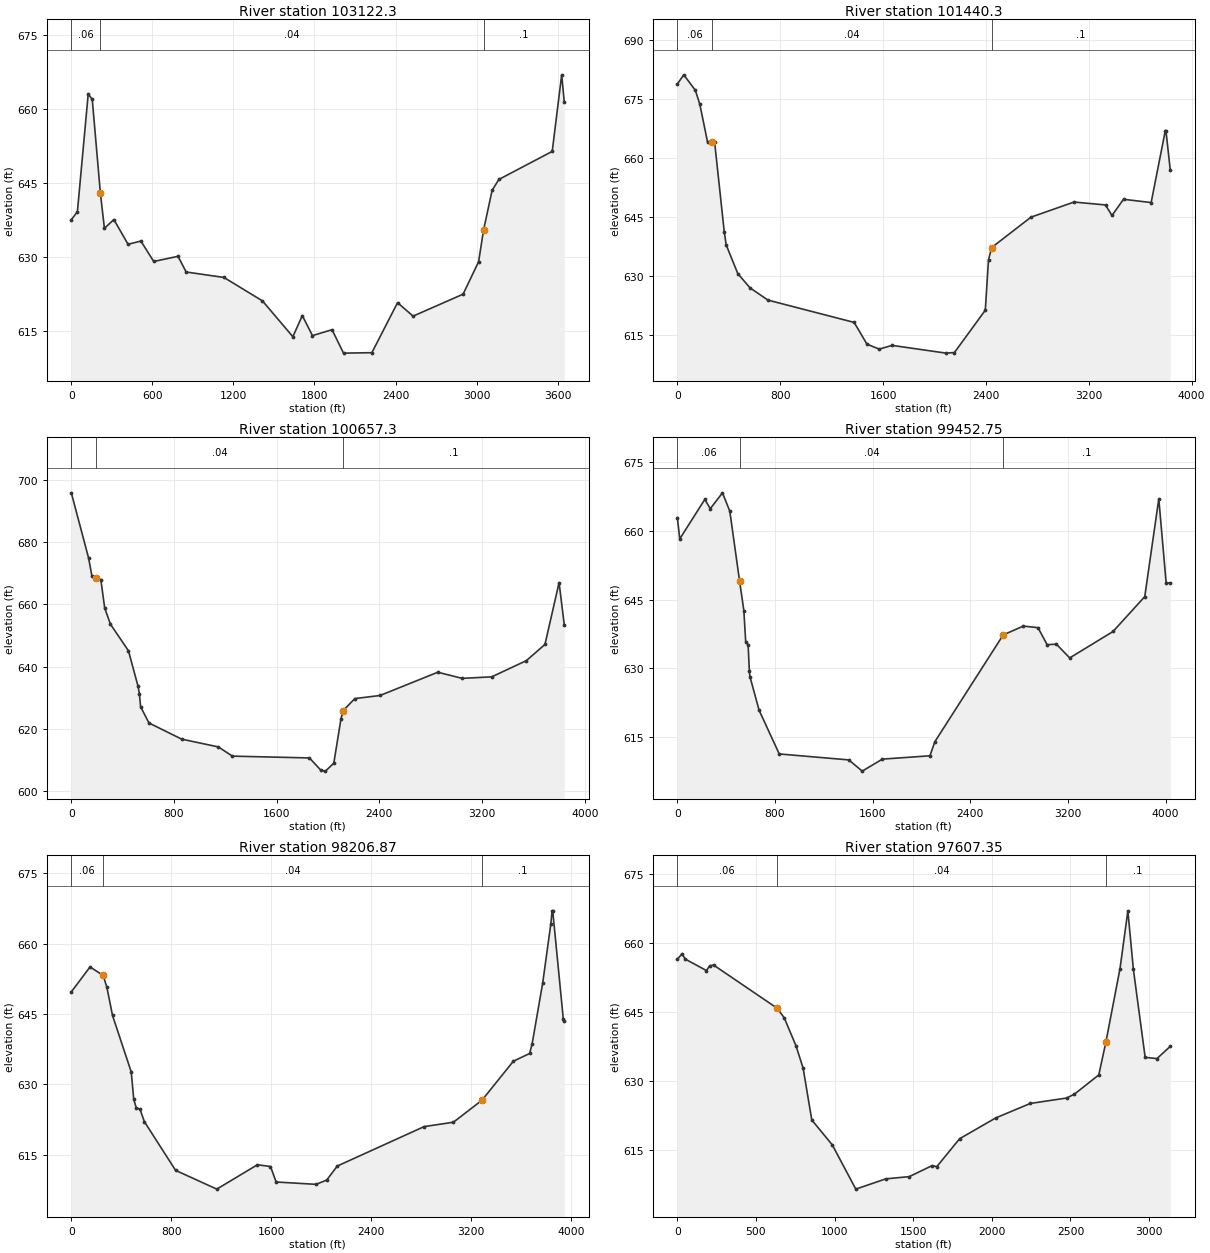
Type RM Length L Ch R = 1 ,103122.3,642.29,1681.95,1583.29
XS GIS Cut Line= 5
      1990677.93       311941.43      1991359.76       310689.44
      1991553.73       310166.31       1991800.6        309901.8
      1992964.43       309314.01
#Sta/Elev= 30
       0  637.64      45  639.23  124.99  663.09     155  662.03     215  643.07
     245  635.88  314.99  637.66     420  632.65     515   633.3     610  629.16
  789.99  630.21     850  627.03    1130  625.92    1415  621.17 1639.99  613.91
 1709.99  618.19    1785  614.13    1930  615.33 2014.99  610.58    2225  610.67
    2415  620.81 2529.99  618.08    2900  622.53    3015  629.11 3051.83  635.55
    3115  643.58    3165  645.79    3560  651.48    3630     667  3649.2  661.48
#Mann= 3 , 0 , 0
       0     .06       0     215     .04       0 3051.83      .1       0
Levee=-1,135,,-1,3630,,0,0
Bank Sta=215,3051.83
XS Rating Curve= 0
Exp/Cntr=0.3,0.1

Type RM Length L Ch R = 1 ,101440.3,896.32,782.97,761.64
XS GIS Cut Line= 3
      1990942.43        312482.2      1992746.94       311283.11
      1993957.79       310136.92
#Sta/Elev= 30
       0  678.87   50.01  681.21  140.01  677.28  175.01   673.7     235  664.09
  267.99  664.25     290  664.06     365  641.25     380  637.95     470  630.68
     565  627.04     705  623.92    1375  618.25 1475.01  612.71 1570.01  611.46
    1670  612.41    2090  610.44    2155  610.59 2395.01  621.35    2420  634.19
    2445   637.3    2750  645.01 3085.01  648.86    3330  648.12    3380  645.44
 3470.01  649.56    3685  648.73    3795     667    3800     667 3833.89  656.93
#Mann= 3 , 0 , 0
       0     .06       0  267.99     .04       0    2445      .1       0
Levee=0,,,-1,3795,,0,0
Bank Sta=267.99,2445
XS Rating Curve= 0
Exp/Cntr=0.3,0.1

Type RM Length L Ch R = 1 ,100657.3,2491.8,1204.64,474.29
XS GIS Cut Line= 3
      1991609.57       313119.95      1993337.67       311744.52
      1994301.65       310427.87
#Sta/Elev= 30
       0   695.8     135  674.81     160  669.21  192.02  668.59     230  667.97
     260  658.86     305  653.66     445  645.15     520  633.73  530.01  631.43
     540  627.17     605  621.97     860  616.79 1145.01   614.3    1255  611.34
 1855.01  610.76    1945  606.79    1980  606.53    2045  609.09    2100   623.1
 2117.25  625.91 2208.65   629.8    2405  630.79 2855.01  638.25    3045  636.29
 3275.01  636.77    3545  641.97    3690  647.17    3800     667 3840.47  653.44
#Mann= 3 , 0 , 0
       0     .06       0  192.02     .04       0 2117.25      .1       0
Levee=0,,,-1,3800,,0,0
Bank Sta=192.02,2117.25
XS Rating Curve= 0
Exp/Cntr=0.3,0.1

Type RM Length L Ch R = 1 ,99452.75,1787.85,1245.88,1320.48
XS GIS Cut Line= 3
      1993516.95       314327.85      1993916.64       311247.84
      1994469.17       310495.47
#Sta/Elev= 30
       0  662.87      20  658.25  224.99  666.86  269.99  664.84     370   668.3
  429.99  664.28  509.99  649.03  544.99   642.6     560  635.82  579.99  635.11
     590  629.46     595  628.16  669.99  620.84  834.99   611.3 1404.99     610
    1515  607.55    1680  610.17 2069.99   610.9    2110  613.97 2669.99  637.28
 2834.99  639.21 2954.99  638.87    3030  635.15 3105.84  635.27    3215  632.26
 3569.99  638.03    3830  645.64    3945     667    4005  648.72  4039.3  648.57
#Mann= 3 , 0 , 0
       0     .06       0  509.99     .04       0 2669.99      .1       0
Levee=0,,,-1,3945,,0,0
Bank Sta=509.99,2669.99
XS Rating Curve= 0
Exp/Cntr=0.3,0.1

Type RM Length L Ch R = 1 ,98206.87,1235.38,599.52,443.7
XS GIS Cut Line= 4
      1995115.73       314598.24      1994974.66       312964.18
      1994610.23       311800.36      1994727.79       310718.83
#Sta/Elev= 30
       0  649.73  150.01  655.04     255  653.24  285.01  650.68     330   644.7
     480  632.66     500  626.82     520  625.04     550  624.72     585  622.08
     835   611.7    1165   607.7    1490  612.89    1595  612.52 1640.14  609.22
    1960  608.72    2045  609.63    2130  612.62    2825  621.02    3060  621.96
 3288.34  626.64    3540  634.96 3670.01   636.6    3690  638.63    3775  651.66
    3840  664.23    3850     667    3855     667 3940.01  643.87 3947.58  643.51
#Mann= 3 , 0 , 0
       0     .06       0     255     .04       0 3288.34      .1       0
Levee=0,,,-1,3850,,0,0
Bank Sta=255,3288.34
XS Rating Curve= 0
Exp/Cntr=0.3,0.1

Type RM Length L Ch R = 1 ,97607.35,1136.18,1236.92,1332.86
XS GIS Cut Line= 3
      1995809.32       313669.53      1995174.51       311671.05
       1994939.4       310660.05
#Sta/Elev= 30
       0  656.48      30  657.66   49.99  656.51     185  654.01     205  655.01
     230  655.22     635  645.81     680  643.72     755   637.6     800  632.76
     855  621.51     985  616.11    1135  606.47    1325   608.7    1475  609.19
    1620  611.58    1650  611.36 1794.99  617.43    2025  621.96    2245  625.11
    2475  626.28    2525  627.12    2680  631.31 2724.99   638.4 2814.99  654.42
    2865     667 2899.99  654.28 2974.99  635.13    3050  634.86 3134.86  637.53
#Mann= 3 , 0 , 0
       0     .06       0     635     .04       0 2724.99      .1       0
Levee=0,,,-1,2865,,0,0
Bank Sta=635,2724.99
XS Rating Curve= 0
Exp/Cntr=0.3,0.1

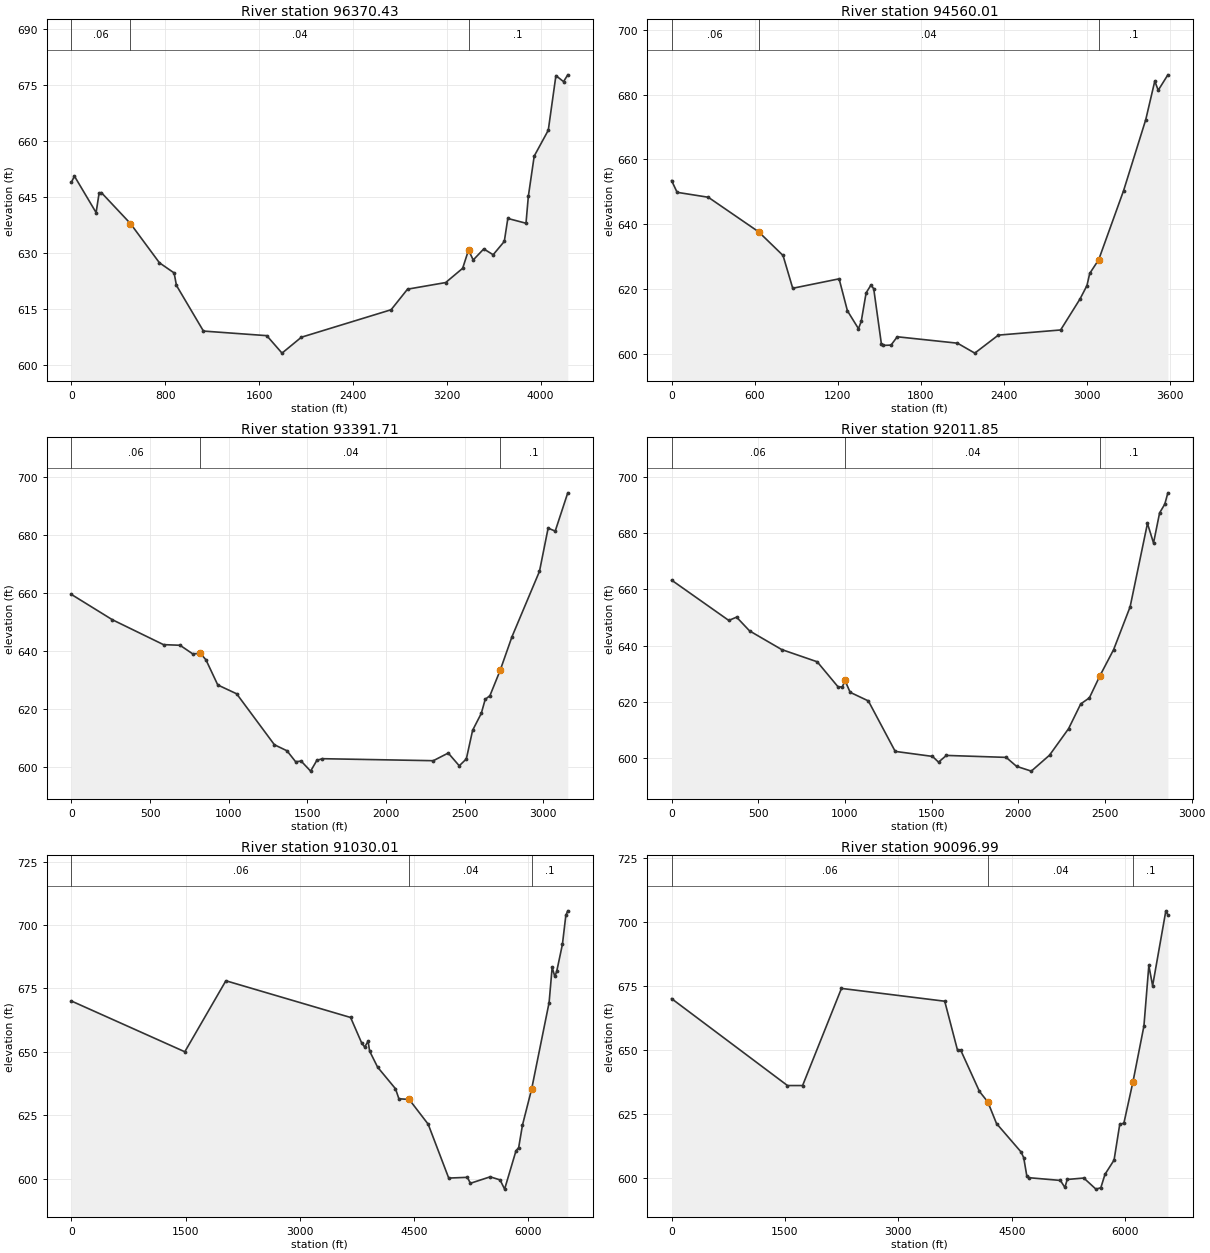
Type RM Length L Ch R = 1 ,96370.43,1063.75,1810.41,2907.95
XS GIS Cut Line= 4
      1996873.22       314028.08      1996673.37       312358.76
      1996226.65       310854.02      1995850.47       309948.83
#Sta/Elev= 30
       0  648.95      25  650.58     210   640.8     235  645.93     255  646.15
  503.08  637.85     750  627.35  874.99  624.64     895  621.29    1125  609.07
 1664.99  607.84 1794.99  603.16    1960  607.42 2724.99  614.78 2864.99  620.29
    3190  622.06    3335  625.88    3385  630.76    3425  628.11 3514.99  631.07
    3595  629.51    3690  633.08    3720  639.23    3875  637.95    3895  645.16
    3945  655.94    4065  662.86    4130  677.49    4195  675.88 4231.14   677.7
#Mann= 3 , 0 , 0
       0     .06       0  503.08     .04       0    3385      .1       0
Bank Sta=503.08,3385
XS Rating Curve= 0
Exp/Cntr=0.3,0.1

Type RM Length L Ch R = 1 ,94560.01,1014.97,1168.31,1286.81
XS GIS Cut Line= 2
       1997543.3       313992.81      1998848.19       310654.17
#Sta/Elev= 30
       0  653.47   39.99  649.84  264.99  648.32  628.74  637.65  804.99  630.34
     875  620.22 1209.99  623.13    1270  613.26    1350  607.73    1370  610.03
    1405  618.79 1439.99  621.21 1459.99  620.07    1515  603.14    1530  602.58
 1584.99  602.67    1630  605.24    2065  603.26 2189.99  600.19    2360  605.75
 2809.99  607.34    2950  616.91    3000  621.04    3020  624.79 3084.89  629.03
 3264.99   650.4 3424.99  672.31 3489.99  684.17 3514.99  681.36 3584.58  686.12
#Mann= 3 , 0 , 0
       0     .06       0  628.74     .04       0 3084.89      .1       0
Bank Sta=628.74,3084.89
XS Rating Curve= 0
Exp/Cntr=0.3,0.1

Type RM Length L Ch R = 1 ,93391.71,937.85,1379.85,1747
XS GIS Cut Line= 2
      1998472.01       314227.93      1999929.73       311430.06
#Sta/Elev= 30
       0  659.54     260  650.84     585  642.27     690  642.06  769.99  639.12
     820  639.25     855  637.03     930  628.39    1050  625.35    1290  607.81
    1370  605.73    1425  601.96    1460  602.19 1519.99  598.73    1560  602.45
    1595  603.01    2300  602.32    2395  604.95    2465  600.57 2509.99  602.92
    2550  612.79 2604.99   618.6    2630  623.44    2660  624.71    2725  633.41
    2800  644.97    2975  667.51    3030  682.38 3074.99  681.35 3154.84  694.53
#Mann= 3 , 0 , 0
       0     .06       0     820     .04       0    2725      .1       0
Bank Sta=820,2725
XS Rating Curve= 0
Exp/Cntr=0.3,0.1

Type RM Length L Ch R = 1 ,92011.85,965.6,981.84,1067.81
XS GIS Cut Line= 3
      1999106.82       314627.63      2000305.91       313569.61
      2001187.59       312664.41
#Sta/Elev= 30
       0  663.23  330.01  648.91     375  650.08     450  645.19     635  638.57
     840  634.22  960.01  625.34     985  625.28    1000  627.61    1030  623.38
    1135  620.32    1290  602.39    1505  600.61    1540  598.57    1585  600.96
    1930  600.26    1990  597.08    2075  595.38 2180.01  601.04 2290.01  610.46
    2360  619.25 2410.01  621.41    2470  629.16 2550.01  638.57 2645.01  653.75
    2745  683.37 2780.01  676.42    2815   687.1 2845.01  690.23 2862.76  694.24
#Mann= 3 , 0 , 0
       0     .06       0    1000     .04       0    2470      .1       0
Bank Sta=1000,2470
XS Rating Curve= 0
Exp/Cntr=0.3,0.1

Type RM Length L Ch R = 1 ,91030.01,851.96,933.02,970.81
XS GIS Cut Line= 2
        1996947.         317722.      2001916.45       313452.05
#Sta/Elev= 30
       0     670    1490     650    2030     678    3670  663.52    3815  653.51
    3855  651.86 3899.99  654.18    3920  650.26    4025  643.94    4260  635.42
    4305  631.47    4440   631.2    4690  621.44    4960  600.19    5205  600.48
    5245  598.13    5505  600.68    5635  599.47 5695.01  595.83    5845  610.99
    5880  612.24    5930  621.12    6050  635.26    6280  669.42    6320  683.28
    6355  679.69 6379.99   681.7    6455  692.36    6500  703.79 6525.36  705.58
#Mann= 3 , 0 , 0
       0     .06       0    4440     .04       0    6050      .1       0
Bank Sta=4440,6050
XS Rating Curve= 0
Exp/Cntr=0.3,0.1

Type RM Length L Ch R = 1 ,90096.99,883.8,1036.3,1017.7
XS GIS Cut Line= 2
       1997530.8        318341.6      2002563.02       314192.66
#Sta/Elev= 30
       0     670    1533     636    1733     636    2247     674    3613  668.99
    3783  649.74 3822.99  649.94    4073  633.68    4183  629.59    4298  621.15
    4623  610.01 4657.99  607.76    4698   600.8    4723  599.96    5143  598.88
    5203  596.12    5233  599.26 5452.99  599.82    5613  595.48    5678  596.02
 5732.99  601.27    5853  606.85 5927.99  620.79    5983   621.3    6103  637.46
    6248  659.28    6313  682.98    6363  675.02    6538  704.35  6564.8  702.72
#Mann= 3 , 0 , 0
       0     .06       0    4183     .04       0    6103      .1       0
Bank Sta=4183,6103
XS Rating Curve= 0
Exp/Cntr=0.3,0.1

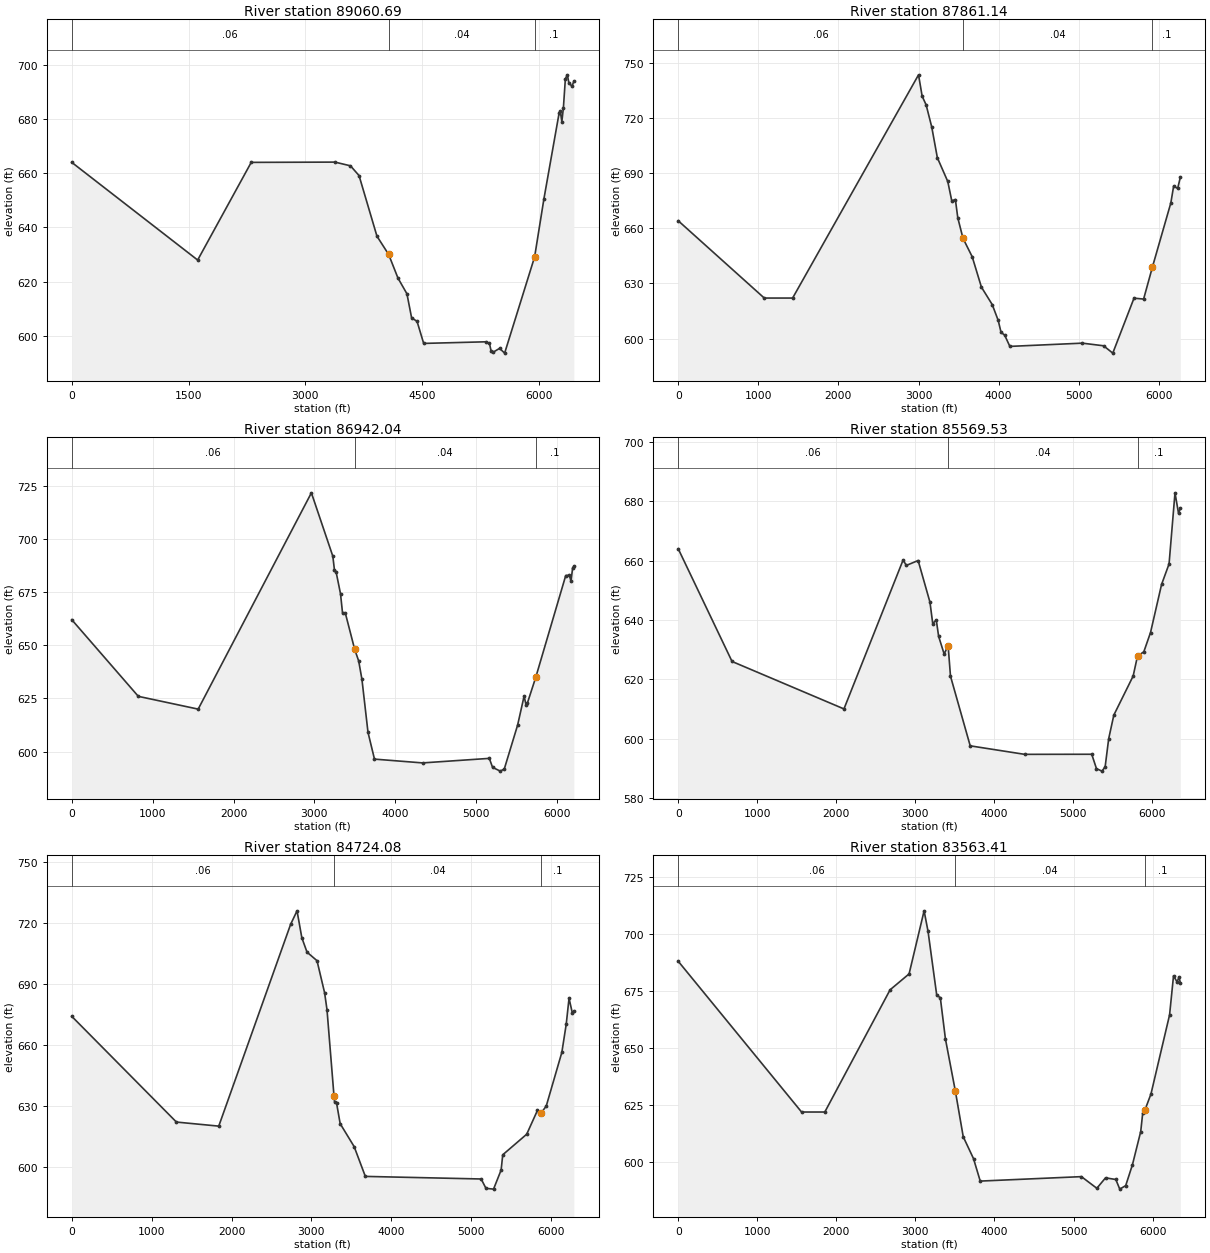
Type RM Length L Ch R = 1 ,89060.69,1310.91,1199.54,1232.22
XS GIS Cut Line= 3
        1997761.         318597.      2001969.35       315961.91
      2003133.18       315021.45
#Sta/Elev= 30
       0     664    1617     628    2305     664    3380   664.1    3580  662.73
 3690.01  659.13 3920.01  636.79    4070  630.07    4190  621.34    4305  615.56
    4365  606.71    4435   605.4    4520  597.27    5325  597.87    5365  597.28
    5385  594.62    5410  593.98 5495.01  595.44    5560  593.69    5945  629.15
    6065  650.62    6260  682.21 6275.01  682.79    6295  679.02 6315.01  684.19
 6340.01  694.79 6365.01  696.27    6385  693.34    6425  692.02 6448.96  693.91
#Mann= 3 , 0 , 0
       0     .06       0    4070     .04       0    5945      .1       0
Bank Sta=4070,5945
XS Rating Curve= 0
Exp/Cntr=0.3,0.1

Type RM Length L Ch R = 1 ,87861.14,1007.46,919.11,855.44
XS GIS Cut Line= 2
        1998928.         319764.      2003932.57       315973.66
#Sta/Elev= 30
       0     664    1074     622    1428     622    3000  743.31    3045  731.73
 3094.99  726.96 3164.99  714.92    3235  698.25    3365  685.35 3414.99  674.81
    3460  675.54    3490  665.62    3555  654.47    3670  644.45    3785  627.95
    3920  618.46    3995  609.81    4030  603.36    4075  601.87 4139.99  595.73
 5044.99  597.49    5310  596.06    5425  592.07    5690  621.93    5810  621.45
    5920  638.86    6150  673.72    6185  682.88    6235  681.56 6268.13  687.57
#Mann= 3 , 0 , 0
       0     .06       0    3555     .04       0    5920      .1       0
Bank Sta=3555,5920
XS Rating Curve= 0
Exp/Cntr=0.3,0.1

Type RM Length L Ch R = 1 ,86942.04,1232.87,1372.51,1427.32
XS GIS Cut Line= 2
        1999805.         320604.      2004532.11        316549.7
#Sta/Elev= 30
       0     662     823     626    1563     620    2963  721.59 3228.01  691.82
    3248  685.36 3268.01  684.51    3323  674.19    3348  665.16    3383  665.04
    3498   648.1    3548  642.57 3588.01  633.96 3663.01  609.08    3743  596.52
    4338  594.74    5163  596.87 5203.01  592.67    5298  590.88    5348  591.87
 5513.01  612.51 5593.01  626.08 5618.01  621.87    5633  622.74 5738.01  635.04
 6108.01  682.75    6153  682.88 6173.01  680.05    6193  686.31 6208.21  687.08
#Mann= 3 , 0 , 0
       0     .06       0    3498     .04       0 5738.01      .1       0
Bank Sta=3498,5738.01
XS Rating Curve= 0
Exp/Cntr=0.3,0.1

Type RM Length L Ch R = 1 ,85569.53,959.38,845.46,899.31
XS GIS Cut Line= 3
        2000372.         321187.      2004731.96       318266.04
      2005531.35       317454.89
#Sta/Elev= 30
       0     664     682     626    2100     610    2850  660.25    2890  658.39
    3040  660.05    3190     646    3225  638.78    3270  639.99    3300  634.45
 3370.01   628.5    3420  631.38    3450  621.06    3700  597.55    4390  594.68
    5240  594.71    5300  589.86    5370  589.02    5410  590.49    5455  599.98
    5520  607.92    5765   621.1    5820  627.84    5900  629.26    5985  635.77
    6125  651.98    6220  658.91    6295  682.88    6340  675.96 6362.47  677.71
#Mann= 3 , 0 , 0
       0     .06       0    3420     .04       0    5820      .1       0
Bank Sta=3420,5820
XS Rating Curve= 0
Exp/Cntr=0.3,0.1

Type RM Length L Ch R = 1 ,84724.08,1232.52,1160.67,1084.14
XS GIS Cut Line= 2
        2001392.         322151.      2006207.31       318083.83
#Sta/Elev= 30
       0     674    1310     622    1840     620    2740  719.29    2820  725.91
    2880  712.67 2945.01  705.58 3070.01  701.38    3165  685.62    3195   677.3
 3283.13  634.62 3290.01  631.87    3315  631.29 3360.01  621.21 3535.01  609.92
    3675  595.27 5125.01     594 5185.01   589.4    5280  589.01    5375  598.42
 5395.01   605.9    5695  616.02    5830  627.77 5875.39  626.41    5940  629.91
    6135  656.28    6190  670.18    6225  682.88    6265  675.89 6285.22  676.59
#Mann= 3 , 0 , 0
       0     .06       0 3283.13     .04       0 5875.39      .1       0
Bank Sta=3283.13,5875.39
XS Rating Curve= 0
Exp/Cntr=0.3,0.1

Type RM Length L Ch R = 1 ,83563.41,975.64,955.53,938.52
XS GIS Cut Line= 2
        2002317.         323046.      2007006.71       318789.17
#Sta/Elev= 30
       0     688    1560     622    1854     622    2680  675.52 2920.01  682.47
    3110  710.09    3160  701.07    3270  673.09    3315  672.08    3380  653.95
 3505.01  631.23 3605.01  611.17    3735  601.59    3820  591.76    5100  593.71
 5295.01  588.61    5405  593.18    5535  592.46 5585.01  588.24    5660  589.78
    5745  598.88 5850.01  613.44    5875  621.44 5904.47  622.97    5980  629.94
    6215  664.51 6265.01  681.65 6310.01  678.94 6335.01  681.16 6350.85   678.5
#Mann= 3 , 0 , 0
       0     .06       0 3505.01     .04       0 5904.47      .1       0
Bank Sta=3505.01,5904.47
XS Rating Curve= 0
Exp/Cntr=0.3,0.1

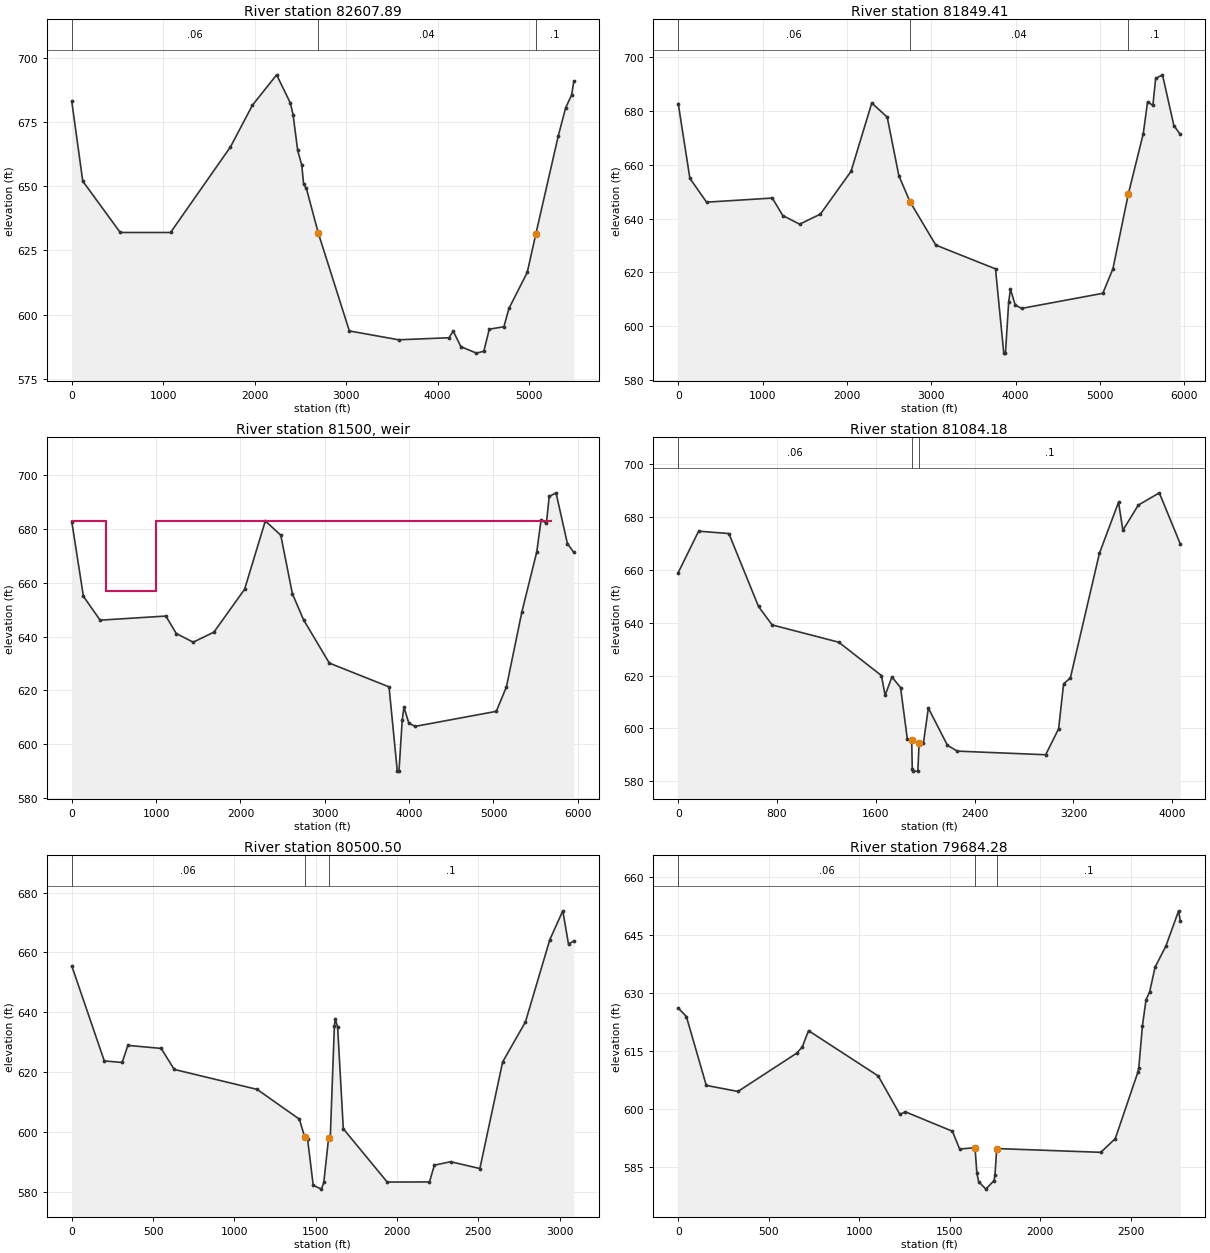
Type RM Length L Ch R = 1 ,82607.89,880.87,758.48,735.33
XS GIS Cut Line= 2
       2003757.3        323220.8      2007676.78       319423.98
#Sta/Elev= 30
       0     683     120     652     530     632    1080     632    1735   665.3
 1975.01  681.52    2240  693.35    2390  682.37    2420  677.78    2470  663.94
    2515   658.2    2535  650.68    2565  649.17 2695.01  631.83    3035  593.69
 3575.01  590.25    4125  591.05    4170  593.67    4255  587.56 4425.01  585.06
 4505.01  585.81    4565  594.37    4725  595.34    4780  602.46    4980  616.47
    5075   631.6 5320.01   669.7    5400  680.52    5465  685.52 5489.49  690.87
#Mann= 3 , 0 , 0
       0     .06       0 2695.01     .04       0    5075      .1       0
Bank Sta=2695.01,5075
XS Rating Curve= 0
Exp/Cntr=0.3,0.1

Type RM Length L Ch R = 1 ,81849.41,1297.7,765.24,1223.73
Node Photo=dam5.gif
XS GIS Cut Line= 3
       2003806.8       323246.23      2005413.34       322734.52
      2008364.61       319652.35
#Sta/Elev= 30
       0  682.78     138     655  336.01  646.12    1116  647.65    1239  641.16
    1440  637.94 1686.07  641.69    2049  657.59    2295     683 2478.01  677.73
    2616  655.95    2748  646.29    3054  630.17    3762  621.32    3860     590
    3880     590    3918  608.87 3939.01  613.77 3996.01  607.88 4071.01  606.63
    5034  612.23    5154  621.32    5337  649.17    5514  671.56    5565  683.43
    5628  682.08    5661  692.11 5742.01  693.46    5877   674.6 5953.35  671.29
#Mann= 3 , 0 , 0
       0     .06       0    2748     .04       0    5337      .1       0
Bank Sta=2748,5337
XS Rating Curve= 0
Exp/Cntr=0.3,0.1

Type RM Length L Ch R = 5 ,81500   ,,,
Node Photo=dam2.gif
BEGIN DESCRIPTION:
Foster Joseph Sayers Dam and Reservoir
END DESCRIPTION:
IW Pilot Flow=0
#Inline Weir SE= 6
       0     683     400     683     400     657    1000     657    1000     683
    5680     683
IW Dist,WD,Coef,Skew,MaxSub,Min_El,Is_Ogee,SpillHt,DesHd
322,25,3.82,0,0.95,3, 0 ,12,20,3,3,
IW Gate Name Wd,H,Inv,GCoef,Exp_T,Exp_O,Exp_H,Type,WCoef,Is_Ogee,SpillHt,DesHd,#Openings
Gate #1     ,7,15,590,0.65,0,1,0.5, 0 ,3, 0 ,,, 2 ,0,0.8, 0
    3865    3875

Type RM Length L Ch R = 1 ,81084.18,951.81,583.67,923.47
Node Photo=dam6.gif
XS GIS Cut Line= 2
      2006160.29       323021.25      2009005.19       320117.58
#Sta/Elev= 30
       0  658.99     165  674.66  409.99  673.76  649.99  646.15     760  639.18
    1300  632.63    1645  620.02    1675  612.56    1730  619.48    1800  615.49
 1854.99  595.98    1890  595.78    1895  584.54    1900  583.84    1940  583.84
    1950  594.31    1985  594.41    2025  607.72    2180  593.58    2260  591.41
    2975  590.04    3080   599.9    3120  616.87    3175  619.13    3410  666.26
    3565  685.61    3600     675    3725  684.52    3895  689.17 4065.07  669.81
#Mann= 3 , 0 , 0
       0     .06       0    1890     .04       0    1950      .1       0
Levee=0,,,-1,2025,,0,0
Bank Sta=1890,1950
XS Rating Curve= 0
Exp/Cntr=0.3,0.1

Type RM Length L Ch R = 1 ,80500.50,769.87,816.22,812.27
XS GIS Cut Line= 3
      2007012.58       323203.47      2008117.63       321816.29
       2009081.6       320922.85
#Sta/Elev= 30
       0  655.51     200  623.74     310  623.22     345  628.94  550.01  627.92
     630   620.9 1140.01  614.22 1400.01  604.26 1432.15  598.31    1450  597.73
    1485  582.15 1535.01  580.88    1550   583.1 1579.75  598.07 1590.01  598.22
    1615  635.28    1620  637.81    1635  635.12    1670  601.06    1940  583.25
 2200.01  583.28    2230  588.89    2330  590.04    2510  587.76    2650  623.41
 2790.01  636.76    2940  664.26    3020  673.92 3055.01   662.8 3087.86  663.84
#Mann= 3 , 0 , 0
       0     .06       0 1432.15     .04       0 1579.75      .1       0
Levee=0,,,-1,1595,,0,0
Bank Sta=1432.15,1579.75
XS Rating Curve= 0
Exp/Cntr=0.3,0.1

Type RM Length L Ch R = 1 ,79684.28,1129.27,1056.41,1012.84
XS GIS Cut Line= 3
      2007756.12       323740.33      2008450.66       322588.21
      2009406.68       321525.98
#Sta/Elev= 30
       0  626.05      45  623.85     155  606.03  330.01  604.47     655  614.38
  685.01  615.95     720  620.19    1105  608.48    1225  598.54    1255   599.2
    1515  594.18    1555  589.58 1639.99  589.92    1650  583.43    1660  581.13
    1700  579.21    1745  581.43    1750  582.78    1760   589.7    2335  588.73
    2415  592.27    2540  609.47 2545.01  610.59    2565  621.44    2585  628.19
    2605  630.24    2635  636.62    2695   642.1    2765  651.18 2774.37  648.49
#Mann= 3 , 0 , 0
       0     .06       0 1639.99     .04       0    1760      .1       0
Bank Sta=1639.99,1760
XS Rating Curve= 0
Exp/Cntr=0.3,0.1

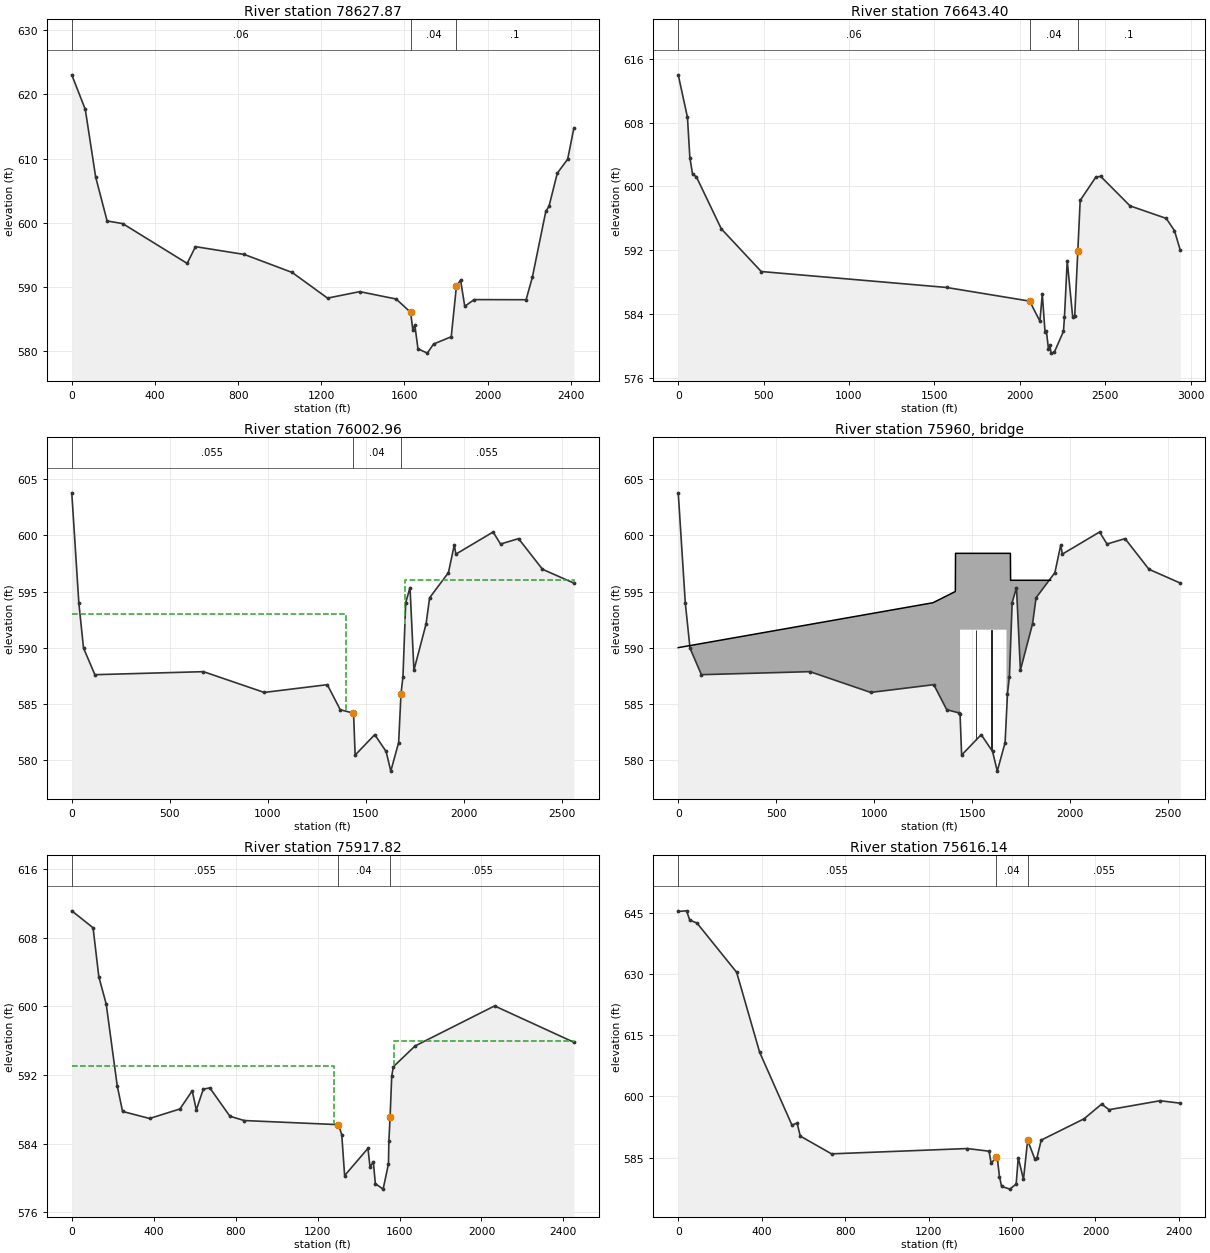
Type RM Length L Ch R = 1 ,78627.87,1630.16,1984.45,2058.18
XS GIS Cut Line= 3
      2008385.29        324230.6      2009161.54       323429.83
      2009921.45       322375.77
#Sta/Elev= 30
       0  623.04   65.01  617.65  115.01   607.1  170.01  600.27  245.01  599.86
     555  593.66     595  596.27     830  595.05 1060.01  592.25 1230.01  588.25
    1385  589.26 1560.01  588.11 1629.67  586.04 1640.01  583.36 1650.01  584.04
 1665.01  580.35    1710  579.68 1740.01   581.1 1825.01  582.23 1850.01  590.12
    1870  591.05 1890.01  586.97    1935  588.02    2185     588 2215.01  591.48
    2280  601.79    2295  602.53    2335  607.71 2385.01   609.9 2414.68  614.72
#Mann= 3 , 0 , 0
       0     .06       0 1629.67     .04       0 1850.01      .1       0
Bank Sta=1629.67,1850.01
XS Rating Curve= 0
Exp/Cntr=0.3,0.1

Type RM Length L Ch R = 1 ,76643.40,907.11,640.44,603.39
XS GIS Cut Line= 3
        2008708.       324863.84      2010554.75       324471.66
      2011494.38       323997.72
#Sta/Elev= 30
       0  613.99      54  608.66      68  603.62      84  601.52     106  601.22
     252  594.69     486  589.33    1572  587.33    2058  585.62 2117.99  583.11
    2132  586.47    2148  581.79    2156  581.88    2168  579.65    2176  580.09
    2184   579.1 2201.99  579.19    2256  581.83    2262  583.67    2278  590.66
    2310  583.65    2322  583.78    2340  591.89    2354  598.25    2446  601.18
    2474  601.26    2646  597.56    2858  595.99    2906  594.46 2940.32  591.99
#Mann= 3 , 0 , 0
       0     .06       0    2058     .04       0    2340      .1       0
Bank Sta=2058,2340
XS Rating Curve= 0
Exp/Cntr=0.3,0.1

Type RM Length L Ch R = 1 ,76002.96,76.32,85.15,89.15
XS GIS Cut Line= 3
      2009787.46       325935.78       2010709.8       325157.45
      2011837.87       324406.55
#Sta/Elev= 30
       0  603.79   36.01  593.99      60  589.96     118  587.59  672.01  587.86
     982  586.01 1304.01   586.7 1370.01  584.47    1434  584.18    1438  584.13
    1446  580.43    1546  582.25    1604  580.75    1628     579    1668  581.55
    1680  585.89 1690.01  587.42    1704  594.01    1726  595.35    1746  587.99
 1808.01  592.12 1826.01  594.44    1922  596.68    1952  599.15 1960.01  598.33
    2150   600.3    2188  599.23    2280  599.71    2402  596.98    2562  595.75
#Mann= 3 , 0 , 0
       0    .055       0    1434     .04       0    1680    .055       0
#XS Ineff= 2 , 0
       0    1400     593    1700       0     596
Permanent Ineff=
       F       F
Bank Sta=1434,1680
XS Rating Curve= 0
Exp/Cntr=0.3,0.1

Type RM Length L Ch R = 3 ,75960   ,,,
Node Photo=xsect2_b.gif
Bridge Culvert-0,0,-1,-1, 0
Deck Dist Width WeirC Skew NumUp NumDn MinLoCord MaxHiCord MaxSubmerge Is_Ogee
30,30,2.6,0, 12, 12, , , 0.95, 0, 2,2,,
       0    1300    1414    1415  1437.9    1438    1675  1675.1    1695    1696
    1760    1900
     590     594     595   598.4   598.4   598.4   598.4   598.4   598.4     596
     596     596
     580     582     582     582     582   591.6   591.6     582     582     582
     582     580
       0    1175    1289    1290  1312.9    1313    1550  1550.1    1570    1571
    1635    1850
     590     594     595   598.4   598.4   598.4   598.4   598.4   598.4     596
     596     596
     580     582     582     582     582   591.6   591.6     582     582     582
     582     580
Pier Skew, UpSta & Num, DnSta & Num=  ,1520, 2 ,1395, 2 , 0 , 0 , 0 ,,
       3       3
     575     599
       3       3
     575     599
Pier Skew, UpSta & Num, DnSta & Num=  ,1600, 2 ,1475, 2 , 0 , 0 , 0 ,,
       4       4
     575     599
       4       4
     575     599
BR Coef=-1 , 0 , 0 ,, 0 ,,,0.8,-1,,1,
WSPro=,,,, 1 ,,,, 0 ,,,, 0 ,,,,-1 ,-1 ,-1 , 0 , 0 , 0 , 0 , 0
BC Design=,, 0 ,, 0 ,,,,,,
BC HTab HWMax=597

Type RM Length L Ch R = 1 ,75917.82,335.8,301.68,321.08
XS GIS Cut Line= 5
      2009989.76       325990.64      2010493.79       325431.75
      2010668.66       325267.17      2011008.11       325061.44
      2011885.88       324464.84
#Sta/Elev= 30
       0  611.14     104  609.16  131.99  603.46     168  600.28     222  590.72
     248  587.74     380  586.92     528  588.03  588.01  590.15     608  587.92
     642  590.34     674  590.49     772  587.18     842  586.68    1302   586.2
    1318  585.03    1332  580.26    1446  583.44    1456  581.25    1472  581.88
    1482  579.32    1520  578.68    1546  581.63    1548  584.24    1554  587.08
    1562   591.9    1570  592.96    1676  595.38    2064  600.05 2450.99  595.81
#Mann= 3 , 0 , 0
       0    .055       0    1302     .04       0    1554    .055       0
#XS Ineff= 2 , 0
       0    1280     593    1575       0     596
Permanent Ineff=
       F       F
Bank Sta=1302,1554
XS Rating Curve= 0
Exp/Cntr=0.3,0.1

Type RM Length L Ch R = 1 ,75616.14,1129.45,965.54,887.98
XS GIS Cut Line= 3
      2010195.18       326408.18      2010848.87       325493.02
      2011951.96       324839.34
#Sta/Elev= 30
       0  645.28      40  645.42      55  643.16   89.99  642.42     280  630.37
     390  610.82     545  592.96     570  593.42     585  590.25     735   585.9
    1385   587.2    1490  586.55    1500   583.6    1525  585.08    1530  584.66
    1540  580.31    1550  577.94    1590  577.26    1620  578.51    1630  584.96
    1655  579.65    1675  589.22    1710  584.55    1720  584.97 1740.01  589.27
 1945.01  594.47    2030   598.1    2065  596.71    2310  598.91 2406.87  598.31
#Mann= 3 , 0 , 0
       0    .055       0    1525     .04       0    1675    .055       0
Bank Sta=1525,1675
XS Rating Curve= 0
Exp/Cntr=0.3,0.1