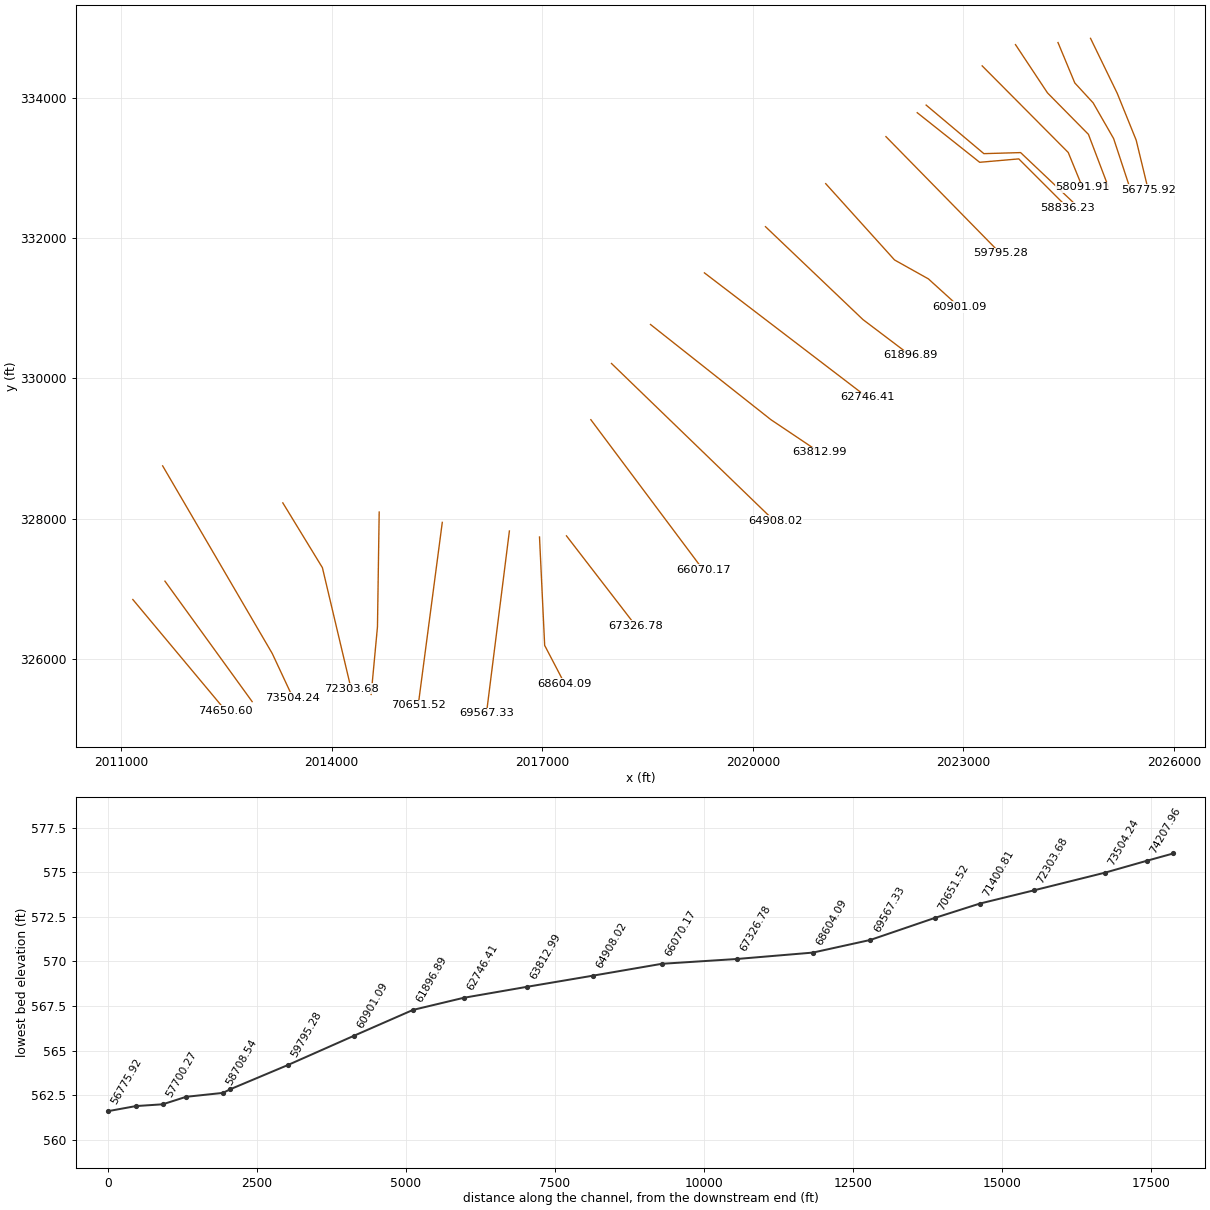
HEC-RAS study BaldEagle.prj: Bald Eagle Cr. for the WCDS Project

--- BaldEagle.g01 (geometry) --- (continued)

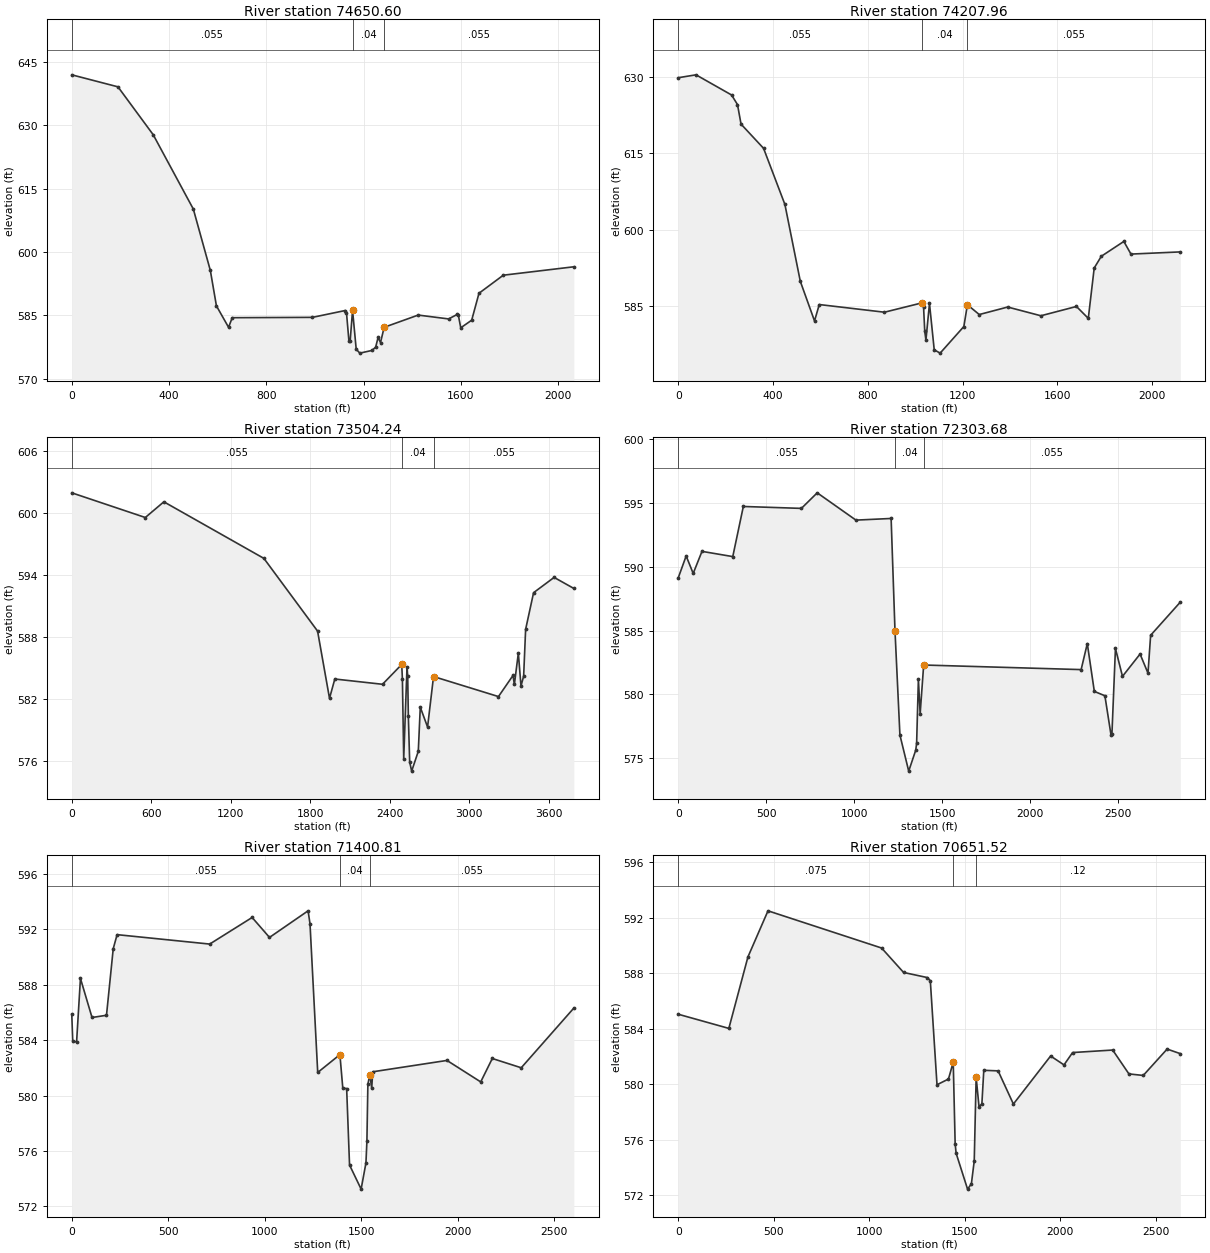
Type RM Length L Ch R = 1 ,74650.60,465.7,442.64,424.42
XS GIS Cut Line= 2
      2011167.54       326849.42      2012491.25       325264.23
#Sta/Elev= 30
       0  641.89     190  639.05     335  627.72     500  610.14     570  595.62
     595  587.25     645  582.17     660  584.45     990  584.53    1125  586.15
    1130  585.65    1140  578.95    1145  578.89    1155  586.18    1170  576.99
    1185  576.07    1235  576.71    1250  577.49    1260  579.77    1270  578.58
    1285  582.18    1425  585.07    1550  584.16    1585  585.21    1590  585.09
    1600  582.06    1645  583.86    1675  590.23    1775   594.5  2065.2  596.49
#Mann= 3 , 0 , 0
       0    .055       0    1155     .04       0    1285    .055       0
Bank Sta=1155,1285
XS Rating Curve= 0
Exp/Cntr=0.3,0.1

Type RM Length L Ch R = 1 ,74207.96,728.06,703.73,676.09
XS GIS Cut Line= 2
      2011625.12       327110.89      2012867.12       325394.97
#Sta/Elev= 30
       0  629.91   74.99  630.48  224.99  626.51  249.99  624.62     265  620.77
     360     616     450  604.95  514.99  589.81     575     582     595  585.23
     870  583.72 1027.56  585.55    1035  584.78    1040  579.98    1045  578.22
 1059.99  585.44    1080  576.31    1105  575.66    1205   580.9    1220  585.19
 1269.99  583.26 1389.99  584.74    1530  583.02 1679.99  584.85    1730  582.51
    1755  592.43    1785  594.74    1880  597.66    1910  595.17 2118.24   595.6
#Mann= 3 , 0 , 0
       0    .055       0 1027.56     .04       0    1220    .055       0
Bank Sta=1027.56,1220
XS Rating Curve= 0
Exp/Cntr=0.3,0.1

Type RM Length L Ch R = 1 ,73504.24,1245.18,1200.55,1071.32
XS GIS Cut Line= 3
      2011592.43       328753.28      2013153.11       326081.34
      2013447.26       325452.17
#Sta/Elev= 30
       0  601.94  555.01  599.55  695.01  601.07 1450.01  595.59 1855.01  588.55
 1945.01  582.04 1985.01  583.91 2345.01   583.4 2490.01  585.32 2495.01  583.94
    2505   576.2    2530  585.11 2535.01   584.2    2540  580.29 2550.01  575.87
 2565.01  574.99    2615  576.91 2630.01  581.18 2685.01  579.26 2730.01  584.15
    3220  582.21    3330  584.26    3340  583.38 3370.01  586.42    3390  583.23
    3410  584.18    3425  588.72    3485  592.27    3640  593.75 3788.88  592.68
#Mann= 3 , 0 , 0
       0    .055       0 2490.01     .04       0 2730.01    .055       0
Bank Sta=2490.01,2730.01
XS Rating Curve= 0
Exp/Cntr=0.3,0.1

Type RM Length L Ch R = 1 ,72303.68,881.34,902.88,716.57
XS GIS Cut Line= 3
      2013304.27       328226.24      2013868.07       327302.91
      2014276.63       325578.82
#Sta/Elev= 30
       0  589.14   44.99  590.86      85  589.49     135  591.22  309.99  590.81
     370  594.74     700  594.59     790  595.81    1010  593.67    1210   593.8
 1231.94  585.01    1260  576.82 1309.99  573.99    1350  575.64 1354.99  576.18
 1364.99  581.19    1375  578.49 1394.99  582.31    2290  581.95 2324.99  583.99
    2365  580.24    2425   579.9    2460  576.81    2465  576.89    2485  583.61
 2524.99  581.42    2625  583.17    2670  581.67    2685  584.64 2853.69  587.24
#Mann= 3 , 0 , 0
       0    .055       0 1231.94     .04       0 1394.99    .055       0
Bank Sta=1231.94,1394.99
XS Rating Curve= 0
Exp/Cntr=0.3,0.1

Type RM Length L Ch R = 1 ,71400.81,842.33,749.28,850.16
XS GIS Cut Line= 3
      2014677.01        328095.5      2014652.49       326461.29
      2014562.61       325497.11
#Sta/Elev= 30
       0  585.88    4.99  583.94   24.99  583.87      45  588.46  104.99  585.64
  179.99   585.8  214.99  590.61     235  591.62  714.99  590.94     935  592.86
    1025  591.42    1225  593.34    1235  592.41 1274.99  581.67    1390  582.96
    1405  580.54 1424.99  580.51 1439.99  574.99    1500  573.25 1524.99  575.14
 1529.99  576.72 1534.99  580.81 1544.99  581.52 1554.99  580.53    1560  581.72
 1944.99  582.54    2120  580.99    2180  582.68    2330  582.01 2602.75  586.32
#Mann= 3 , 0 , 0
       0    .055       0    1390     .04       0 1544.99    .055       0
Bank Sta=1390,1544.99
XS Rating Curve= 0
Exp/Cntr=0.3,0.1

Type RM Length L Ch R = 1 ,70651.52,1053.85,1084.19,984.26
XS GIS Cut Line= 2
      2015575.82       327948.43      2015232.64       325341.86
#Sta/Elev= 30
       0  585.05  265.01  584.03     365  589.18     470   592.5    1065  589.82
 1180.01  588.06    1305  587.69    1320  587.46    1355  579.97 1415.01  580.38
    1440   581.6 1450.01  575.73    1455  575.04    1515  572.45    1535  572.83
    1550  574.48 1560.01   580.5 1575.01  578.39    1590  578.59    1600  581.01
    1675  580.97 1755.01  578.58    1950  582.04    2020   581.4 2065.01  582.29
    2275  582.47    2360  580.75    2435  580.64    2560  582.54 2629.06  582.21
#Mann= 3 , 0 , 0
       0    .075       0    1440     .04       0 1560.01     .12       0
Bank Sta=1440,1560.01
XS Rating Curve= 0
Exp/Cntr=0.3,0.1

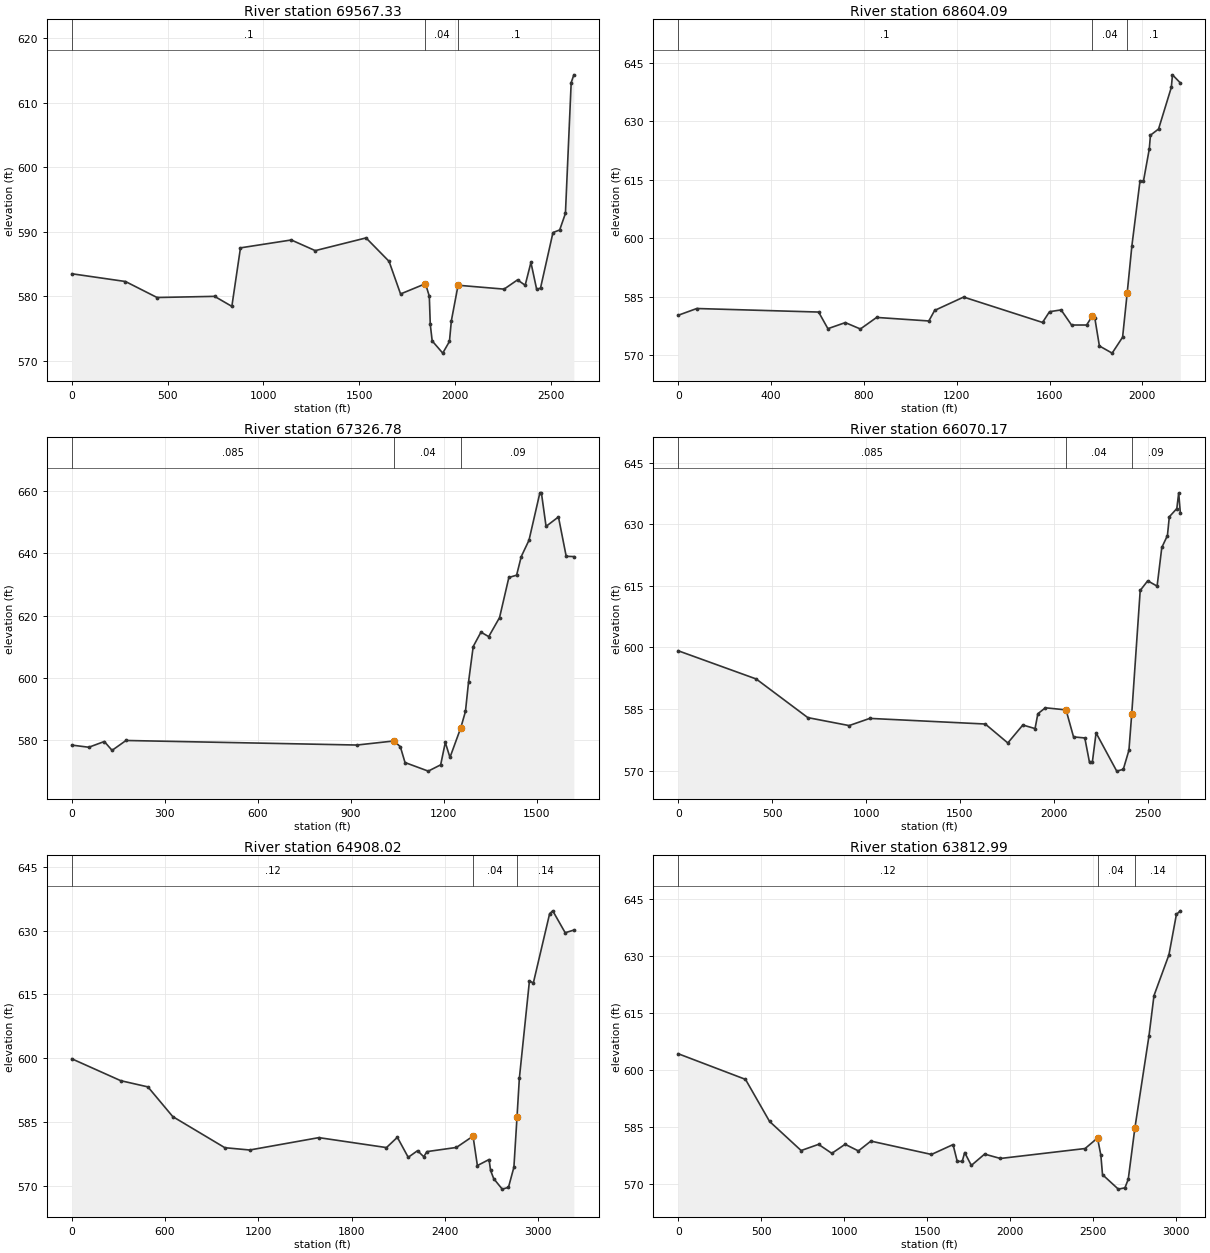
Type RM Length L Ch R = 1 ,69567.33,647.18,963.24,1032.38
XS GIS Cut Line= 2
      2016531.84       327825.86      2016204.99       325227.46
#Sta/Elev= 30
       0   583.5     280   582.3     445  579.82     745     580     835  578.45
     880  587.51    1145  588.73    1270  587.08    1535  589.05    1655  585.42
    1715  580.37 1845.01  581.96    1865  580.02    1870  575.65    1880   573.1
    1935  571.21    1970  573.02    1980  576.22 2015.01  581.72    2255  581.12
    2325  582.55    2365  581.72    2395  585.25    2425  581.08    2445  581.28
    2510  589.88    2545  590.28    2575  592.85    2605  613.09 2618.88   614.3
#Mann= 3 , 0 , 0
       0      .1       0 1845.01     .04       0 2015.01      .1       0
Bank Sta=1845.01,2015.01
XS Rating Curve= 0
Exp/Cntr=0.3,0.1

Type RM Length L Ch R = 1 ,68604.09,1043.26,1277.31,1296.09
XS GIS Cut Line= 3
      2016960.82       327740.06      2017034.36       326195.73
      2017320.34       325648.27
#Sta/Elev= 30
       0  580.23      80  581.96  604.99  581.05     645  576.78  719.99  578.34
     785   576.7     855  579.67 1079.99  578.76    1105  581.47 1229.99   584.9
    1570  578.38    1600  581.14    1650   581.6 1694.99  577.72 1759.99  577.72
    1784     580    1795  579.62 1814.99  572.34 1869.99   570.5    1915  574.59
 1934.99  586.04 1954.99  598.04 1989.99  614.72    2005   614.7    2030  622.92
    2035  626.47 2069.99  628.06    2125  638.76 2129.99  641.98 2163.73  639.91
#Mann= 3 , 0 , 0
       0      .1       0    1784     .04       0 1934.99      .1       0
Bank Sta=1784,1934.99
XS Rating Curve= 0
Exp/Cntr=0.3,0.1

Type RM Length L Ch R = 1 ,67326.78,1326.73,1256.61,1253.97
XS GIS Cut Line= 2
      2017344.86       327756.41      2018333.55       326473.55
#Sta/Elev= 30
       0  578.49      55   577.8     105  579.64     130   576.8  174.99  579.97
     920  578.51 1039.49  579.82 1060.01  577.95    1075   572.9    1150  570.14
    1190  572.16    1205  579.35 1220.01  574.53    1255  584.07    1270  589.29
    1280  598.78    1295  610.11    1320  614.72    1345  613.28    1380   619.4
    1410  632.25    1435     633    1450  638.97    1475  644.22    1510  659.39
 1515.01  659.41    1530  648.65    1570  651.68    1595  639.05 1619.64  638.96
#Mann= 3 , 0 , 0
       0    .085       0 1039.49     .04       0    1255     .09       0
Bank Sta=1039.49,1255
XS Rating Curve= 0
Exp/Cntr=0.3,0.1

Type RM Length L Ch R = 1 ,66070.17,1058.4,1162.15,1196.7
XS GIS Cut Line= 2
      2017692.13       329411.05      2019293.65       327270.23
#Sta/Elev= 30
       0  599.17     415  592.31     690   582.9     910  580.96    1020  582.71
    1635  581.34    1755  576.73    1835   581.1 1900.01  580.23    1915  583.84
    1955  585.29 2065.01  584.78 2105.01   578.2    2165  577.95    2190     572
    2205     572 2225.01  579.18    2335  569.87    2370  570.31    2400  574.96
    2415  583.88    2460  613.86    2500  616.21    2550  614.91    2575  624.32
    2605  627.23    2615   631.8    2655   633.8    2665  637.63 2673.57  632.81
#Mann= 3 , 0 , 0
       0    .085       0 2065.01     .04       0    2415     .09       0
Bank Sta=2065.01,2415
XS Rating Curve= 0
Exp/Cntr=0.3,0.1

Type RM Length L Ch R = 1 ,64908.02,1046.25,1095.03,1136.24
XS GIS Cut Line= 3
      2017986.28       330211.81      2020208.81       328062.82
      2020315.04       327972.94
#Sta/Elev= 30
       0  599.85     315   594.7  490.01  593.24  650.01  586.25     985  578.94
 1145.01   578.4 1590.01  581.31 2025.01  578.97    2095  581.39    2165  576.68
 2225.01  578.24    2265  576.81 2285.01  578.02    2475     579 2581.99  581.66
    2610  574.74    2685  576.16    2695  573.59    2715  571.67 2770.01   569.2
    2810  569.61 2845.01  574.35    2865  586.13 2880.01  595.23 2945.01  618.18
 2970.01  617.66    3075  633.98    3095  634.64 3175.01  629.49 3230.72  630.11
#Mann= 3 , 0 , 0
       0     .12       0 2581.99     .04       0    2865     .14       0
Bank Sta=2581.99,2865
XS Rating Curve= 0
Exp/Cntr=0.3,0.1

Type RM Length L Ch R = 1 ,63812.99,1100.51,1066.59,1055.78
XS GIS Cut Line= 3
      2018541.92       330767.44      2020257.84       329411.05
      2020952.38       328945.29
#Sta/Elev= 30
       0  604.26     405  597.51     550  586.42     740  578.75     845  580.38
     925  578.01    1005   580.4    1085  578.65    1160  581.24    1525  577.72
 1654.99  580.32    1680  575.92    1710  575.88    1725  578.22    1765  574.83
    1845  577.81    1940  576.66    2450  579.28    2525  582.05    2545  577.54
    2555   572.4    2650  568.58    2690  568.92    2710  571.18 2749.99   584.7
    2835  609.02 2864.99  619.59    2955  630.34    3000  640.98 3023.53  641.93
#Mann= 3 , 0 , 0
       0     .12       0    2525     .04       0 2749.99     .14       0
Bank Sta=2525,2749.99
XS Rating Curve= 0
Exp/Cntr=0.3,0.1

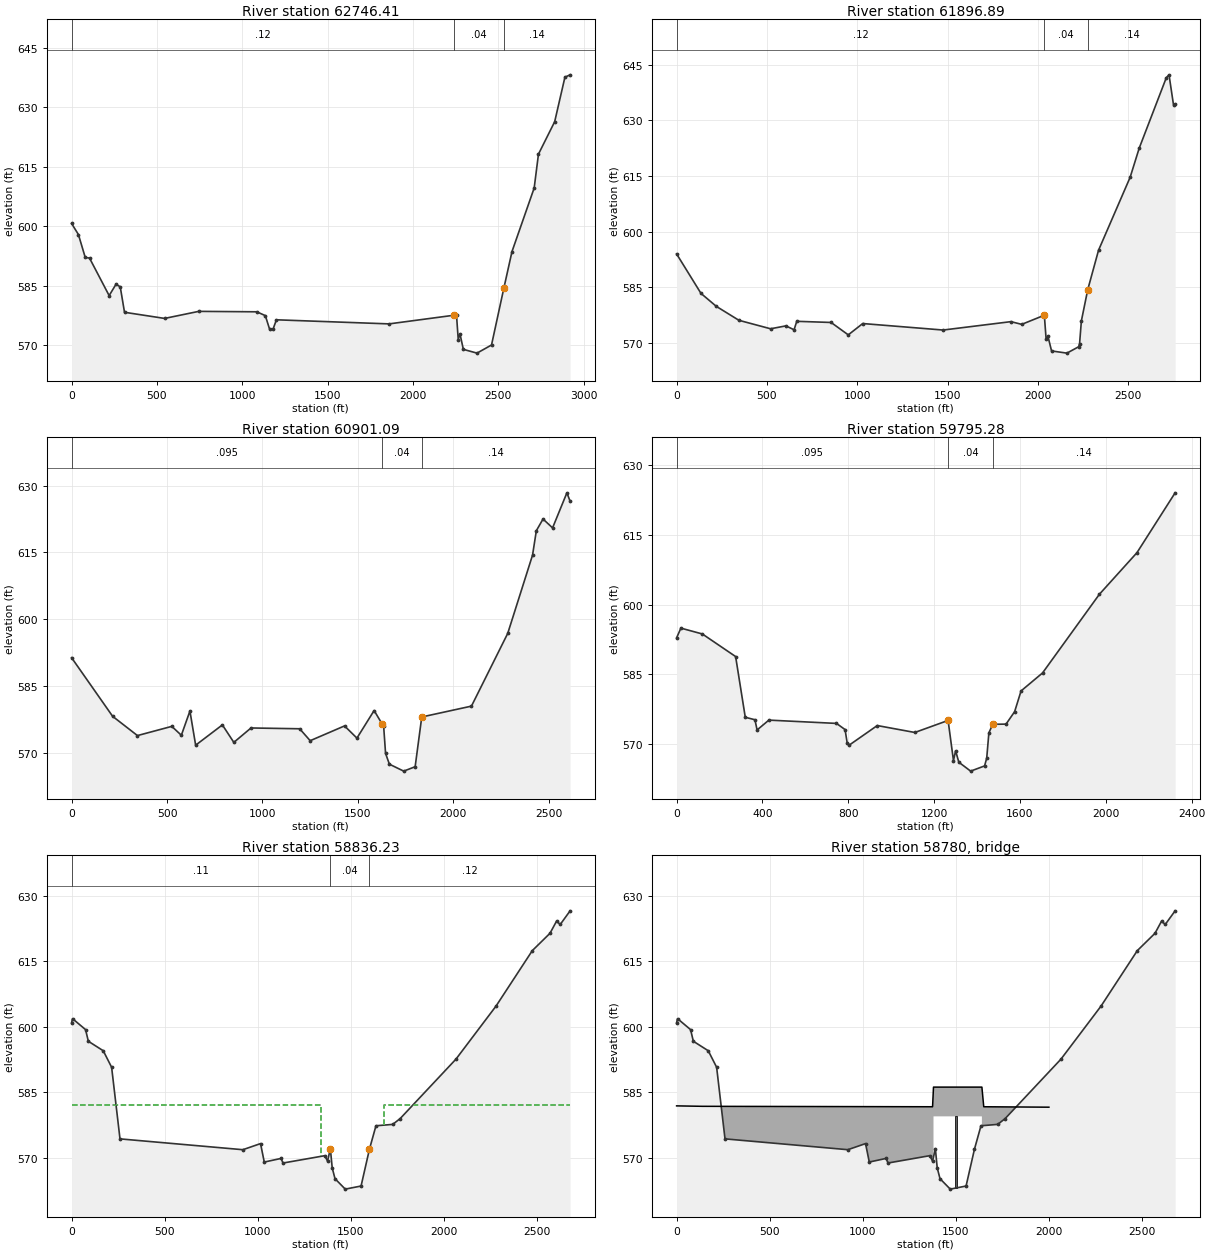
Type RM Length L Ch R = 1 ,62746.41,939.4,849.52,853.91
XS GIS Cut Line= 2
        2019310.       331502.84      2021630.58       329729.72
#Sta/Elev= 30
       0  600.68      40  597.89      80   592.1     105  591.95     220  582.48
     260  585.33     285   584.7     310  578.27     545  576.72     745   578.5
    1085  578.39    1135  577.42    1160  573.99    1180     574    1200  576.37
 1859.99  575.34  2239.4  577.52    2255  577.52    2265  571.39 2274.99  572.85
    2295  568.91    2375  567.96    2460  570.01 2532.91  584.49    2580   593.6
    2710  609.65    2735  618.18    2830  626.37    2890   637.6 2920.45   638.2
#Mann= 3 , 0 , 0
       0     .12       0  2239.4     .04       0 2532.91     .14       0
Bank Sta=2239.4,2532.91
XS Rating Curve= 0
Exp/Cntr=0.3,0.1

Type RM Length L Ch R = 1 ,61896.89,942.56,995.8,1028.23
XS GIS Cut Line= 3
      2020180.21       332160.61      2021569.29       330836.89
      2022239.32       330330.29
#Sta/Elev= 30
       0     594  135.01  583.37  220.01  579.87  345.01  576.12  520.01  573.84
     605  574.62  650.01  573.57  665.01  575.85  855.01  575.54     950   572.2
 1030.01  575.25 1475.01   573.5    1850  575.76    1910  575.03 2035.01  577.49
 2045.01  570.97 2055.01   571.8 2075.01  567.87 2160.01  567.28 2225.01     569
    2230   569.8 2240.01  575.96 2275.17  584.36 2335.01     595 2510.01  614.67
    2560  622.49 2710.01  641.48 2725.01  642.25 2750.01   634.1 2758.79  634.39
#Mann= 3 , 0 , 0
       0     .12       0 2035.01     .04       0 2275.17     .14       0
Bank Sta=2035.01,2275.17
XS Rating Curve= 0
Exp/Cntr=0.3,0.1

Type RM Length L Ch R = 1 ,60901.09,1148.8,1105.81,1040.91
XS GIS Cut Line= 4
      2021038.17       332773.44       2022018.7       331686.68
      2022500.79       331417.04      2022942.03       331016.66
#Sta/Elev= 30
       0  591.31     215  578.14  345.01  573.81  525.01  575.88  575.01  573.88
  620.01  579.33     650  571.65  790.01  576.21  850.01  572.28  940.01  575.52
 1195.01  575.34 1250.01  572.66 1430.01  575.98 1495.01  573.24    1585  579.44
 1628.27  576.32 1635.01  575.89 1645.01   569.8 1665.01  567.38 1740.01  565.82
 1800.01  566.81 1834.61  577.99 2095.01  580.43 2285.01  596.77 2415.01  614.36
 2435.01  619.86 2470.01  622.48 2520.01  620.49 2595.01  628.37 2611.92  626.48
#Mann= 3 , 0 , 0
       0    .095       0 1628.27     .04       0 1834.61     .14       0
Bank Sta=1628.27,1834.61
XS Rating Curve= 0
Exp/Cntr=0.3,0.1

Type RM Length L Ch R = 1 ,59795.28,725.16,959.05,1179.32
XS GIS Cut Line= 2
      2021896.14       333443.46      2023522.18       331784.74
#Sta/Elev= 30
       0  592.86      20  594.96  119.99   593.7     275  588.84     320  575.77
     365  575.24     375  573.04  429.99  575.16  744.99  574.45  784.99  573.12
  794.99  570.18     805   569.8     935  573.99    1110   572.5 1264.99  575.09
    1290  566.46    1300  568.56 1314.99   566.1    1370  564.18    1435   565.3
 1444.99  566.99 1454.99  572.41 1472.88  574.26 1534.99   574.3    1575  576.98
 1604.99  581.44    1705  585.31    1970  602.25 2144.99   611.2 2322.79  624.08
#Mann= 3 , 0 , 0
       0    .095       0 1264.99     .04       0 1472.88     .14       0
Bank Sta=1264.99,1472.88
XS Rating Curve= 0
Exp/Cntr=0.3,0.1

Type RM Length L Ch R = 1 ,58836.23,147.38,127.7,91.82
XS GIS Cut Line= 4
       2022341.9       333784.25      2023231.41       333077.87
      2023788.28       333126.46      2024483.45       332431.29
#Sta/Elev= 30
       0  600.93       5  601.88      75  599.37      90   596.7     170  594.53
     215  590.75     260  574.34     920  571.86    1015  573.26    1035  569.03
    1125  569.86 1135.87  568.81    1360  570.49 1375.01  569.24    1390   572.1
    1400   567.7    1415  565.22    1470  562.83    1555  563.54    1600  571.97
    1635  577.34 1725.01  577.66    1765  578.99    2065  592.62    2280  604.76
 2475.01  617.47    2570  621.44    2605  624.21    2625  623.46 2677.98  626.58
#Mann= 3 , 0 , 0
       0     .11       0    1390     .04       0    1600     .12       0
#XS Ineff= 2 , 0
       0    1340     582    1678       0     582
Permanent Ineff=
       F       F
Bank Sta=1390,1600
XS Rating Curve= 0
Exp/Cntr=0.3,0.1

Type RM Length L Ch R = 3 ,58780   ,,,
Node Photo=xsect8_a.gif
Bridge Culvert-0,0,-1,-1, 0
Deck Dist Width WeirC Skew NumUp NumDn MinLoCord MaxHiCord MaxSubmerge Is_Ogee
40,20,2.6,0, 9, 9, , , 0.95, 0, 0,0,,
       0     138    1375    1380    1380    1640    1640    1650    2000
   581.9   581.8   581.7   586.2   586.2   586.2   586.2   581.7   581.6
     560     560     560     560   579.5   579.5     560     560     560
       0     138    1275    1280    1280    1540    1540    1550    1900
   581.9   581.8   581.7   586.2   586.2   586.2   586.2   581.7   581.6
     560     560     560     560   579.5   579.5     560     560     560
Pier Skew, UpSta & Num, DnSta & Num=  ,1500, 2 ,1400, 2 , 0 , 0 , 0 ,,
       8       8
     555     581
       8       8
     555     581
BR Coef=-1 , 0 , 0 ,, 0 ,,,0.8,-1,,1,
WSPro=,,,, 1 ,,,, 0 ,,,, 0 ,,,,-1 ,-1 ,-1 , 0 , 0 , 0 , 0 , 0
BC Design=,, 0 ,, 0 ,,,,,,
BC HTab HWMax=590

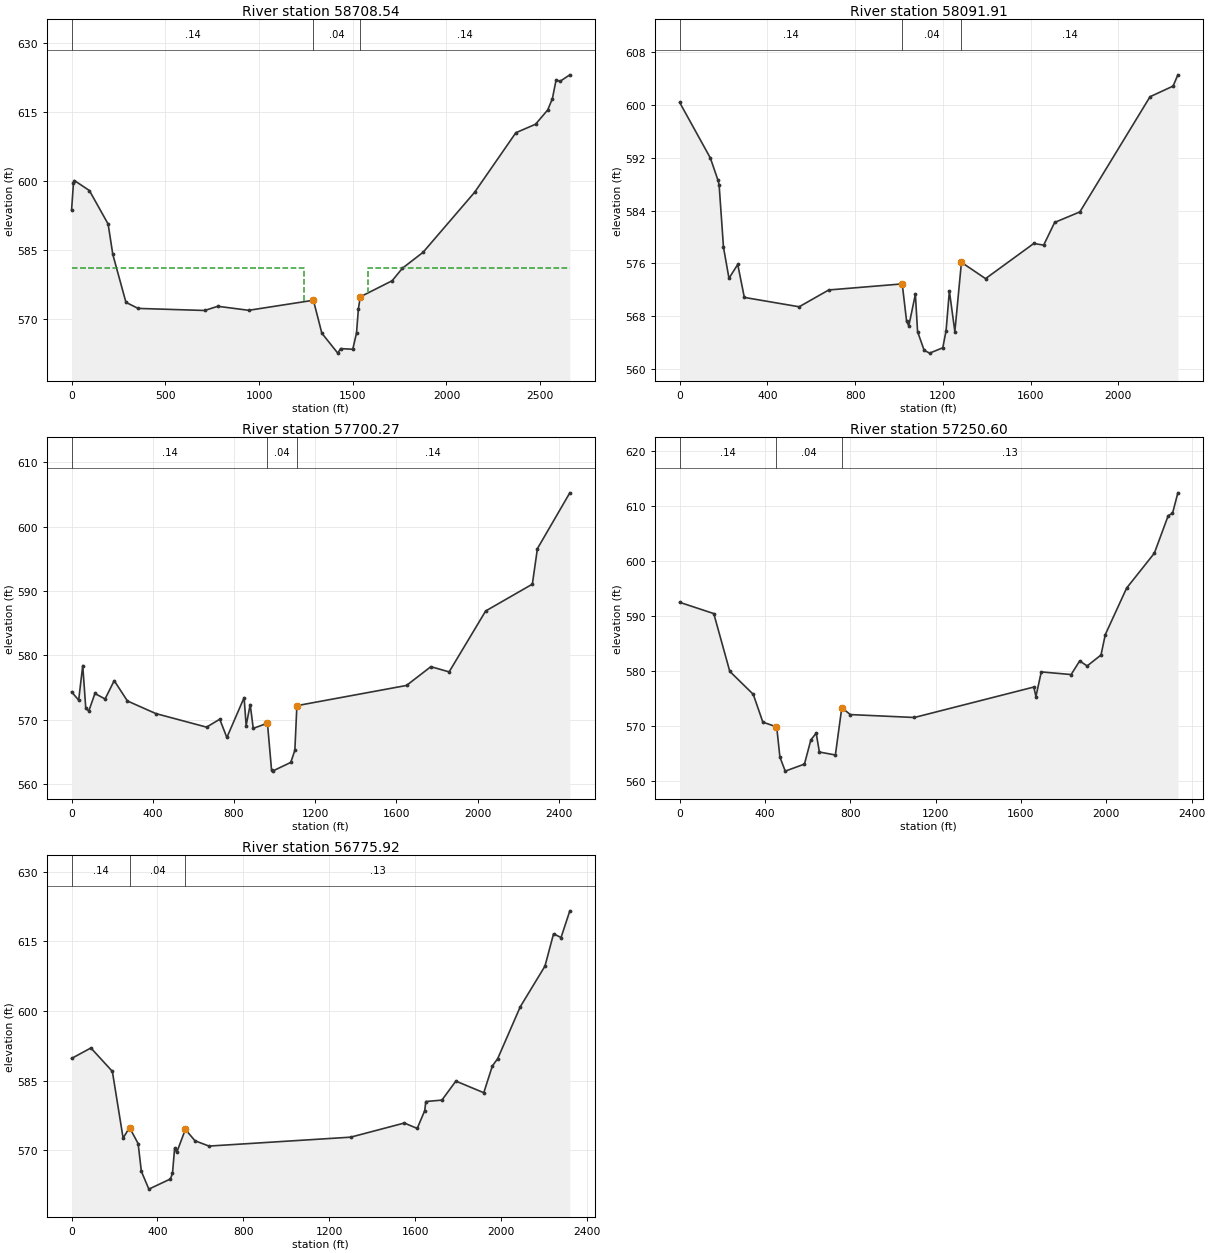
Type RM Length L Ch R = 1 ,58708.54,910.33,616.62,484.39
XS GIS Cut Line= 4
      2022468.97       333892.63      2023291.21       333201.21
      2023814.45       333216.16      2024584.36       332487.36
#Sta/Elev= 30
       0  593.67    9.99  599.47      15  600.06      95  597.89     195  590.62
     220  584.02     290  573.64     355  572.32     710  571.87     780  572.78
     945  571.91    1290  574.09    1335  566.95    1420  562.62    1435   563.6
 1499.99  563.46    1520  566.98 1529.99   572.2    1540  574.83    1710  578.32
    1765  581.04    1875  584.49    2150  597.51    2370  610.43    2475  612.27
    2540  615.37    2565  617.84    2585  621.93    2605  621.56 2657.91  622.99
#Mann= 3 , 0 , 0
       0     .14       0    1290     .04       0    1540     .14       0
#XS Ineff= 2 , 0
       0    1240     581    1580       0     581
Permanent Ineff=
       F       F
Bank Sta=1290,1540
XS Rating Curve= 0
Exp/Cntr=0.3,0.1

Type RM Length L Ch R = 1 ,58091.91,432.77,391.65,387.22
XS GIS Cut Line= 3
      2023266.91       334451.38      2024492.79       333218.02
      2024694.61       332724.68
#Sta/Elev= 30
       0  600.43  140.01     592     175  588.61     180  587.92     200  578.45
     225  573.75     265  575.85     295  570.85     545  569.43     680  571.98
    1015   572.9    1035  567.22    1045  566.53 1075.01  571.33    1085  565.66
 1115.01  562.83    1140   562.4 1200.01  563.21    1215  565.82    1230  571.82
    1255  565.66    1285  576.17    1395   573.7    1615  579.03    1660  578.78
    1710  582.22    1825  583.82 2145.01  601.29    2250   602.9 2271.98  604.61
#Mann= 3 , 0 , 0
       0     .14       0    1015     .04       0    1285     .14       0
Bank Sta=1015,1285
XS Rating Curve= 0
Exp/Cntr=0.3,0.1

Type RM Length L Ch R = 1 ,57700.27,451.26,449.67,326.97
XS GIS Cut Line= 4
      2023741.57       334754.11      2024197.53       334066.42
      2024780.57       333475.91      2025064.62       332728.42
#Sta/Elev= 30
       0   574.3      35  573.02      55   578.4      70  571.73      85  571.34
     115  574.05     165   573.2  209.99  576.05     275  572.89     415  570.93
     665  568.82     730  570.05     765  567.21     850  573.41     860  569.07
     880  572.33     895  568.63     965  569.43     985  562.21     990  561.98
    1080  563.34    1100  565.22    1110  572.16    1650   575.3    1770  578.22
    1860  577.41    2040  586.88    2270  591.05    2295  596.58  2454.6  605.25
#Mann= 3 , 0 , 0
       0     .14       0     965     .04       0    1110     .14       0
Bank Sta=965,1110
XS Rating Curve= 0
Exp/Cntr=0.3,0.1

Type RM Length L Ch R = 1 ,57250.60,466.25,474.68,345.51
XS GIS Cut Line= 5
      2024347.03       334784.01      2024586.23       334208.44
      2024847.85        333924.4      2025139.37       333416.11
      2025371.09       332713.47
#Sta/Elev= 30
       0  592.54     160  590.49  235.01     580     345  575.83     390  570.78
  449.99  569.97     455  569.87     470  564.43     495  561.88     585  563.16
     615  567.54     640  568.78     655  565.35     730  564.81     760   573.4
     800  572.15    1100  571.62 1660.01  577.15    1670  575.43 1695.01   579.9
    1835  579.42    1875  581.89    1910  580.98    1975  582.97    1995  586.67
    2095  595.12    2225  601.46    2290  608.28 2310.01  608.69 2335.28  612.42
#Mann= 3 , 0 , 0
       0     .14       0  449.99     .04       0     760     .13       0
Bank Sta=449.99,760
XS Rating Curve= 0
Exp/Cntr=0.3,0.1

Type RM Length L Ch R = 1 ,56775.92,542.79,532.13,480.2
XS GIS Cut Line= 4
      2024810.47       334843.81      2025191.69       334058.95
      2025460.79       333393.68      2025632.71       332683.57
#Sta/Elev= 30
       0  589.76      90  592.02     190  586.97     240  572.59  270.01  574.86
     310  571.41     325  565.43     360  561.59  460.01  563.77     470  564.96
  480.01  570.42     490  569.53     530  574.46     575  572.01  640.01  570.87
 1300.01  572.79 1550.01  575.84    1610  574.67 1645.01  578.52 1650.01  580.47
    1725  580.78    1790  584.88    1920  582.37    1960  588.14    1985  589.73
    2090   600.9    2205  609.66 2245.01  616.62 2280.01  615.83  2320.8  621.58
#Mann= 3 , 0 , 0
       0     .14       0  270.01     .04       0     530     .13       0
Bank Sta=270.01,530
XS Rating Curve= 0
Exp/Cntr=0.3,0.1