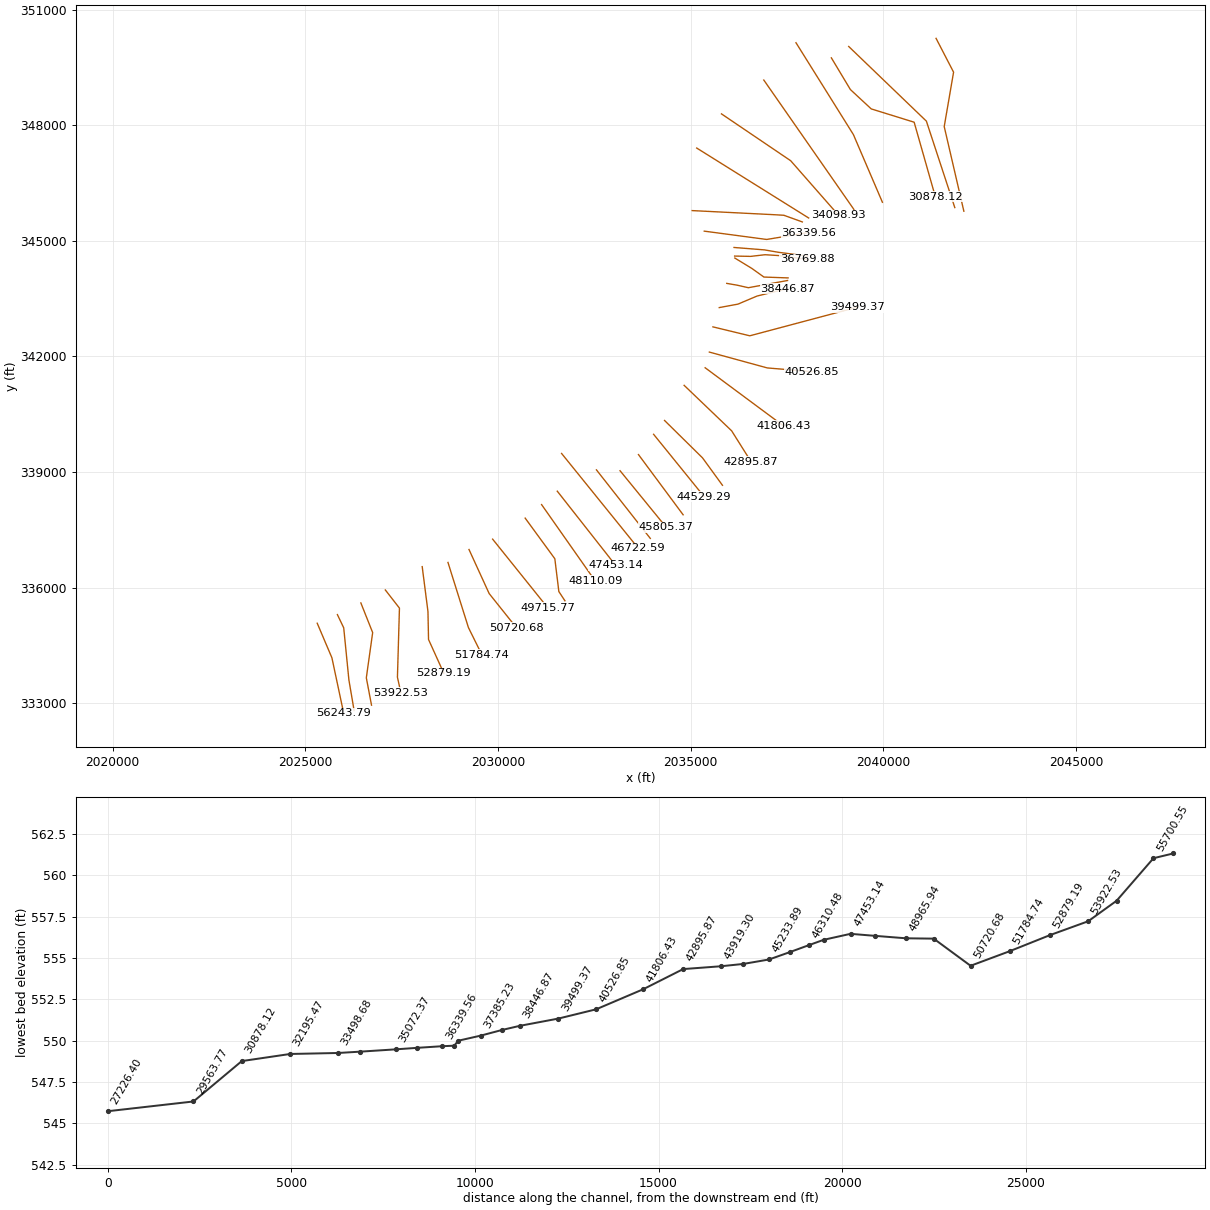
HEC-RAS study BaldEagle.prj: Bald Eagle Cr. for the WCDS Project

--- BaldEagle.g01 (geometry) --- (continued)

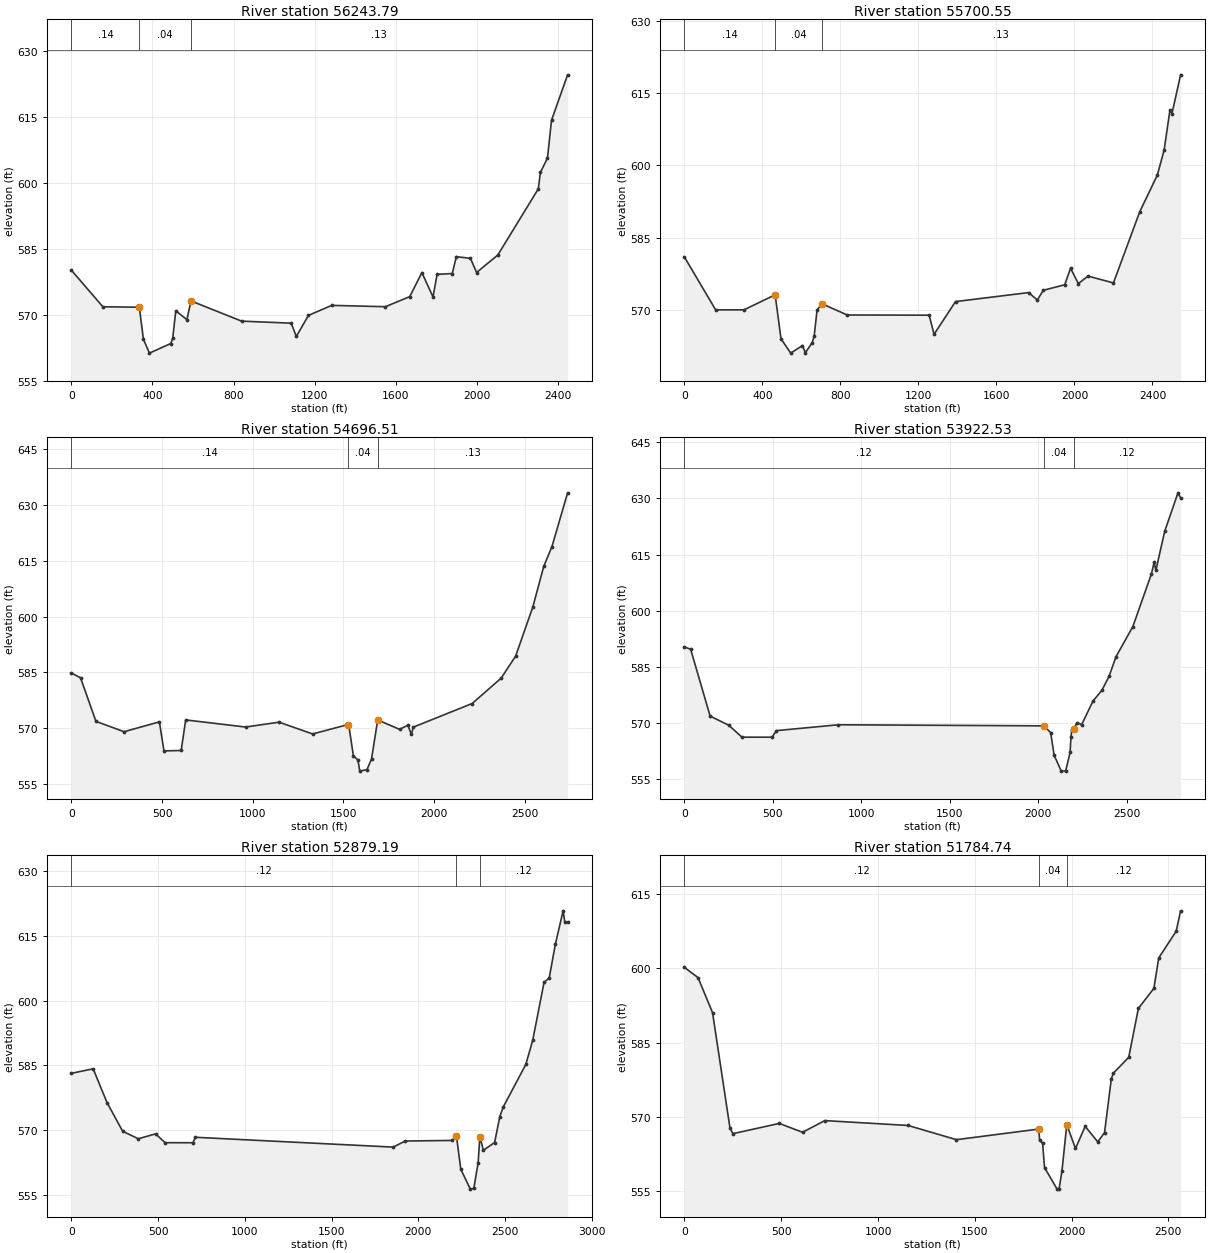
Type RM Length L Ch R = 1 ,56243.79,582.58,543.24,360.04
XS GIS Cut Line= 3
      2025311.29       335075.53      2025692.51       334178.55
      2025998.98        332735.9
#Sta/Elev= 30
       0  580.14     155  571.86  335.09  571.75     355   564.5     385  561.32
     490   563.5     500  564.74     515  570.95     570  568.92     590  573.19
     840  568.59    1085  568.13    1110   565.1    1170   569.9    1285  572.17
    1550  571.87    1670  574.16    1730  579.62    1785  574.09 1805.01  579.22
    1880  579.41    1900  583.25 1970.01  582.85    2000  579.64    2105  583.63
    2305  598.67    2315  602.38    2350  605.64    2370  614.24 2449.47  624.57
#Mann= 3 , 0 , 0
       0     .14       0  335.09     .04       0     590     .13       0
Bank Sta=335.09,590
XS Rating Curve= 0
Exp/Cntr=0.3,0.1

Type RM Length L Ch R = 1 ,55700.55,664.56,1004.05,541.98
XS GIS Cut Line= 4
      2025834.53       335299.78      2025998.98       334955.93
      2026133.52       333602.98      2026268.07       332810.64
#Sta/Elev= 30
       0  580.95  160.01     570  305.01  570.01     465  573.13     495  564.01
  545.01  561.03     605   562.6     620   561.1  655.01  563.22  665.01  564.49
  680.01  569.98     705  571.27  835.01  568.94    1255   568.9    1280  564.93
    1390  571.72 1765.01  573.59    1810  572.04 1840.01  574.06 1950.01  575.21
    1980  578.64 2020.01  575.46    2070  577.01 2200.01  575.59    2335  590.37
    2425  597.94 2460.01  603.16 2490.01  611.51    2500   610.7 2544.46  618.76
#Mann= 3 , 0 , 0
       0     .14       0     465     .04       0     705     .13       0
Bank Sta=465,705
XS Rating Curve= 0
Exp/Cntr=0.3,0.1

Type RM Length L Ch R = 1 ,54696.51,946.4,773.97,788.98
XS GIS Cut Line= 4
      2026443.73       335602.51       2026750.2        334832.6
      2026585.75       333659.04       2026720.3       332948.93
#Sta/Elev= 30
       0  584.81      50  583.54     135  571.83     290  569.05     485   571.7
     510  563.89  605.01  564.01     630  572.22     960  570.31 1145.01  571.61
 1330.01  568.45 1523.65  570.95    1530  570.57    1555  562.57    1580  561.46
    1590  558.46    1630  558.88    1655  561.74 1688.93  572.21    1810  569.68
    1855   570.8    1875  568.35    1885  570.27    2210  576.63    2370  583.45
    2450  589.39    2545  602.64 2605.01  613.51    2650  618.78 2736.43  633.24
#Mann= 3 , 0 , 0
       0     .14       0 1523.65     .04       0 1688.93     .13       0
Bank Sta=1523.65,1688.93
XS Rating Curve= 0
Exp/Cntr=0.3,0.1

Type RM Length L Ch R = 1 ,53922.53,758.88,1043.34,1115.72
XS GIS Cut Line= 4
       2027079.1       335938.88      2027445.36       335467.96
      2027393.04       333673.99      2027482.74       333270.35
#Sta/Elev= 30
       0  590.36      35  589.73     145  571.91     250  569.48     325  566.28
     495  566.28     520  568.03     870  569.59 2032.92   569.3    2070   567.5
    2090  561.46 2129.99  557.22    2155  557.26    2180   562.2    2185  566.29
    2190  568.26 2200.09   568.4 2219.99  570.18 2244.99   569.6    2310  575.96
 2359.99   578.8 2399.99   582.5 2439.99  587.79    2535  595.81    2640  609.87
 2654.99  612.93 2664.99  610.81 2714.99  621.23    2790  631.49  2804.8  630.12
#Mann= 3 , 0 , 0
       0     .12       0 2032.92     .04       0 2200.09     .12       0
Bank Sta=2032.92,2200.09
XS Rating Curve= 0
Exp/Cntr=0.3,0.1

Type RM Length L Ch R = 1 ,52879.19,951.66,1094.44,1110.64
XS GIS Cut Line= 4
      2028035.88       336544.34      2028185.38       335378.26
      2028200.33        334653.2      2028596.49       333778.64
#Sta/Elev= 30
       0  583.17     125  584.21     205   576.4  294.99  569.77     385  568.03
     485  569.16     540  567.12     700  567.11     715  568.37    1855   566.1
    1925  567.51    2195  567.64 2219.99  568.64    2245  560.97    2300  556.38
 2319.99  556.54    2345  562.47    2355  568.55    2375  565.36    2440  567.16
    2470  573.16    2490   575.4 2619.99  585.22    2660  590.87    2725  604.18
    2755  605.25    2790  612.98    2835  620.75    2845   618.1 2860.94  618.19
#Mann= 3 , 0 , 0
       0     .12       0 2219.99     .04       0    2355     .12       0
Bank Sta=2219.99,2355
XS Rating Curve= 0
Exp/Cntr=0.3,0.1

Type RM Length L Ch R = 1 ,51784.74,853.75,1064.06,1088.78
XS GIS Cut Line= 3
      2028704.88       336652.73      2029235.59       334963.41
      2029586.91       334253.29
#Sta/Elev= 30
       0  600.19   70.01  598.13  145.01  591.06     235  567.77     250  566.61
  490.01  568.68     610  566.89     725  569.25 1155.01  568.27    1405   565.4
    1830  567.54 1835.01  565.24    1850   564.7    1860  559.77    1925  555.41
 1935.01  555.41    1950  559.06 1975.01  568.43    2020  563.62    2070  568.08
 2135.01  564.96 2170.01  566.81 2205.01  577.67    2215  578.81 2295.01  582.03
    2345  591.92 2425.01  595.96    2450  602.11 2540.01  607.49    2563  611.62
#Mann= 3 , 0 , 0
       0     .12       0    1830     .04       0 1975.01     .12       0
Bank Sta=1830,1975.01
XS Rating Curve= 0
Exp/Cntr=0.3,0.1

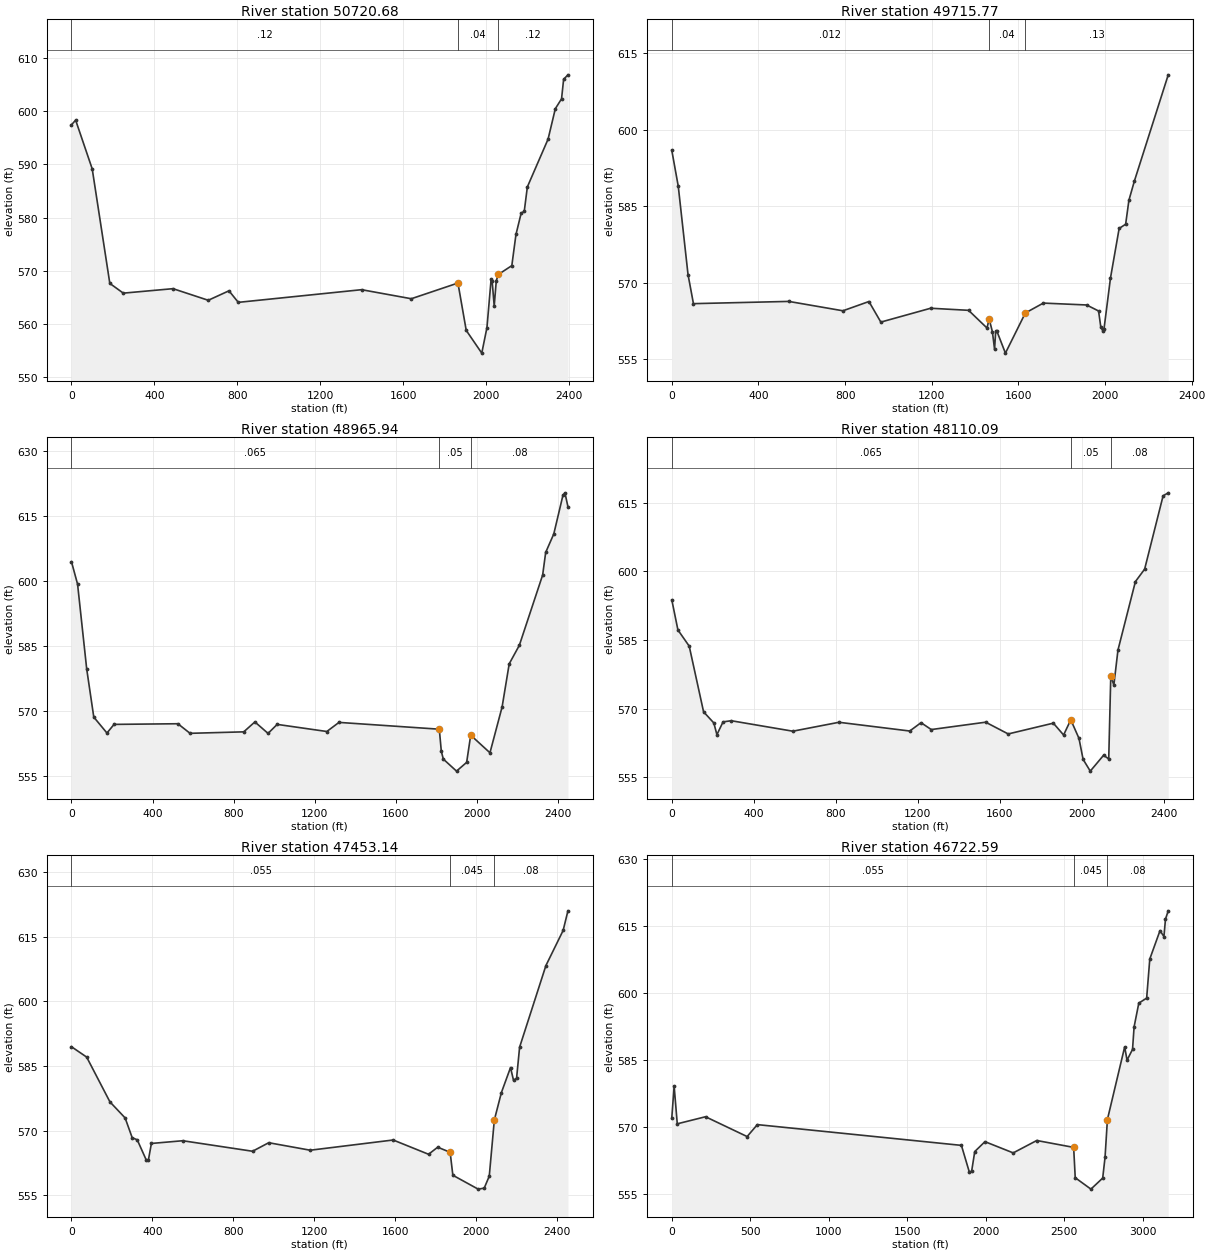
Type RM Length L Ch R = 1 ,50720.68,1013.44,1004.92,960.68
XS GIS Cut Line= 3
      2029250.54       336989.09      2029773.79       335845.44
       2030483.9       334955.93
#Sta/Elev= 30
       0  597.43      20  598.31     100  589.15  184.99  567.63  249.99   565.8
  489.99  566.64  659.99  564.46     760  566.24     805  564.07    1400  566.45
    1640  564.75    1865   567.7    1905   558.8 1979.99  554.53    2005  559.34
    2025  568.37 2029.99   568.1    2040  563.37    2050  568.13    2060  569.31
    2125  570.97    2145  576.82 2169.99  580.81 2184.99  581.17 2199.99  585.76
 2299.99  594.74    2335  600.46 2364.99  602.31    2375  605.98 2395.86  606.82
#Mann= 3 , 0 , 0
       0     .12       0    1865     .04       0    2060     .12       0
Bank Sta=1865,2060
XS Rating Curve= 0
Exp/Cntr=0.3,0.1

Type RM Length L Ch R = 1 ,49715.77,973.05,749.83,546.4
XS GIS Cut Line= 2
      2029863.48       337258.19      2031298.66        335471.7
#Sta/Elev= 30
       0  595.98      30  588.91   75.01  571.59     100  565.88     540  566.32
     790  564.48     910   566.3     965  562.26    1195  564.98    1370  564.57
    1455   561.1    1465  562.87 1480.01  560.35 1490.01  556.89    1495  560.48
    1500  560.55    1540  556.17 1632.06  564.05    1715  565.99    1915  565.62
    1970  564.44 1980.01  561.38    1990  560.49    1995  560.89    2025  570.92
    2065  580.64    2095  581.47    2110  586.16    2135   589.9 2291.57  610.79
#Mann= 3 , 0 , 0
       0    .012       0    1465     .04       0 1632.06     .13       0
Bank Sta=1465,1632.06
XS Rating Curve= 0
Exp/Cntr=0.3,0.1

Type RM Length L Ch R = 1 ,48965.94,535.92,855.85,934.1
XS GIS Cut Line= 4
      2030708.14       337803.86      2031478.06        336749.9
       2031582.7       335897.76      2031739.68       335658.57
#Sta/Elev= 30
       0  604.48   30.01  599.32   75.01  579.77  110.01  568.65  175.01  564.98
  210.01  566.97  525.01  567.12  585.01  564.91  850.01  565.25  905.01  567.54
  970.01  564.89    1015  566.97    1260  565.33    1320  567.43    1815  565.86
 1825.01  560.75    1835  558.96 1900.01  556.19 1950.01  558.21 1970.01  564.48
 2065.01  560.42    2125     571 2160.01  580.94 2210.01  585.21 2325.01  601.42
 2340.01  606.64 2380.01   610.9 2425.01  619.78 2435.01  620.38 2449.87  617.17
#Mann= 3 , 0 , 0
       0    .065       0    1815     .05       0 1970.01     .08       0
Bank Sta=1815,1970.01
XS Rating Curve= 0
Exp/Cntr=0.3,0.1

Type RM Length L Ch R = 1 ,48110.09,601.13,656.95,661
XS GIS Cut Line= 2
      2031134.21       338155.17      2032524.54       336174.33
#Sta/Elev= 30
       0   593.8      30   587.2      85  583.67  154.99  569.31     205  566.87
     220  564.31     250  567.11     290  567.36     590  565.07     815  567.02
    1160  565.11    1215  566.93    1265  565.43    1530  567.04 1639.99  564.47
    1860  566.83 1909.99  564.24 1945.01  567.56    1985   563.5    2005  558.92
    2040  556.34    2105  559.81 2129.99  559.01    2140  577.15    2155  575.16
    2175  582.81    2260  597.78    2305   600.5    2395  616.53 2420.07  617.19
#Mann= 3 , 0 , 0
       0    .065       0 1945.01     .05       0    2140     .08       0
Bank Sta=1945.01,2140
XS Rating Curve= 0
Exp/Cntr=0.3,0.1

Type RM Length L Ch R = 1 ,47453.14,752.33,730.56,732.77
XS GIS Cut Line= 2
      2031541.59       338502.76      2033058.99       336574.24
#Sta/Elev= 30
       0  589.47   75.01  587.07     190  576.69  265.01  572.97     300  568.39
  325.01  567.89     370  563.17     380  563.17     395  567.05  550.01  567.68
     895  565.24     975  567.22 1180.01  565.48    1590  567.85 1765.01  564.54
 1810.01  566.18  1871.6     565 1885.01  559.68    2010  556.46 2040.01  556.69
    2065  559.47 2090.01  572.48 2125.01  578.85 2170.01  584.64 2185.01  581.67
    2200  582.17    2215  589.38    2345  608.29 2430.01  616.42 2453.91  620.98
#Mann= 3 , 0 , 0
       0    .055       0  1871.6    .045       0 2090.01     .08       0
Bank Sta=1871.6,2090.01
XS Rating Curve= 0
Exp/Cntr=0.3,0.1

Type RM Length L Ch R = 1 ,46722.59,450.02,412.11,417.44
XS GIS Cut Line= 2
      2031653.71       339481.96      2033642.03       337022.73
#Sta/Elev= 30
       0  571.98      15  579.14      35   570.7     215  572.28     480  567.85
     545  570.52    1845  565.88    1895  559.96    1910  560.07    1930   564.5
    1995  566.71    2175   564.2    2325  566.97    2560  565.43    2570  558.65
    2670   556.1    2745  558.57 2760.01  563.24    2775  571.66    2885   587.9
    2900  584.93    2935  587.33    2945  592.37    2975  597.68    3025   598.8
    3045  607.55    3110  613.88    3135  612.56    3145  616.47 3162.47  618.31
#Mann= 3 , 0 , 0
       0    .055       0    2560    .045       0    2775     .08       0
Bank Sta=2560,2775
XS Rating Curve= 0
Exp/Cntr=0.3,0.1

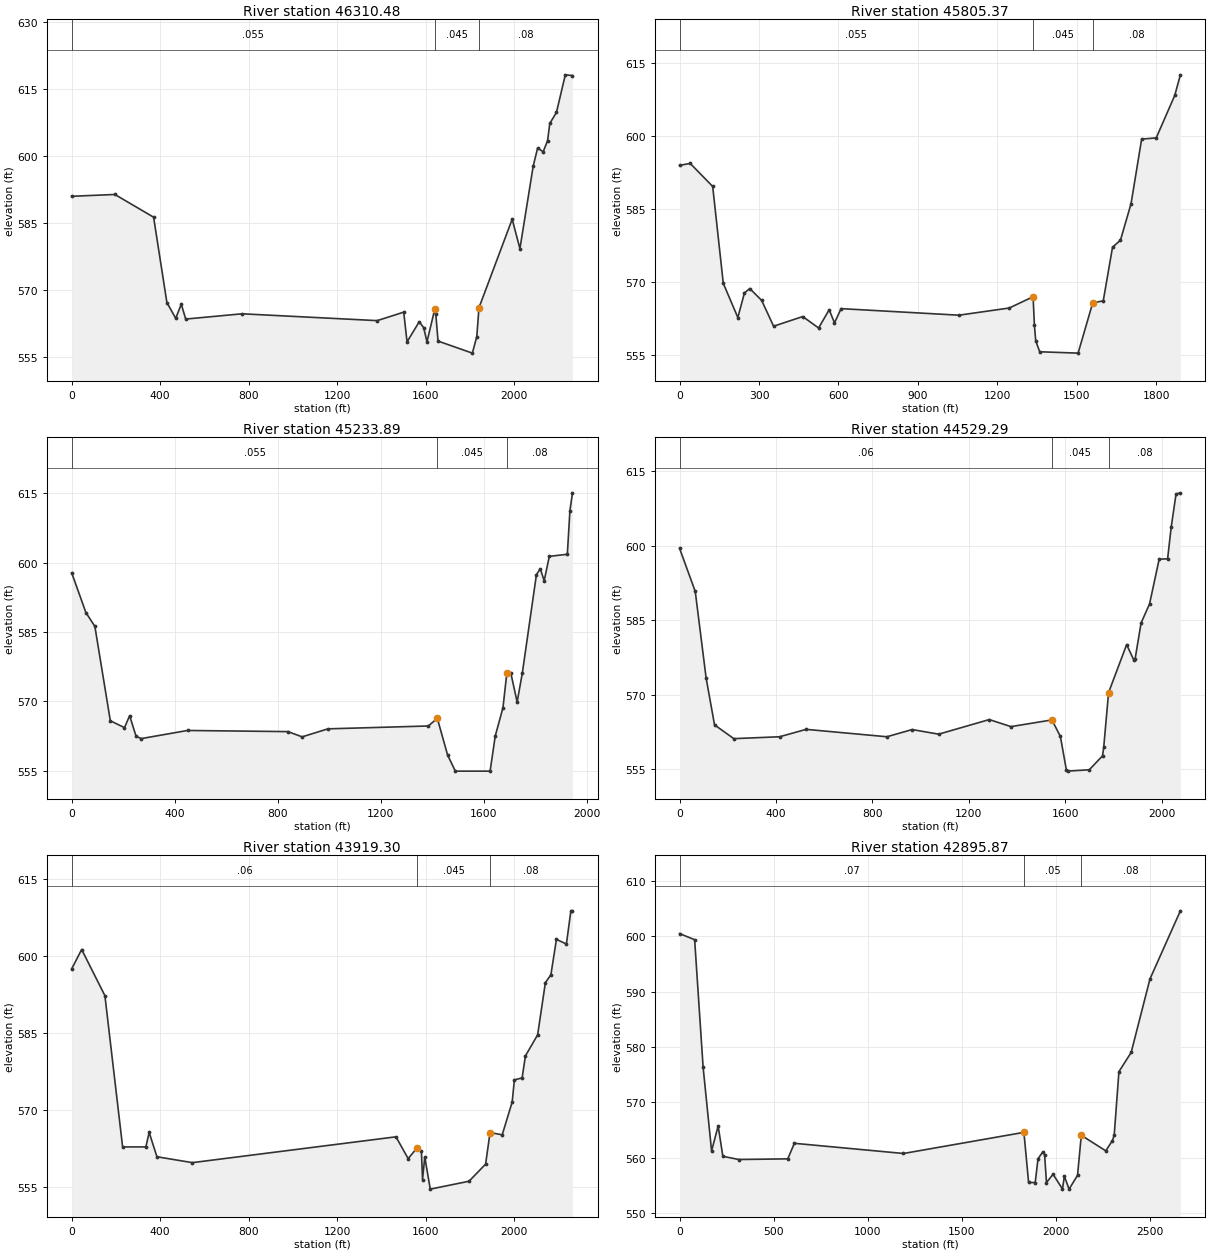
Type RM Length L Ch R = 1 ,46310.48,515.81,505.11,504.5
XS GIS Cut Line= 2
      2032558.17        339055.9      2033955.97       337276.88
#Sta/Elev= 30
       0   590.9  195.01  591.31  370.01  586.22  430.01  567.11     470  563.56
  495.01  566.74  515.01   563.4  770.01  564.58    1380  563.05 1500.01  564.95
 1515.01  558.29    1570  562.79 1590.01  561.49 1605.01  558.31 1640.01  565.56
 1645.01  564.46 1655.01  558.47    1810  555.77 1830.01  559.44 1840.01  565.94
 1990.01  585.76    2025  579.17 2085.01  597.68    2105  601.71    2130  600.87
 2150.01  603.39    2160  607.23    2190  609.68    2230  618.11 2262.47  617.95
#Mann= 3 , 0 , 0
       0    .055       0 1640.01    .045       0 1840.01     .08       0
Bank Sta=1640.01,1840.01
XS Rating Curve= 0
Exp/Cntr=0.3,0.1

Type RM Length L Ch R = 1 ,45805.37,599.31,571.47,563.23
XS GIS Cut Line= 2
      2033171.11       339033.47      2034367.09        337568.4
#Sta/Elev= 30
       0  594.02   40.01  594.42     125  589.68     165  569.73     220  562.69
     245  567.76     265  568.66     310  566.21     355   560.9  465.01  562.89
     525  560.54     565  564.29     585  561.59     610  564.52    1055  563.17
    1245  564.65    1335  566.97    1340   561.1    1345   557.9    1360  555.64
    1505  555.36    1560  565.67 1600.01  566.14    1635  577.16    1665  578.62
    1705  586.14    1745  599.43    1800  599.67 1870.01  608.42 1891.24  612.66
#Mann= 3 , 0 , 0
       0    .055       0    1335    .045       0    1560     .08       0
Bank Sta=1335,1560
XS Rating Curve= 0
Exp/Cntr=0.3,0.1

Type RM Length L Ch R = 1 ,45233.89,705.96,704.6,714.86
XS GIS Cut Line= 2
       2033649.5       339452.06      2034808.11       337889.82
#Sta/Elev= 30
       0  597.82      55  589.24   90.01  586.23     150  565.81     205  564.32
     225   566.9     250  562.45     270  561.95  449.99  563.71     840  563.46
     895  562.33     995  564.06    1385  564.68    1420  566.33    1460  558.38
    1490  554.91    1625  554.91    1645  562.51    1675  568.64    1690  576.14
    1705  576.25    1730  569.86 1750.01  576.07    1805  597.46    1820   598.7
    1835   596.1 1854.99  601.39    1925  601.84    1935  611.26 1944.99  615.14
#Mann= 3 , 0 , 0
       0    .055       0    1420    .045       0    1690     .08       0
Bank Sta=1420,1690
XS Rating Curve= 0
Exp/Cntr=0.3,0.1

Type RM Length L Ch R = 1 ,44529.29,577.75,609.99,568.83
XS GIS Cut Line= 2
      2034041.93       339979.04      2035350.04       338364.47
#Sta/Elev= 30
       0  599.48      65  590.81     110  573.42     145  563.95     225  561.18
     415  561.56     525  563.05     860  561.56     965  563.01 1075.01  562.08
    1285  565.02    1375   563.6    1545  564.95    1580  561.63    1605  554.88
    1610  554.64    1700  554.91    1755  557.72    1760  559.49    1780  570.44
    1855  580.11    1885  576.98 1890.01   577.2    1915  584.47 1950.01  588.29
 1990.01  597.32    2025  597.38    2040   603.8    2060  610.44 2077.98  610.67
#Mann= 3 , 0 , 0
       0     .06       0    1545    .045       0    1780     .08       0
Bank Sta=1545,1780
XS Rating Curve= 0
Exp/Cntr=0.3,0.1

Type RM Length L Ch R = 1 ,43919.30,1040.77,1023.42,1050.78
XS GIS Cut Line= 3
      2034325.98       340337.84      2035312.66        339366.1
      2035828.43       338655.99
#Sta/Elev= 30
       0   597.5      45  601.27     150  592.26     230  562.74     335  562.74
  350.01  565.56     385  560.82     545  559.67    1465  564.71 1520.01  560.46
    1560  562.52    1580   561.9    1585  556.37    1595  560.77    1620   554.5
    1795  556.04    1870  559.38    1890  565.54    1945   565.1 1990.01  571.49
 2000.01  575.81    2035  576.22    2050  580.52    2105  584.61    2140  594.79
    2165  596.36    2190  603.25 2235.01  602.34    2255  608.74 2262.51  608.82
#Mann= 3 , 0 , 0
       0     .06       0    1560    .045       0    1890     .08       0
Bank Sta=1560,1890
XS Rating Curve= 0
Exp/Cntr=0.3,0.1

Type RM Length L Ch R = 1 ,42895.87,949.7,1089.44,1150.88
XS GIS Cut Line= 3
      2034834.27       341249.77      2036067.62       340068.74
      2036575.92       339261.45
#Sta/Elev= 30
       0  600.51      80   599.4     125  576.37  170.01  561.23     205  565.74
     230  560.26     315  559.68     575   559.8     610  562.61    1190  560.77
 1830.01  564.59    1855  555.53    1890  555.52    1905  559.82    1930  561.04
    1940  560.56 1949.99  555.52    1985  557.02    2035  554.35    2045  556.66
    2070  554.33    2115  556.82    2135  564.06    2265  561.25 2300.01  563.07
    2310   564.1    2335  575.56    2400  579.02    2500  592.31 2661.61  604.62
#Mann= 3 , 0 , 0
       0     .07       0 1830.01     .05       0    2135     .08       0
Bank Sta=1830.01,2135
XS Rating Curve= 0
Exp/Cntr=0.3,0.1

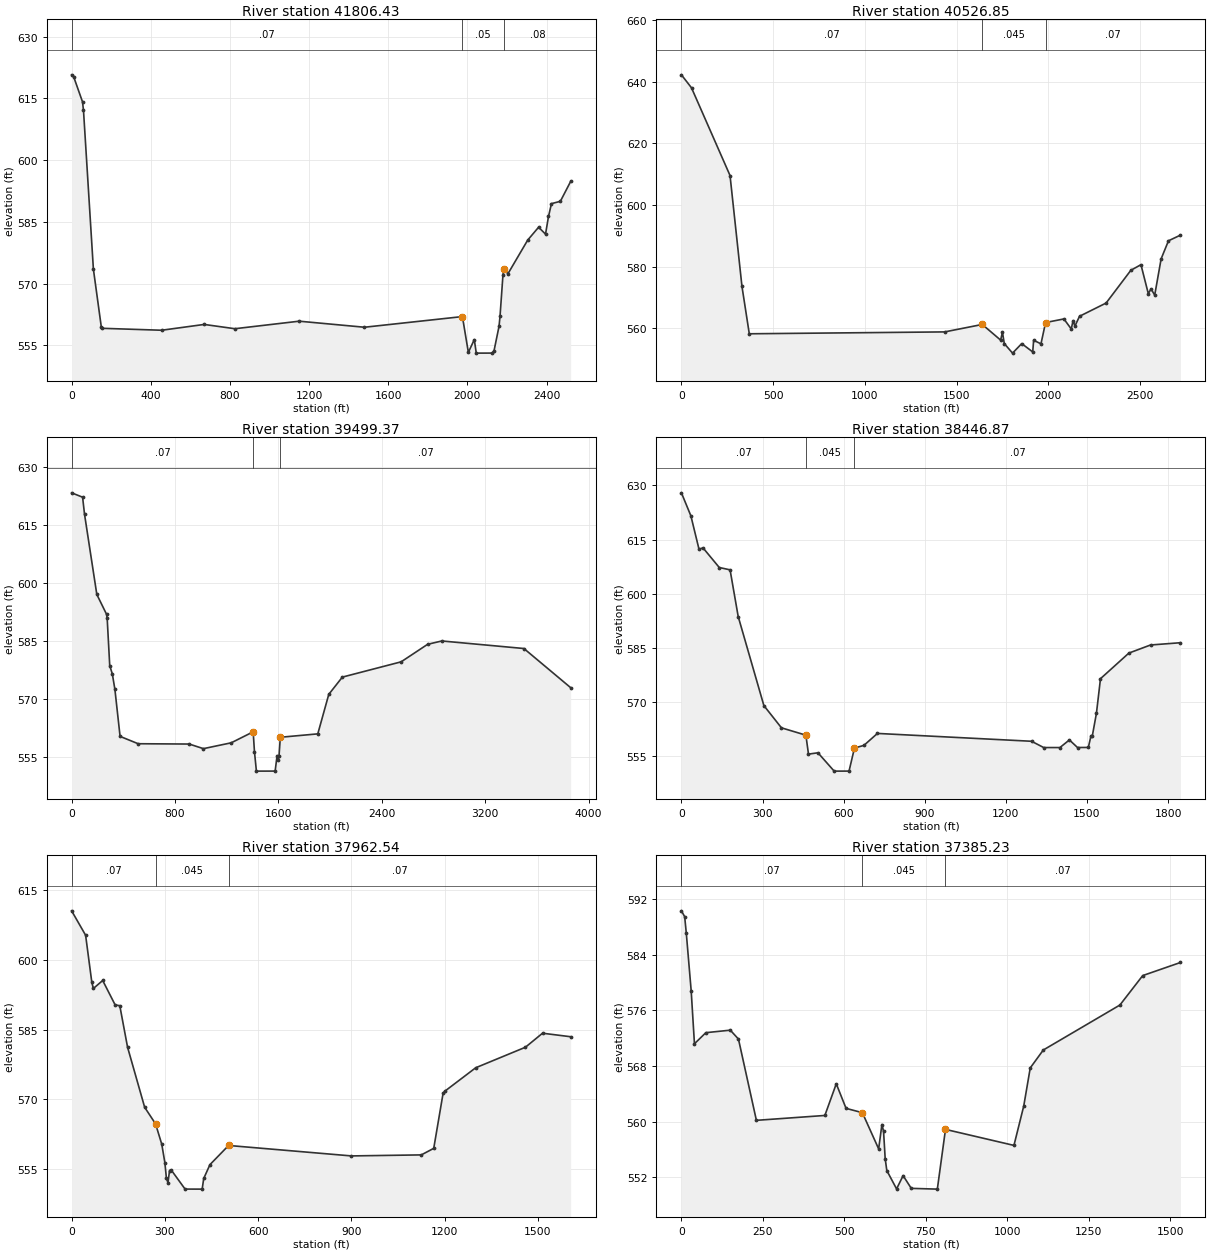
Type RM Length L Ch R = 1 ,41806.43,888.38,1279.58,1383.8
XS GIS Cut Line= 2
      2035379.94       341705.74      2037405.63       340203.29
#Sta/Elev= 30
       0  620.73      10  620.31      55  614.17      60   612.1     110  573.53
  149.99  559.48     155  559.14     455  558.67     670  560.08     825  559.04
    1150  560.87    1480   559.4    1975  561.99    2005  553.29    2035   556.4
    2045  553.11    2125  553.12    2135  553.74    2160  559.61    2165  562.02
    2180  572.18    2185  573.44    2205  572.39    2305  580.58    2360   583.7
    2395  582.02    2410  586.31    2425  589.43    2470     590 2522.06  594.83
#Mann= 3 , 0 , 0
       0     .07       0    1975     .05       0    2185     .08       0
Bank Sta=1975,2185
XS Rating Curve= 0
Exp/Cntr=0.3,0.1

Type RM Length L Ch R = 1 ,40526.85,815.3,1027.47,1143.96
XS GIS Cut Line= 3
      2035488.32       342113.12      2036990.77         341702.
      2038149.37       341604.83
#Sta/Elev= 30
       0  642.25      55  638.03  265.01  609.56     330  573.58     370  558.18
    1435  558.79    1640  561.21    1740  556.13 1750.01  558.68    1760     555
    1805   551.9    1855  554.99    1915  552.29    1920  556.07    1960  554.92
    1985  561.83    2085     563    2125  559.74    2135  562.45    2145  560.67
    2170  563.86    2315  568.16    2450   578.8    2505  580.61    2545  571.22
    2560  572.74    2580  570.74    2615  582.51    2655  588.37 2720.35  590.21
#Mann= 3 , 0 , 0
       0     .07       0    1640    .045       0    1985     .07       0
Bank Sta=1640,1985
XS Rating Curve= 0
Exp/Cntr=0.3,0.1

Type RM Length L Ch R = 1 ,39499.37,1020.48,1052.51,961.41
XS GIS Cut Line= 3
      2035581.76       342767.17      2036538.54       342535.45
      2039319.19       343275.46
#Sta/Elev= 30
       0  623.27      85  622.14     100  617.71     195  597.01     270   591.9
     275  590.94     295  578.58     315  576.48  334.99  572.45     375  560.32
     515  558.42     910  558.34 1019.99  557.15    1235  558.66 1404.99   561.5
    1415  556.34 1429.99  551.34 1574.99  551.35    1590  555.35 1599.99  554.28
 1604.99  555.25    1615  560.09 1904.99  560.97 1989.99  571.18 2094.99  575.64
    2550  579.59 2754.99  584.12 2864.99  584.98 3499.99  583.03 3861.87  572.91
#Mann= 3 , 0 , 0
       0     .07       0 1404.99    .045       0    1615     .07       0
Bank Sta=1404.99,1615
XS Rating Curve= 0
Exp/Cntr=0.3,0.1

Type RM Length L Ch R = 1 ,38446.87,555.93,484.33,254.37
XS GIS Cut Line= 4
       2035746.2       343267.98      2036232.07       343357.68
      2036725.41       343566.98      2037517.75       343761.32
#Sta/Elev= 30
       0  627.97      35   621.6      65  612.38   80.01  612.72  140.01  607.29
     180  606.64     210  593.72  305.01  569.05  370.01  562.89  460.34  560.86
     470  555.61  505.01  555.98     565   550.9     620  550.91  640.01  557.29
  675.01  558.03     725  561.34    1295  559.17 1340.01  557.43 1400.01  557.43
    1435  559.54 1465.01  557.44 1505.01  557.46 1515.01   560.7 1520.01  560.74
    1535  566.91    1550   576.5 1655.01  583.59 1735.01  585.83 1845.81  586.46
#Mann= 3 , 0 , 0
       0     .07       0  460.34    .045       0  640.01     .07       0
Bank Sta=460.34,640.01
XS Rating Curve= 0
Exp/Cntr=0.3,0.1

Type RM Length L Ch R = 1 ,37962.54,607.69,577.32,216.39
XS GIS Cut Line= 4
      2035940.55       343895.87      2036202.17       343851.02
      2036501.17       343783.75      2037517.75       343970.62
#Sta/Elev= 30
       0  610.57      45  605.32      65  595.17      70  593.85     100  595.57
     140  590.32     155  590.14     180   581.2     235  568.27  270.05   564.7
  290.01  560.32     300  556.35     305  552.96     310  552.03  315.01  554.65
     320  554.81     365  550.66     420  550.65     425  552.94     445  555.92
     505  560.05     900   557.8 1125.01  558.02    1165  559.43    1195  571.25
    1200   571.7    1300  576.78 1459.99   581.2    1515  584.22 1605.52  583.46
#Mann= 3 , 0 , 0
       0     .07       0  270.05    .045       0     505     .07       0
Bank Sta=270.05,505
XS Rating Curve= 0
Exp/Cntr=0.3,0.1

Type RM Length L Ch R = 1 ,37385.23,333.65,615.35,664.9
XS GIS Cut Line= 4
      2036149.85       344553.66      2036590.86       344284.57
      2036904.81       344060.32       2037532.7        344037.9
#Sta/Elev= 30
       0  590.28      10  589.44   14.99  587.07      30  578.77   39.99  571.19
   74.99  572.78     150  573.14  174.99  571.86  229.99  560.19     440  560.89
     475  565.44     505  561.91     555  561.29     605  556.09     615  559.59
     620  558.63     625   554.7     630  552.98     660  550.34  679.99  552.25
     705  550.42  784.99  550.31     810  558.89 1019.99  556.59    1050  562.24
 1069.99  567.72    1110  570.29    1345  576.75 1414.99  580.98 1530.73  582.86
#Mann= 3 , 0 , 0
       0     .07       0     555    .045       0     810     .07       0
Bank Sta=555,810
XS Rating Curve= 0
Exp/Cntr=0.3,0.1

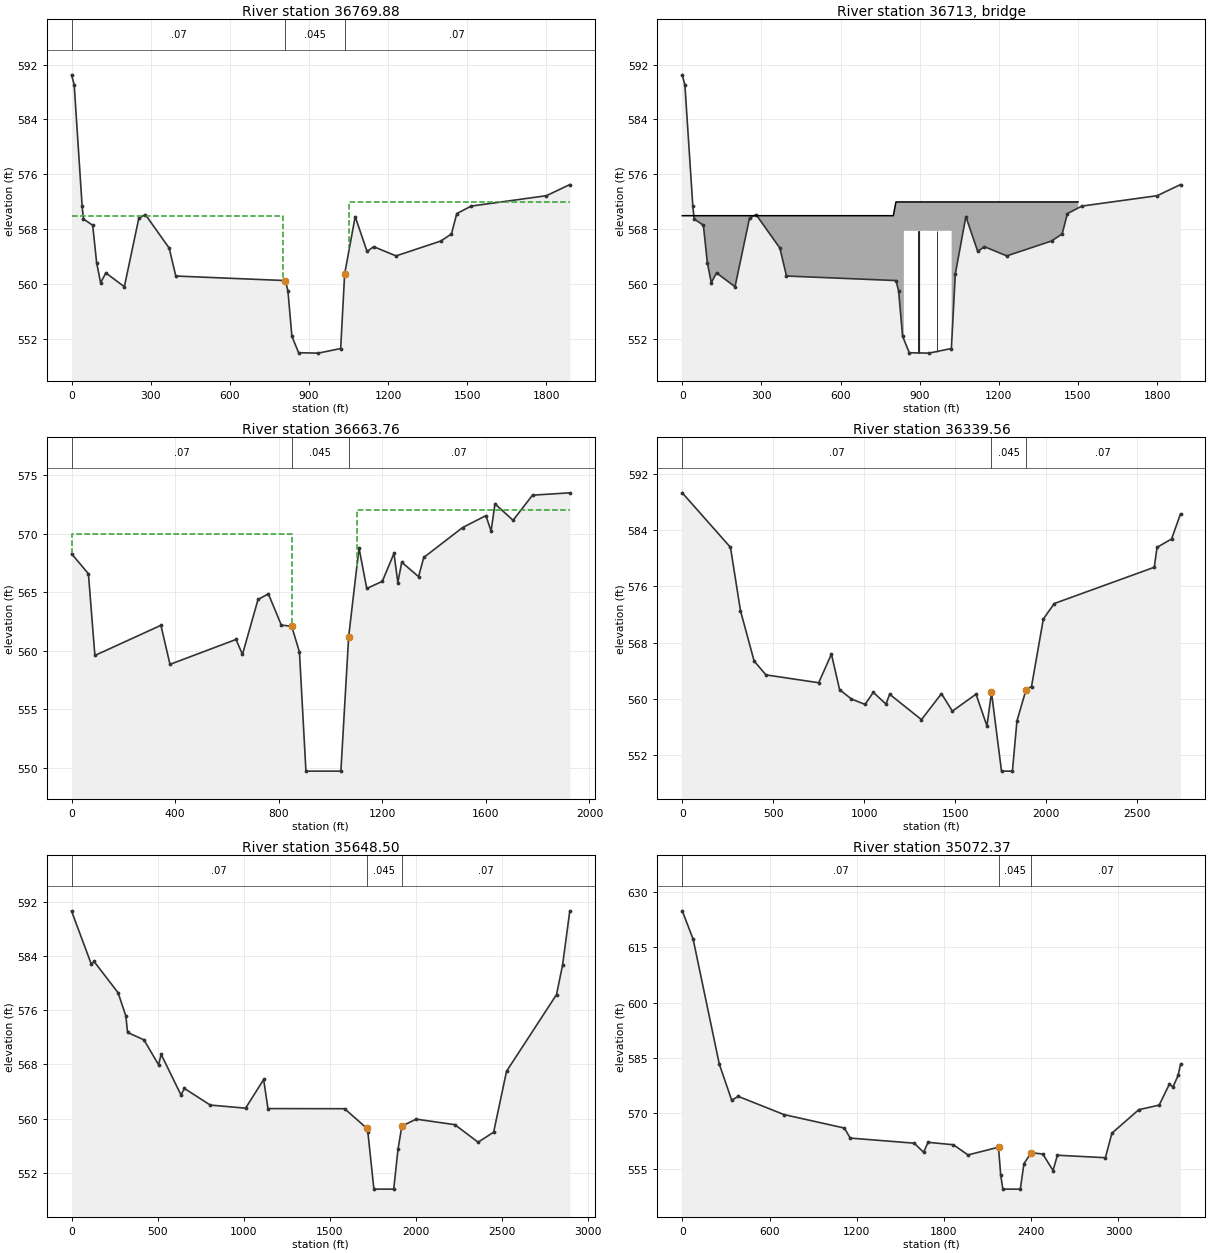
Type RM Length L Ch R = 1 ,36769.88,195.36,106.12,84.13
XS GIS Cut Line= 5
       2036144.8       344604.68      2036560.51       344596.83
        2036937.       344639.97      2037309.57       344616.44
      2038023.34        344518.4
#Sta/Elev= 30
       0   590.5      10     589   40.01  571.39      45  569.52      80  568.61
   95.01  563.16     110  560.24     130  561.67  200.01  559.66  255.01  569.66
     280  570.15  370.01  565.28     395  561.22     810  560.56     820  559.07
  835.01  552.47  860.44  550.06  935.01     550 1020.01  550.67 1035.01  561.52
 1075.01  569.87    1120  564.79    1145  565.49 1230.01  564.15 1400.01  566.32
    1440  567.35 1460.01  570.31 1515.01   571.4    1800  572.91 1888.52  574.53
#Mann= 3 , 0 , 0
       0     .07       0     810    .045       0 1035.01     .07       0
#XS Ineff= 2 , 0
       0     803     570    1052       0     572
Permanent Ineff=
       F       F
Bank Sta=810,1035.01
XS Rating Curve= 0
Exp/Cntr=0.3,0.1

Type RM Length L Ch R = 3 ,36713   ,,,
Node Photo=mvc-017f.gif
BEGIN DESCRIPTION:
PA 150 - Near Mill Hall
END DESCRIPTION:
Bridge Culvert-0,0,0,-1, 0
Deck Dist Width WeirC Skew NumUp NumDn MinLoCord MaxHiCord MaxSubmerge Is_Ogee
35,30,2.6,0, 8, 8, , , 0.95, 0, 2,2,,
       0     800     810     840     840    1021    1021    1500
     570     570     572     572     572     572     572     572
     500     500     500     500   567.8   567.8     500     500
       0     835     845     875     875    1076    1076    1500
     570     570     572     572     572     572     572     572
     500     500     500     500   567.8   567.8     500     500
Pier Skew, UpSta & Num, DnSta & Num=  ,895, 2 ,935, 2 , 0 , 0 , 0 ,,
       2       2
     540     570
       2       2
     540     570
Pier Skew, UpSta & Num, DnSta & Num=  ,965, 2 ,1005, 2 , 0 , 0 , 0 ,,
       2       2
     540     570
       2       2
     540     570
BR Coef=-1 , 0 , 0 ,, 0 ,,,0.8,0,,1,
WSPro=,,,, 1 ,,,, 0 ,,,, 0 ,,,,-1 ,-1 ,-1 , 0 , 0 , 0 , 0 , 0
BC Design=,, 0 ,, 0 ,,,,,,
BC HTab HWMax=575

Type RM Length L Ch R = 1 ,36663.76,287.58,324.2,381.59
XS GIS Cut Line= 4
      2036129.12       344828.22       2036917.4       344765.47
      2037282.12       344702.72      2038039.03       344604.68
#Sta/Elev= 30
       0  568.29      65  566.58   89.99  559.59     345  562.17     380  558.83
  634.99  560.96  659.99  559.68     720  564.38     760  564.86  809.99  562.19
  849.99  562.09     880  559.88     905   549.7 1039.99   549.7    1070  561.19
 1109.99  568.79    1140  565.32    1200  565.93    1245  568.32 1259.99  565.83
    1275  567.57    1340  566.33 1359.99  567.97 1509.99  570.53    1600  571.55
    1620  570.23    1635  572.56    1705  571.15 1779.99   573.3 1924.08   573.5
#Mann= 3 , 0 , 0
       0     .07       0  849.99    .045       0    1070     .07       0
#XS Ineff= 2 , 0
       0     853     570    1102       0     572
Permanent Ineff=
       F       F
Bank Sta=849.99,1070
XS Rating Curve= 0
Exp/Cntr=0.3,0.1

Type RM Length L Ch R = 1 ,36339.56,718.15,691.06,604.43
XS GIS Cut Line= 3
      2035356.52       345251.77      2036976.22       345036.07
      2038066.48       345216.48
#Sta/Elev= 30
       0  589.34     265  581.57     320  572.54  395.01  565.37  460.01  563.39
     750  562.27  820.01  566.35     865  561.28     930  559.95    1005  559.18
    1050   560.9    1120  559.23 1140.01  560.63    1315  557.01    1425  560.71
    1485  558.22    1615  560.64    1675  556.11 1700.01  560.89    1755  549.67
    1815  549.67    1840  556.83    1890  561.28 1920.01  561.73    1985  571.35
    2045  573.56    2595  578.73    2610  581.57    2690  582.76 2739.08  586.35
#Mann= 3 , 0 , 0
       0     .07       0 1700.01    .045       0    1890     .07       0
Bank Sta=1700.01,1890
XS Rating Curve= 0
Exp/Cntr=0.3,0.1

Type RM Length L Ch R = 1 ,35648.50,765.85,576.14,412.09
XS GIS Cut Line= 4
      2035042.78       345785.14      2037156.62       345679.25
      2037423.31       345663.56      2037901.77         345491.
#Sta/Elev= 30
       0  590.68  114.99   582.8     130  583.25     270  578.61  314.99  575.18
     325  572.73     420  571.65     505  567.96     520   569.5     635   563.5
     655  564.46     805     562 1009.99  561.54    1115  565.78    1140  561.48
 1584.99  561.46 1713.09  558.58 1719.99  557.98    1755  549.57    1870  549.57
    1895  555.47    1917  558.88 1999.99  559.92    2225   559.1    2360  556.51
    2450  557.99    2525     567 2814.99  578.33    2850  582.67 2892.27  590.72
#Mann= 3 , 0 , 0
       0     .07       0 1713.09    .045       0    1917     .07       0
Bank Sta=1713.09,1917
XS Rating Curve= 0
Exp/Cntr=0.3,0.1

Type RM Length L Ch R = 1 ,35072.37,1037.75,973.44,895.39
XS GIS Cut Line= 2
      2035160.43       347408.76      2038066.48       345592.97
#Sta/Elev= 30
       0  624.94      75  617.22     255  583.34     340  573.58  385.01  574.63
  700.01  569.69    1115  566.04    1155  563.32    1595  561.94 1660.01  559.47
 1690.01  562.18    1865  561.51 1965.01  558.75 2175.01  560.85    2190  553.31
    2205  549.48    2325  549.48    2350   556.4    2400  559.34    2480  558.99
    2550  554.53    2580  558.67    2910     558    2955  564.65    3140  571.03
    3280  572.26    3350  577.94    3375   577.2 3410.01  580.29 3426.69  583.31
#Mann= 3 , 0 , 0
       0     .07       0 2175.01    .045       0    2400     .07       0
Bank Sta=2175.01,2400
XS Rating Curve= 0
Exp/Cntr=0.3,0.1

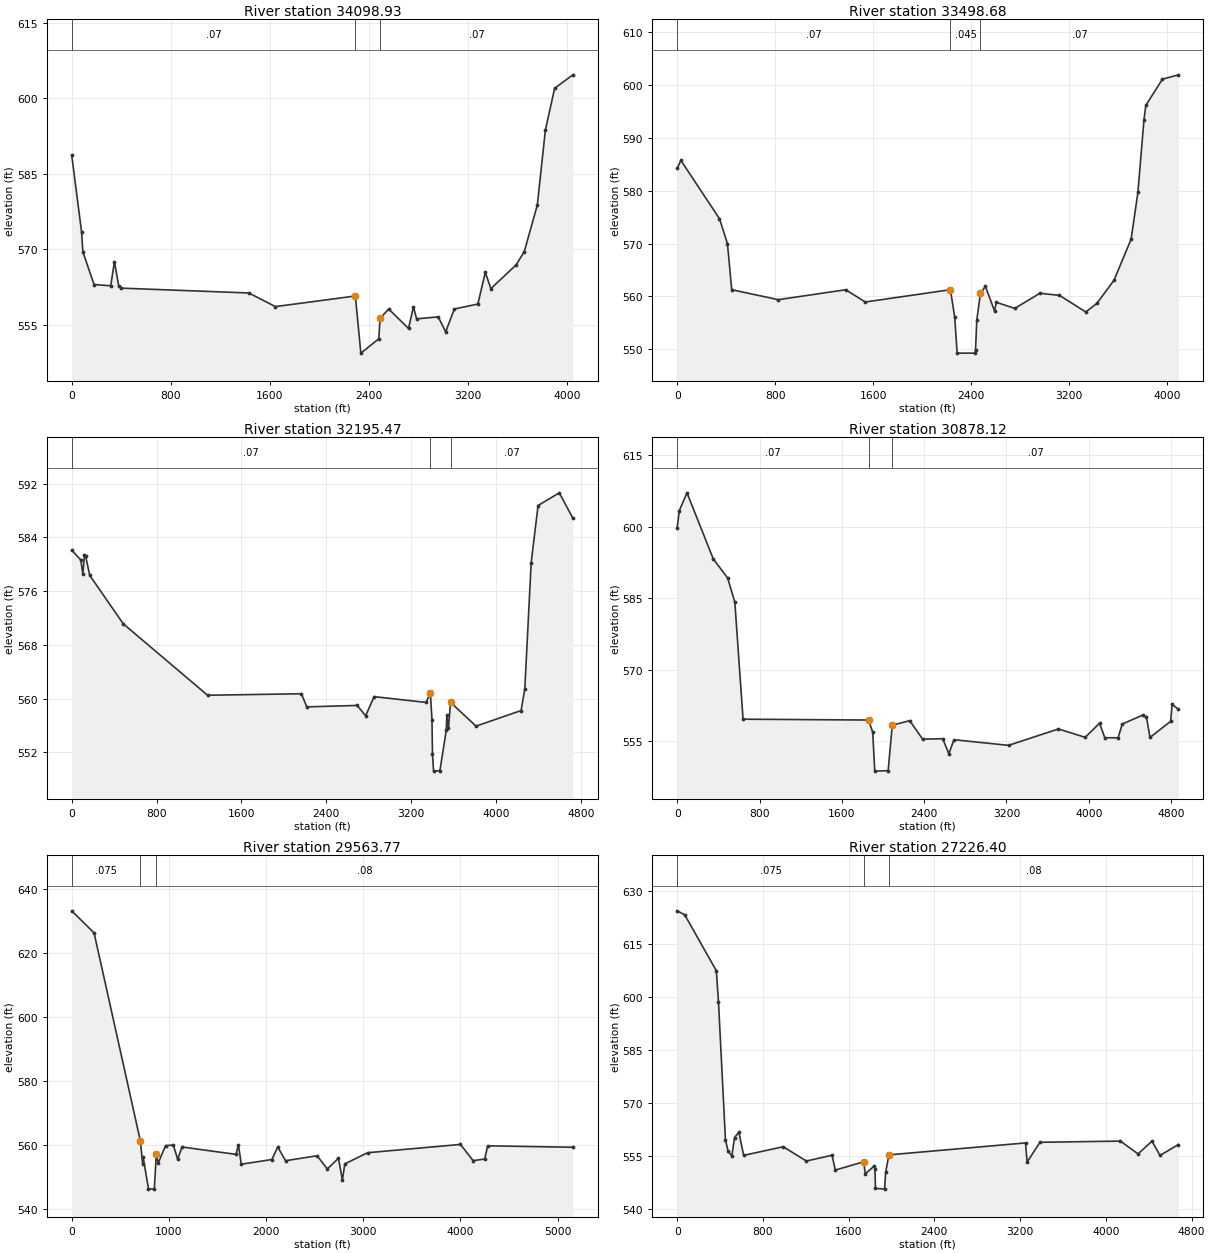
Type RM Length L Ch R = 1 ,34098.93,799.01,600.25,559.33
XS GIS Cut Line= 3
      2035803.61       348295.08      2037599.79       347079.33
      2038839.07       345667.48
#Sta/Elev= 30
       0  588.65      80  573.31   89.99  569.47  179.99  562.97  314.99  562.71
  344.99  567.54     380  562.59     400  562.25 1429.99  561.29    1645  558.58
  2290.5  560.69    2335  549.34 2479.99  552.19    2490  556.24    2560   558.1
 2719.99  554.24 2759.99  558.54 2784.99  556.15 2959.99  556.55    3020  553.56
 3089.99  558.11 3279.99  559.09    3340  565.38    3385  562.15    3590  566.89
    3655  569.52 3759.99  578.73 3824.99  593.61 3899.99  601.95 4047.54  604.62
#Mann= 3 , 0 , 0
       0     .07       0  2290.5    .045       0    2490     .07       0
Bank Sta=2290.5,2490
XS Rating Curve= 0
Exp/Cntr=0.3,0.1

Type RM Length L Ch R = 1 ,33498.68,1144.02,1303.2,1114.79
XS GIS Cut Line= 2
      2036901.71       349173.56       2039239.1       345816.51
#Sta/Elev= 30
       0  584.25      30  585.75     345  574.71  409.99     570  444.99  561.27
  824.99  559.38    1375  561.26 1534.99  558.94 2229.99  561.27 2264.99  556.03
    2285  549.26 2429.99  549.26    2435  549.87 2444.99  555.53 2474.99  560.55
 2514.99  561.92 2589.99  557.25 2604.99  558.88 2754.99  557.73    2960  560.59
    3120   560.2 3334.99  557.05    3425  558.67    3565  563.06    3705  570.85
    3760  579.68    3810  593.49    3825  596.17    3960  601.12 4090.62  601.95
#Mann= 3 , 0 , 0
       0     .07       0 2229.99    .045       0 2474.99     .07       0
Bank Sta=2229.99,2474.99
XS Rating Curve= 0
Exp/Cntr=0.3,0.1

Type RM Length L Ch R = 1 ,32195.47,659.24,1317.35,1728.83
XS GIS Cut Line= 3
      2037737.05       350142.25      2039227.33        347757.8
      2039980.31       346000.84
#Sta/Elev= 30
       0   582.1      85  580.66     105  578.53     120  581.44     130  581.29
     170  578.35     485  571.15    1280   560.5    2165  560.72    2215  558.77
    2690  558.98    2770  557.45    2850  560.29    3340  559.43    3380  560.86
    3395  556.88    3400  551.72    3410   549.2    3470  549.27    3530  555.31
 3535.01  557.58    3550  555.57 3570.01  559.44    3810   555.9    4235  558.22
    4270  561.44 4330.01  580.22    4395  588.75    4595  590.64 4723.37  586.85
#Mann= 3 , 0 , 0
       0     .07       0    3380    .045       0 3570.01     .07       0
Bank Sta=3380,3570.01
XS Rating Curve= 0
Exp/Cntr=0.3,0.1

Type RM Length L Ch R = 1 ,30878.12,866.8,1314.34,675.12
XS GIS Cut Line= 5
      2038654.75       349750.07      2039148.89       348926.49
       2039690.1        348424.5      2040803.89       348079.38
      2041352.94       346149.86
#Sta/Elev= 30
       0  599.74      20  603.31      95  607.06     350  593.24     490  589.22
     560  584.15  640.01  559.65    1860  559.47    1900  556.92    1920  548.77
 2050.01  548.86 2090.01   558.4    2260  559.34 2385.01  555.47    2580  555.56
    2640  552.43    2690  555.35 3220.01  554.17    3705   557.6    3965  555.85
    4105  558.81    4155  555.77    4285  555.75    4325  558.63    4525  560.51
    4560  560.15 4595.01  555.83    4795  559.19 4810.01  562.74 4870.78  561.75
#Mann= 3 , 0 , 0
       0     .07       0    1860    .045       0 2090.01     .07       0
Bank Sta=1860,2090.01
XS Rating Curve= 0
Exp/Cntr=0.3,0.1

Type RM Length L Ch R = 1 ,29563.77,2544.14,2337.37,1294.9
XS GIS Cut Line= 3
      2039105.75        350044.2      2041121.56       348106.84
      2041858.85       345863.57
#Sta/Elev= 30
       0   633.3     230   626.4   705.5   561.5     730  554.27  735.01  556.26
     790  546.41     850  546.33     870  557.17     890  554.48  964.99   559.9
    1045  560.13    1090  555.71    1135   559.5 1690.01  557.19    1715  560.11
    1745  554.12    2060  555.58    2120  559.54    2200  555.21    2525  556.76
    2630  552.63 2745.01  555.99    2785  549.16 2810.01  554.21 3045.01  557.71
    4000   560.3    4130  555.24    4250  555.73    4280  559.87 5157.19  559.41
#Mann= 3 , 0 , 0
       0    .075       0   705.5    .045       0     870     .08       0
Bank Sta=705.5,870
XS Rating Curve= 0
Exp/Cntr=0.3,0.1

Type RM Length L Ch R = 1 ,27226.40,1250.49,1265.71,1300.38
XS GIS Cut Line= 4
      2041372.55       350255.98      2041827.48        349377.5
      2041584.33       347965.65      2042094.16       345769.45
#Sta/Elev= 30
       0  624.29      70  623.17     365  607.39     385  598.67     450  559.74
     475  556.39     510  555.16     535  560.31     575  561.82     620  555.27
  989.29  557.71 1205.01  553.67    1445  555.31    1475  551.12 1740.13  553.46
 1755.01  550.04    1840  552.34    1845  551.45    1850  545.97    1935  545.74
    1945  550.47    1975  555.41    3250  558.78    3265  553.39    3385  558.96
    4135   559.3    4300  555.69    4430  559.29    4505  555.25 4676.52  558.33
#Mann= 3 , 0 , 0
       0    .075       0 1740.13     .05       0    1975     .08       0
Bank Sta=1740.13,1975
XS Rating Curve= 0
Exp/Cntr=0.3,0.1