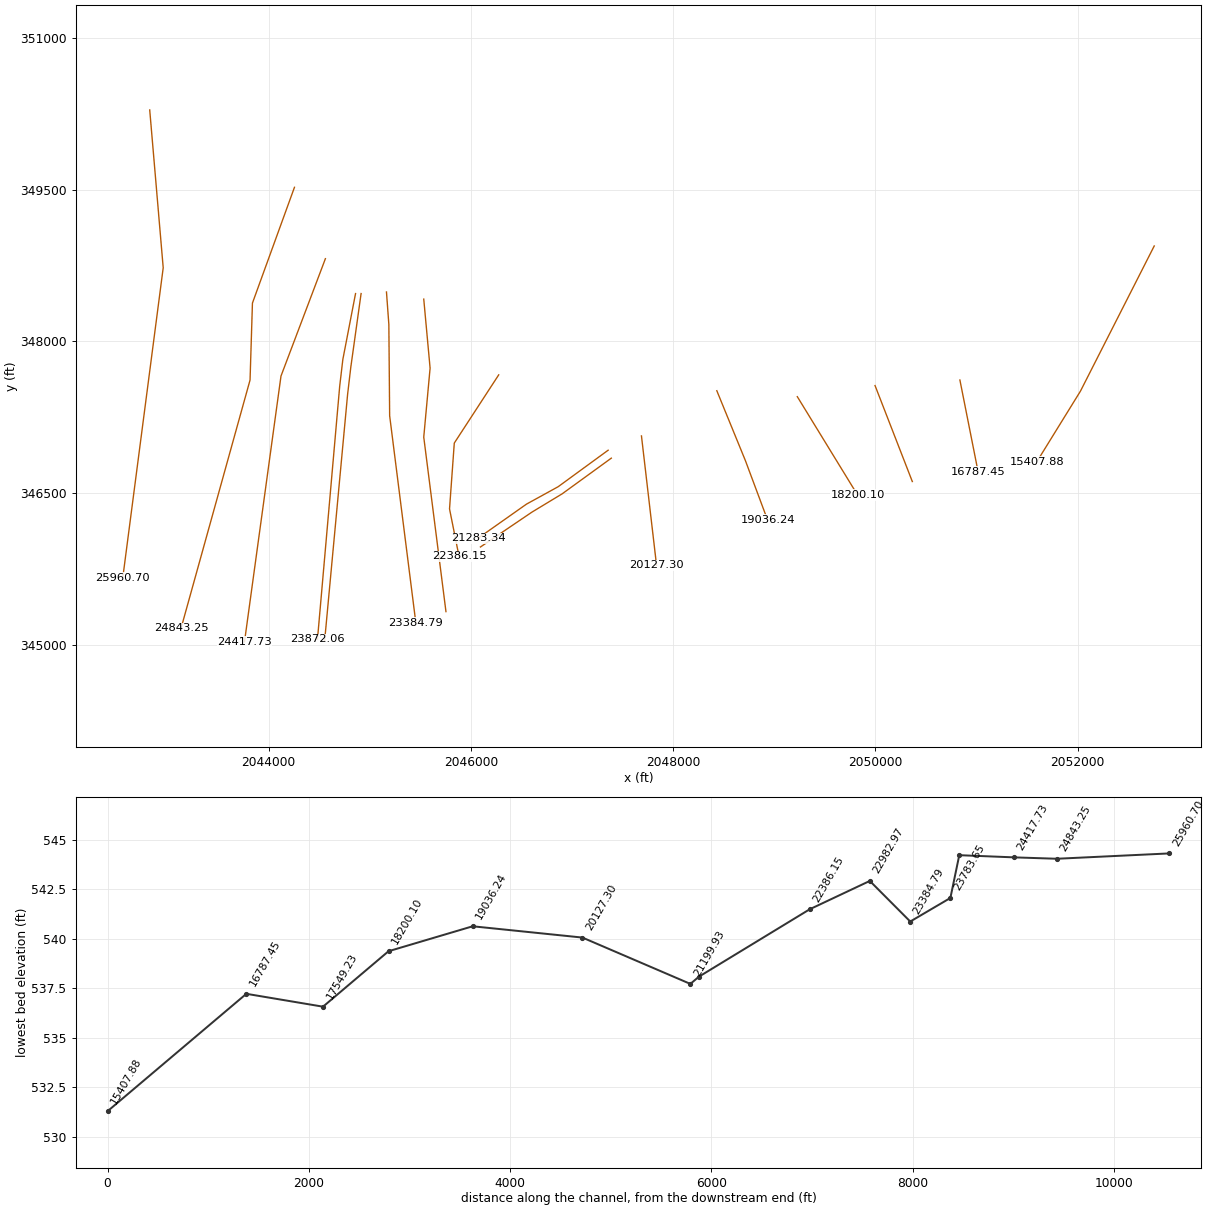
HEC-RAS study BaldEagle.prj: Bald Eagle Cr. for the WCDS Project

--- BaldEagle.g01 (geometry) --- (continued)

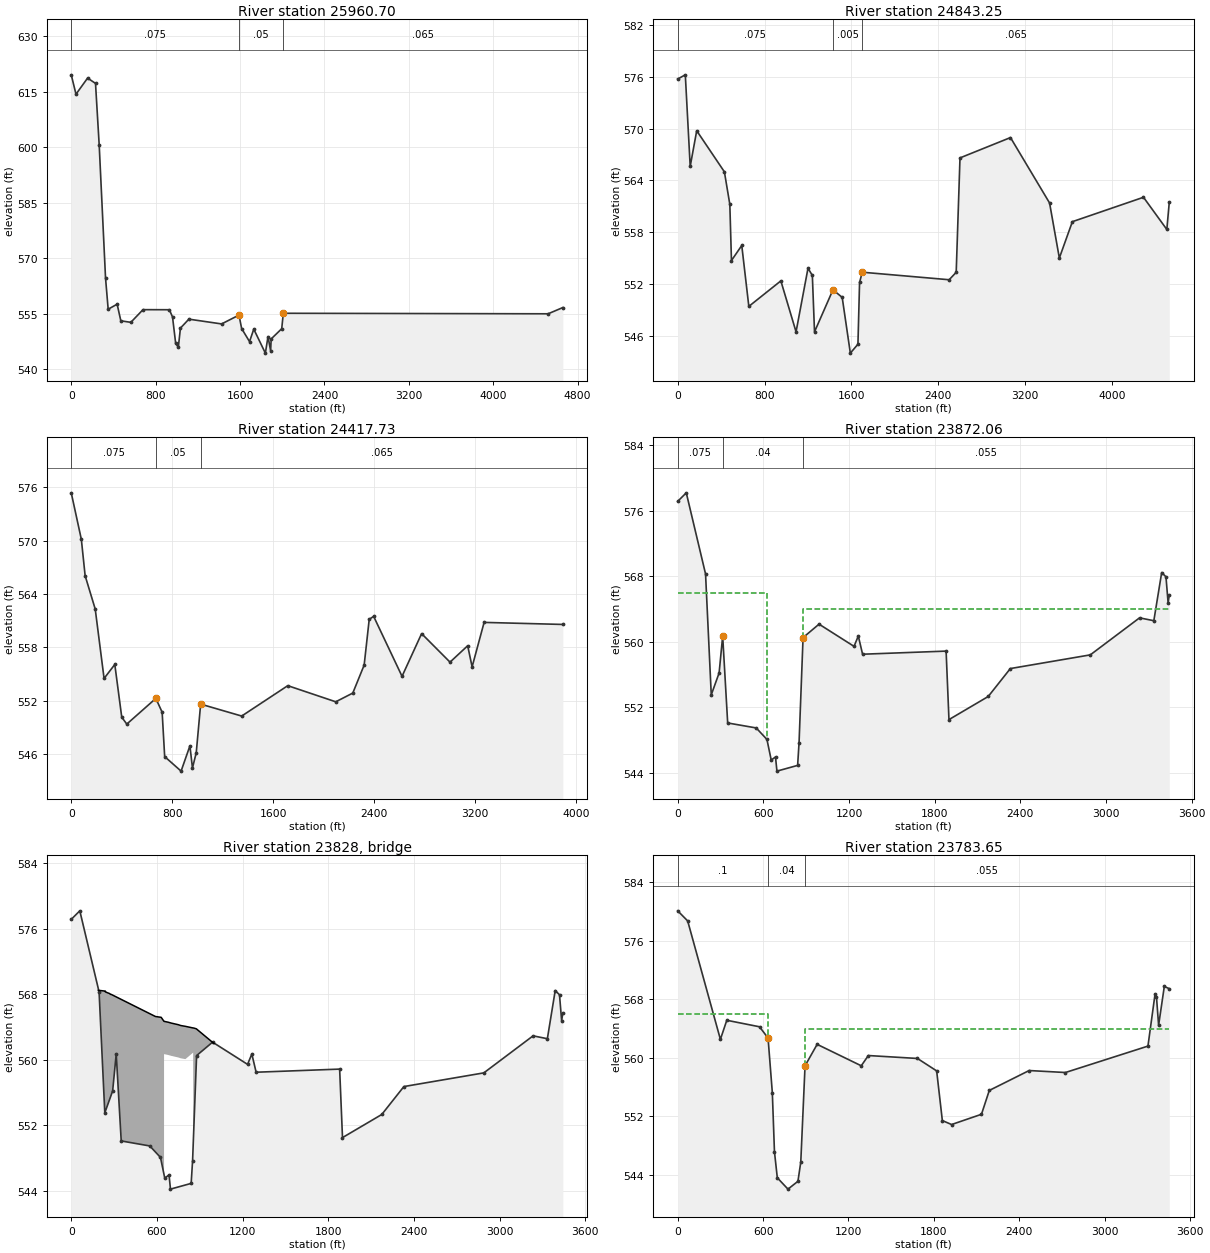
Type RM Length L Ch R = 1 ,25960.70,1383.81,1117.45,1033.11
XS GIS Cut Line= 3
      2042823.61       350287.35      2042956.95       348726.48
      2042556.93       345659.64
#Sta/Elev= 30
       0  619.61   44.99  614.37  154.99  618.73     230  617.29  264.99  600.59
     325  564.65     350   556.2     435  557.56     470  553.06     565  552.65
     680  556.08     930  556.06  959.99   554.1  989.99  546.93 1014.99   545.9
    1035  551.09    1115  553.51    1425  552.22 1589.99  554.61 1614.99  550.98
 1689.99  547.43    1730  550.81 1839.99  544.32 1864.99  548.79 1889.99  544.95
 1894.99  548.16 1994.99  550.93    2010   555.1 4519.99  554.96 4659.38  556.65
#Mann= 3 , 0 , 0
       0    .075       0 1589.99     .05       0    2010    .065       0
Bank Sta=1589.99,2010
XS Rating Curve= 0
Exp/Cntr=0.3,0.1

Type RM Length L Ch R = 1 ,24843.25,551.89,425.51,323.01
XS GIS Cut Line= 4
      2044255.07        349522.6      2043839.36       348377.44
      2043815.83       347616.61      2043133.43       345161.57
#Sta/Elev= 30
       0  575.73   69.99  576.21  114.99  565.63     175  569.75     430     565
     480  561.24     495  554.75  589.99  556.49     655  549.45     950   552.4
    1090  546.51 1199.99  553.86    1240  553.03    1260  546.51 1429.99  551.37
 1514.99  550.49    1590  544.05 1659.99  545.08    1675  552.22    1700   553.4
    2500  552.53    2565  553.39    2600  566.61 3064.99  568.96 3424.99   561.4
    3515  555.04 3634.99  559.24    4290  562.06 4504.99  558.34 4527.59   561.5
#Mann= 3 , 0 , 0
       0    .075       0 1429.99    .005       0    1700    .065       0
Bank Sta=1429.99,1700
XS Rating Curve= 0
Exp/Cntr=0.3,0.1

Type RM Length L Ch R = 1 ,24417.73,484.58,545.67,609
XS GIS Cut Line= 3
      2044560.97       348816.68      2044121.73       347655.83
      2043760.92       345028.23
#Sta/Elev= 30
       0  575.35      80  570.13     110  566.05     190   562.3     260  554.52
     345  556.09     400  550.17     440   549.4     670  552.28     720  550.73
     740  545.75     870  544.12     940  546.96     960  544.47     990  546.18
    1025  551.64    1350   550.3    1715  553.71    2095   551.9    2230  552.88
    2320  556.02    2360  561.15    2395  561.49    2620  554.76    2775  559.55
    3000  556.35    3140  558.19    3175  555.82    3270  560.81 3893.43  560.58
#Mann= 3 , 0 , 0
       0    .075       0     670     .05       0    1025    .065       0
Bank Sta=670,1025
XS Rating Curve= 0
Exp/Cntr=0.3,0.1

Type RM Length L Ch R = 1 ,23872.06,81.4,88.41,89.56
XS GIS Cut Line= 4
      2044859.02       348471.56      2044733.53       347820.55
      2044702.15       347553.86      2044482.53       345051.76
#Sta/Elev= 30
       0  577.16   59.99   578.2     195   568.3     235  553.54  289.99  556.21
  314.99  560.72     350  550.11  549.99   549.5     625   548.1     655  545.58
     685  545.96  694.99  544.23     840  544.93     850  547.72  878.03  560.53
     990  562.17    1235  559.46 1264.99  560.72    1295   558.5    1880  558.88
 1899.99  550.52    2175  553.34 2329.99  556.75    2890  558.42    3235  562.94
    3335  562.59    3390  568.47    3420  567.95    3435  564.78 3443.25  565.75
#Mann= 3 , 0 , 0
       0    .075       0  314.99     .04       0  878.03    .055       0
#XS Ineff= 2 , 0
       0     625     566  878.03       0     564
Permanent Ineff=
       F       F
Bank Sta=314.99,878.03
XS Rating Curve= 0
Exp/Cntr=0.3,0.1

Type RM Length L Ch R = 3 ,23828   ,,,
Node Photo=mvc-016f.gif
BEGIN DESCRIPTION:
PA Route 150 -High St. Bridge. Bridge
END DESCRIPTION:
Bridge Culvert-0,0,-1,-1, 0
Deck Dist Width WeirC Skew NumUp NumDn MinLoCord MaxHiCord MaxSubmerge Is_Ogee
20,50,2.6,0, 26, 26, , , 0.95, 0, 2,2,,
     190     239   239.1     240     254     269     275   275.9     276     280
     590     630     650   650.1     653     680     700     750     767     800
     854     855   856.9     857     876    1000
   568.5   568.4   568.3   568.3   568.2   568.1     568     568     568     568
   565.3   565.2   564.7   564.7   564.7   564.6   564.5   564.3   564.2   564.1
   563.9   563.9   563.9   563.9   563.8     562
     540     540     540     540     540     540     540     540     540     540
     540     540     540   560.7   560.7   560.6   560.5   560.3   560.2   560.1
   560.9     540     540     540     540     540
     200     254   254.1     255     269     284     290   290.9     291     295
     605     645     665   665.1     668     695     715     765     782     815
     869     870   871.9     872     891    1000
   568.5   568.4   568.3   568.3   568.2   568.1     568     568     568     568
   565.3   565.2   564.7   564.7   564.7   564.6   564.5   564.3   564.2   564.1
   563.9   563.9   563.9   563.9   563.8     562
     540     540     540     540     540     540     540     540     540     540
     540     540     540   560.7   560.7   560.6   560.5   560.3   560.2   560.1
   560.9     540     540     540     540     540
BR Coef=-1 , 0 , 0 ,, 0 ,,,0.8,-1,,1,
WSPro=,,,, 1 ,,,, 0 ,,,, 0 ,,,,-1 ,-1 ,-1 , 0 , 0 , 0 , 0 , 0
BC Design=,, 0 ,, 0 ,,,,,,
BC HTab HWMax=750

Type RM Length L Ch R = 1 ,23783.65,346.3,398.85,439.32
XS GIS Cut Line= 4
      2044913.93       348471.56      2044811.96       347742.11
      2044780.59       347475.43      2044553.12       345036.07
#Sta/Elev= 30
       0  580.11   69.99  578.73     300  562.54  344.99  565.15     575  564.26
  634.99  562.72  664.99  555.26     680  547.18     700  543.62     775  542.07
     845  543.14  864.99  545.77     895  558.93     980  561.86 1289.99  558.93
    1340  560.33    1685  559.93 1819.99  558.23    1860  551.44    1925   550.9
 2134.99   552.3    2190  555.56    2470  558.28    2725  558.01    3305  561.62
 3354.99  568.73    3365  568.36    3380  564.46    3420  569.77 3455.01  569.47
#Mann= 3 , 0 , 0
       0      .1       0  634.99     .04       0     895    .055       0
#XS Ineff= 2 , 0
       0  634.99     566     895       0     564
Permanent Ineff=
       F       F
Bank Sta=634.99,895
XS Rating Curve= 0
Exp/Cntr=0.3,0.1

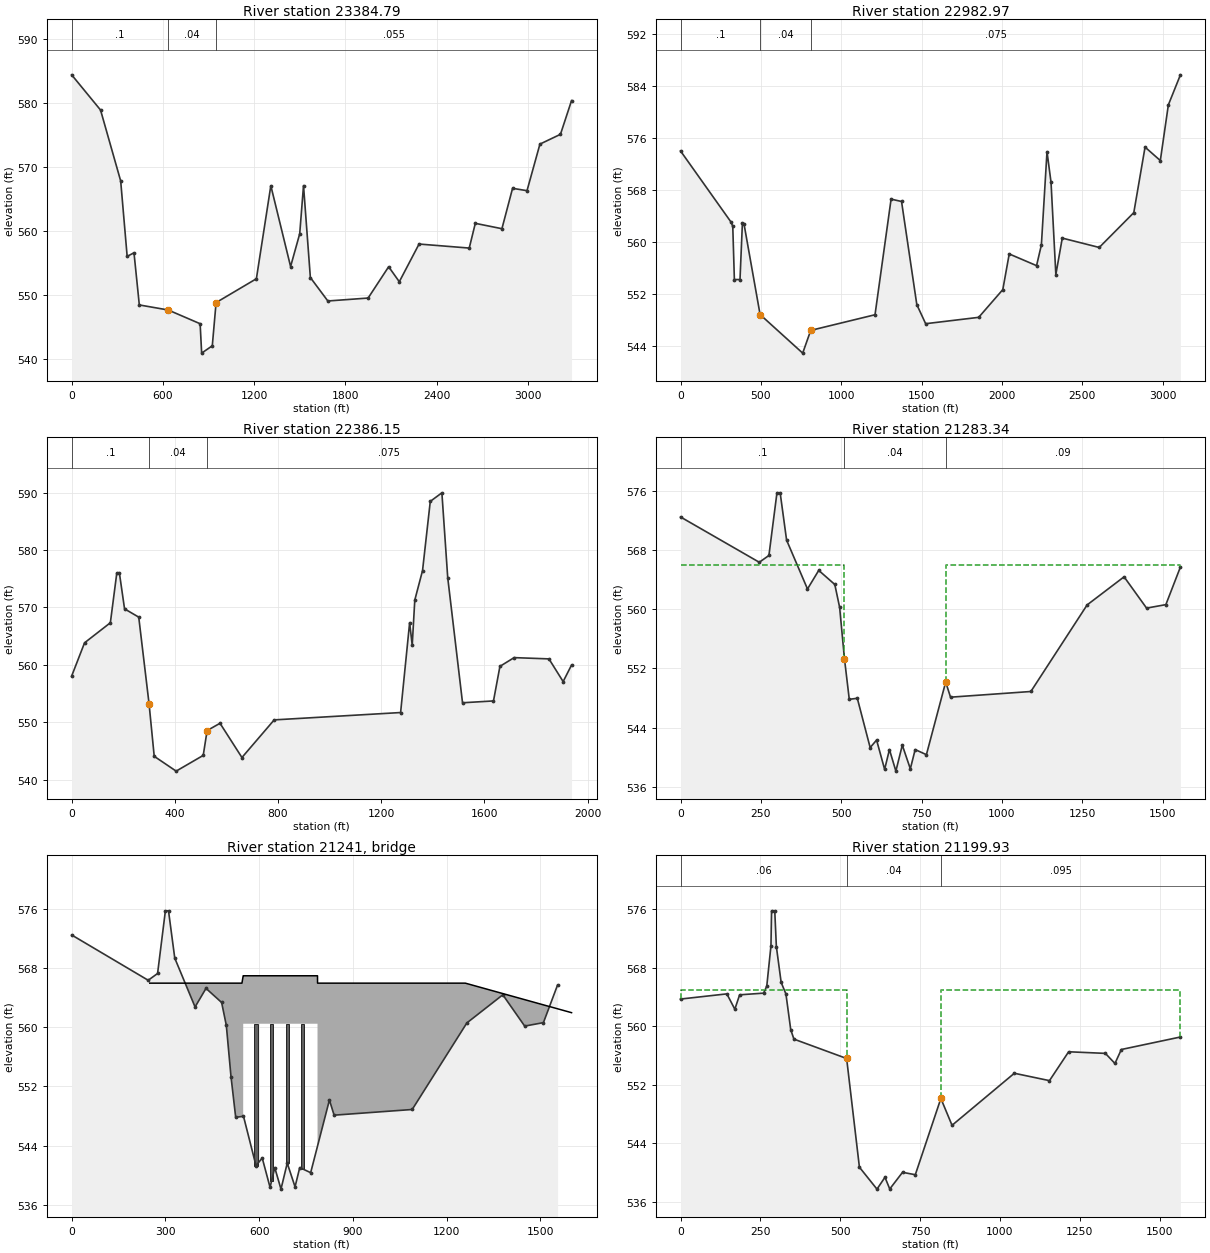
Type RM Length L Ch R = 1 ,23384.79,385.05,401.83,369.68
XS GIS Cut Line= 4
      2045164.92       348487.25      2045188.45       348165.66
       2045196.3       347263.65      2045455.14       345216.48
#Sta/Elev= 30
       0  584.43     190  578.92  322.45  567.82     365  556.02     410  556.58
  444.99  548.42     635  547.63     845  545.48     855  540.88     925  542.03
     950  548.79    1215  552.52    1310  567.08    1440  554.43    1500  559.56
    1525   567.1    1570  552.71    1685  549.04 1949.99   549.5    2085   554.4
    2155  552.05    2285  557.95    2615  557.32    2655  561.19    2830  560.35
    2900  566.67    2995   566.3    3080  573.59 3214.99  575.12 3287.96   580.4
#Mann= 3 , 0 , 0
       0      .1       0     635     .04       0     950    .055       0
Bank Sta=635,950
XS Rating Curve= 0
Exp/Cntr=0.3,0.1

Type RM Length L Ch R = 1 ,22982.97,897.38,596.82,454.75
XS GIS Cut Line= 4
      2045533.57       348416.66      2045596.32       347734.27
      2045533.57       347051.88      2045753.19       345326.29
#Sta/Elev= 30
       0  574.06     315  563.08  325.01  562.43     335  554.26     370  554.26
     385  562.99     395  562.81     495  548.87     760  542.93     810  546.43
    1210  548.84    1310  566.64    1375  566.28    1470   550.4    1525  547.46
 1855.01  548.44 2005.01  552.71 2045.01   558.2 2215.01   556.4 2245.01  559.58
 2280.01  573.95 2305.01  569.24 2335.01  555.03 2375.01  560.64 2605.01   559.2
    2820  564.56    2890  574.65    2985  572.58    3035  581.15 3110.04  585.78
#Mann= 3 , 0 , 0
       0      .1       0     495     .04       0     810    .075       0
Levee=-1,10,,0,,,0,0
Bank Sta=495,810
XS Rating Curve= 0
Exp/Cntr=0.3,0.1

Type RM Length L Ch R = 1 ,22386.15,1231.68,1102.81,1012.84
XS GIS Cut Line= 4
      2046274.79        347667.6      2045835.55       346993.05
      2045788.49       346342.03      2045882.61       345871.42
#Sta/Elev= 30
       0  558.05      50  563.84     150  567.33     175     576     185     576
     205  569.75     260  568.31     300  553.23     320  544.08     405   541.5
     510  544.24     525  548.56     575  549.83     660  543.87     785  550.42
 1275.01   551.7 1310.01  567.35    1320  563.42    1330  571.28 1360.01  576.41
 1390.01  588.46    1435  589.95 1457.67  575.17    1515   553.4 1635.01  553.72
    1660  559.74    1715  561.26    1850  561.04    1905  557.09  1937.6  559.97
#Mann= 3 , 0 , 0
       0      .1       0     300     .04       0     525    .075       0
Levee=-1,185,,0,,,0,0
Bank Sta=300,525
XS Rating Curve= 0
Exp/Cntr=0.3,0.1

Type RM Length L Ch R = 1 ,21283.34,87.33,83.41,105.85
XS GIS Cut Line= 4
       2047357.2       346922.46      2046863.06       346561.65
      2046549.32       346389.09      2046070.86       346051.82
#Sta/Elev= 30
       0  572.53     245  566.39     275  567.31  299.99   575.8     310   575.8
     330  569.39     395  562.77  429.99  565.29     480  563.38     495  560.28
     510  553.33     525  547.82     550  547.96  589.99  541.28     610   542.3
     635  538.33     650  541.01  669.99  538.09     690  541.61     715   538.4
     730  541.01     765  540.32     825  550.16     840  548.11    1090  548.88
    1265  560.61    1380  564.42    1450  560.18    1510  560.65  1555.3  565.75
#Mann= 3 , 0 , 0
       0      .1       0     510     .04       0     825     .09       0
Levee=-1,310,,0,,,0,0
#XS Ineff= 2 , 0
       0     510     566     825       0     566
Permanent Ineff=
       F       F
Bank Sta=510,825
XS Rating Curve= 0
Exp/Cntr=0.3,0.1

Type RM Length L Ch R = 3 ,21241   ,,,
Node Photo=mvc-013f.gif
BEGIN DESCRIPTION:
Upper Conrail Railroad Bridge
END DESCRIPTION:
Bridge Culvert-0,0,0,-1, 0
Deck Dist Width WeirC Skew NumUp NumDn MinLoCord MaxHiCord MaxSubmerge Is_Ogee
30,20,2.6,0, 29, 29, , , 0.95, 0, 2,2,,
     250     404     530     545     549   549.1     565     585     592     610
     625     631     645     664     672     690     705     712     730     745
     752     765     775   786.9     787     850    1200    1260    1600
     566     566     566     566     567     567     567     567     567     567
     567     567     567     567     567     567     567     567     567     567
     567     567     567     567     566     566     566     566     562
     540     540     540     540     540   560.5   560.5   560.5   560.5   560.5
   560.5   560.5   560.5   560.5   560.5   560.5   560.5   560.5   560.5   560.5
   560.5   560.5   560.5   560.5     540     540     540     540     540
     250     404     530     545     549   549.1     565     585     592     610
     625     631     645     664     672     690     705     712     730     745
     752     765     775   786.9     787     850    1200    1260    1600
     566     566     566     566     567     567     567     567     567     567
     567     567     567     567     567     567     567     567     567     567
     567     567     567     567     566     566     566     566     562
     540     540     540     540     540   560.5   560.5   560.5   560.5   560.5
   560.5   560.5   560.5   560.5   560.5   560.5   560.5   560.5   560.5   560.5
   560.5   560.5   560.5   560.5     540     540     540     540     540
Pier Skew, UpSta & Num, DnSta & Num=  ,590, 2 ,590, 2 , 0 , 0 , 0 ,,
      10       7
     538     561
      10       7
     538     561
Pier Skew, UpSta & Num, DnSta & Num=  ,640, 2 ,640, 2 , 0 , 0 , 0 ,,
      10       7
     538     561
      10       7
     538     561
Pier Skew, UpSta & Num, DnSta & Num=  ,690, 2 ,690, 2 , 0 , 0 , 0 ,,
      10       7
     538     561
      10       7
     538     561
Pier Skew, UpSta & Num, DnSta & Num=  ,740, 2 ,740, 2 , 0 , 0 , 0 ,,
      10       7
     538     561
      10       7
     538     561
BR Coef=-1 , 0 , 0 ,, 0 ,,,0.8,0,,1,
WSPro=,,,, 1 ,,,, 0 ,,,, 0 ,,,,-1 ,-1 ,-1 , 0 , 0 , 0 , 0 , 0
BC Design=,, 0 ,, 0 ,,,,,,
BC HTab HWMax=570

Type RM Length L Ch R = 1 ,21199.93,553.09,1072.63,1286.79
XS GIS Cut Line= 4
      2047388.58       346844.02      2046902.28       346491.06
      2046604.22       346310.66      2046094.39       345965.54
#Sta/Elev= 30
       0  563.73     145  564.44     170  562.34     185  564.31     260  564.54
     270   565.5   283.1  571.02     285   575.8     295   575.8     300  570.91
     315  566.01     330  564.42     345  559.54     355  558.25  520.01   555.6
     560  540.73     615  537.73     640  539.35     655  537.75     695  540.03
     735   539.7     815  550.13     850  546.46    1045  553.58    1155  552.57
    1215  556.52 1330.01   556.3    1360  554.92    1380  556.83 1564.95  558.54
#Mann= 3 , 0 , 0
       0     .06       0  520.01     .04       0     815    .095       0
Levee=-1,295,,0,,,0,0
#XS Ineff= 2 , 0
       0  520.01     565     815       0     565
Permanent Ineff=
       F       F
Bank Sta=520.01,815
XS Rating Curve= 0
Exp/Cntr=0.3,0.1

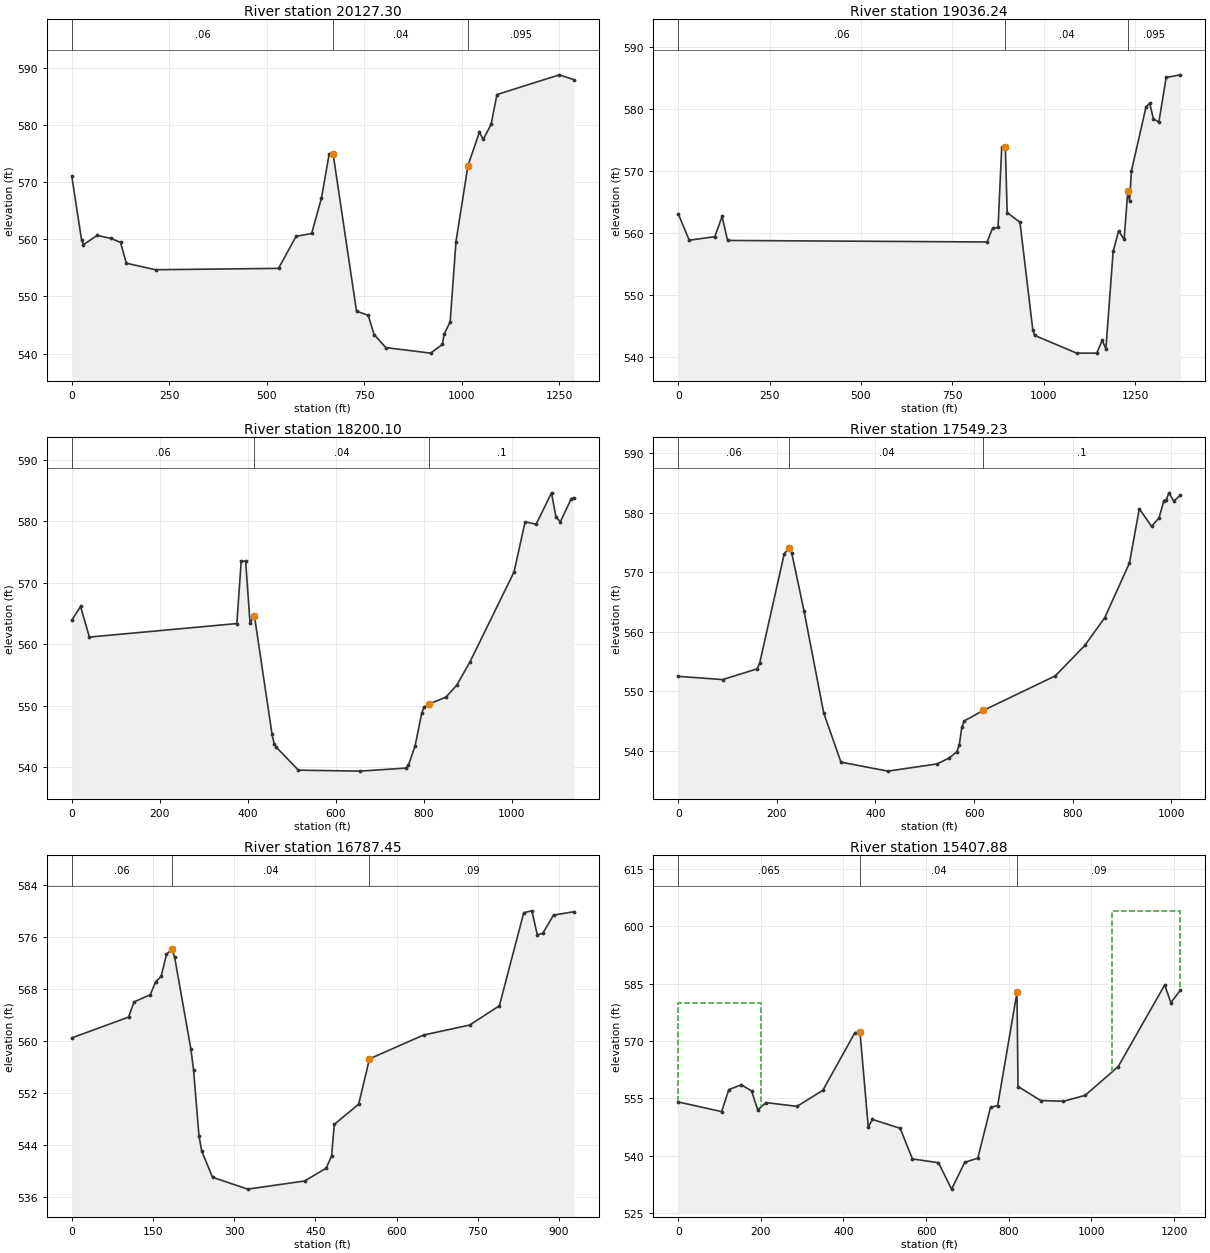
Type RM Length L Ch R = 1 ,20127.30,967.54,1091.06,1144.07
XS GIS Cut Line= 2
      2047686.63       347063.64      2047835.66       345785.14
#Sta/Elev= 30
       0  571.11      25  559.96      30  559.09      65   560.7     100   560.2
     125  559.48     140  555.83     215  554.69  530.01  554.93     575  560.54
     615  561.05     640  567.21     660     575     670     575     730  547.42
     760   546.7     775  543.33     805  541.04     920  540.07     950  541.59
     955  543.49     970  545.51     985  559.62  1015.7  572.95    1045  578.79
    1055  577.55    1075  580.18    1090   585.4    1250  588.86 1287.16  588.01
#Mann= 3 , 0 , 0
       0     .06       0     670     .04       0  1015.7    .095       0
Levee=-1,670,,0,,,0,0
Bank Sta=670,1015.7
XS Rating Curve= 0
Exp/Cntr=0.3,0.1

Type RM Length L Ch R = 1 ,19036.24,753.78,836.15,901.22
XS GIS Cut Line= 3
      2048431.78       347510.72      2048714.14       346820.49
      2048933.76       346232.22
#Sta/Elev= 30
       0  563.11   29.99  558.85   99.99  559.41  119.99  562.67  134.99  558.81
  844.99  558.56     860  560.78     875   560.9     885   573.8     895   573.8
     900   563.3  934.99  561.73  969.99  544.44  974.99   543.5 1089.99  540.64
    1145  540.64    1160   542.7 1169.99  541.32 1189.99  557.07    1205  560.35
 1219.99  558.98    1230  566.78 1234.99  565.14    1240  570.02 1279.99  580.37
 1289.99  580.93    1300  578.41 1314.99  577.91    1335  585.08 1373.68  585.51
#Mann= 3 , 0 , 0
       0     .06       0     895     .04       0    1230    .095       0
Levee=-1,895,,0,,,0,0
Bank Sta=895,1230
XS Rating Curve= 0
Exp/Cntr=0.3,0.1

Type RM Length L Ch R = 1 ,18200.10,720.98,650.86,608.04
XS GIS Cut Line= 2
       2049227.9        347451.9      2049824.01       346479.29
#Sta/Elev= 30
       0  563.94      20  566.17      40  561.19     375  563.39     385  573.54
     395  573.54     405  563.53     415  564.64     455   545.4     460  543.79
     465  543.25     515  539.54  655.01  539.38     760  539.88     765  540.36
     780  543.48     795  548.76     800  549.74  812.67  550.34     850  551.41
     875  553.39  905.01  557.19    1005  571.81    1030  579.95    1055  579.54
    1090  584.66    1100  580.75    1110  579.95 1135.01  583.71 1140.75  583.81
#Mann= 3 , 0 , 0
       0     .06       0     415     .04       0  812.67      .1       0
Levee=-1,395,,0,,,0,0
Bank Sta=415,812.67
XS Rating Curve= 0
Exp/Cntr=0.3,0.1

Type RM Length L Ch R = 1 ,17549.23,822.3,761.78,696.9
XS GIS Cut Line= 2
      2049996.57       347561.71      2050365.22       346612.63
#Sta/Elev= 30
       0   552.5   90.01  551.96  160.01  553.76     165  554.66     215  573.12
     225  574.01     230   573.3     255  563.52     295  546.36     330  538.09
  425.01  536.58     525  537.79     550  538.81     565  539.85     570     541
     575  543.94     580  545.01  618.94  546.78  765.01   552.6  825.01  557.75
     865  562.37     915  571.54     935  580.66  960.01  577.69     975  579.14
     985  582.03     990   582.2     995  583.33    1005  581.94 1018.16  582.92
#Mann= 3 , 0 , 0
       0     .06       0     225     .04       0  618.94      .1       0
Levee=-1,225,,0,,,0,0
Bank Sta=225,618.94
XS Rating Curve= 0
Exp/Cntr=0.3,0.1

Type RM Length L Ch R = 1 ,16787.45,1904.75,1379.57,1202.47
XS GIS Cut Line= 2
      2050835.83       347616.61      2051016.24       346706.76
#Sta/Elev= 30
       0  560.51     105  563.72     115  566.05     145  567.16     155  569.17
     165  569.97     175  573.39     185  574.16     190  572.96     220  558.83
     225   555.6     235  545.45  239.99  543.12     260  539.06     325  537.23
     430  538.48  469.99  540.45     480  542.36     485   547.2     530  550.31
     550  557.29     650  560.96     735  562.49     790  565.46     835   579.8
     850  580.08     860  576.39  869.99   576.6     890  579.42  927.56  579.94
#Mann= 3 , 0 , 0
       0     .06       0     185     .04       0     550     .09       0
Levee=-1,185,,0,,,0,0
Bank Sta=185,550
XS Rating Curve= 0
Exp/Cntr=0.3,0.1

Type RM Length L Ch R = 1 ,15407.88,407.83,593.53,487.81
XS GIS Cut Line= 3
      2052757.51       348942.18      2052028.06        347506.8
      2051596.66       346808.72
#Sta/Elev= 30
       0  554.07     105  551.55   122.5  557.29   152.5  558.55   177.5  556.96
   192.5  551.98   212.5  553.91   287.5  552.92     350  557.11   427.5  572.14
     440   572.3     460   547.5     470   549.5   537.2   547.2   566.8   539.2
     630   538.2   661.6   531.3   693.6   538.3   725.2   539.4     756   552.7
   773.2   553.1     820   582.7   822.5   558.1   877.5  554.45   932.5  554.25
     985   555.8    1065  563.31  1177.5  584.62  1192.5  580.05 1215.36   583.2
#Mann= 3 , 0 , 0
       0    .065       0     440     .04       0     820     .09       0
Levee=-1,430,,-1,820,,0,0
#XS Ineff= 2 , 0
       0     200     580    1050       0     604
Permanent Ineff=
       F       F
Bank Sta=440,820
XS Rating Curve= 0
Exp/Cntr=0.3,0.1