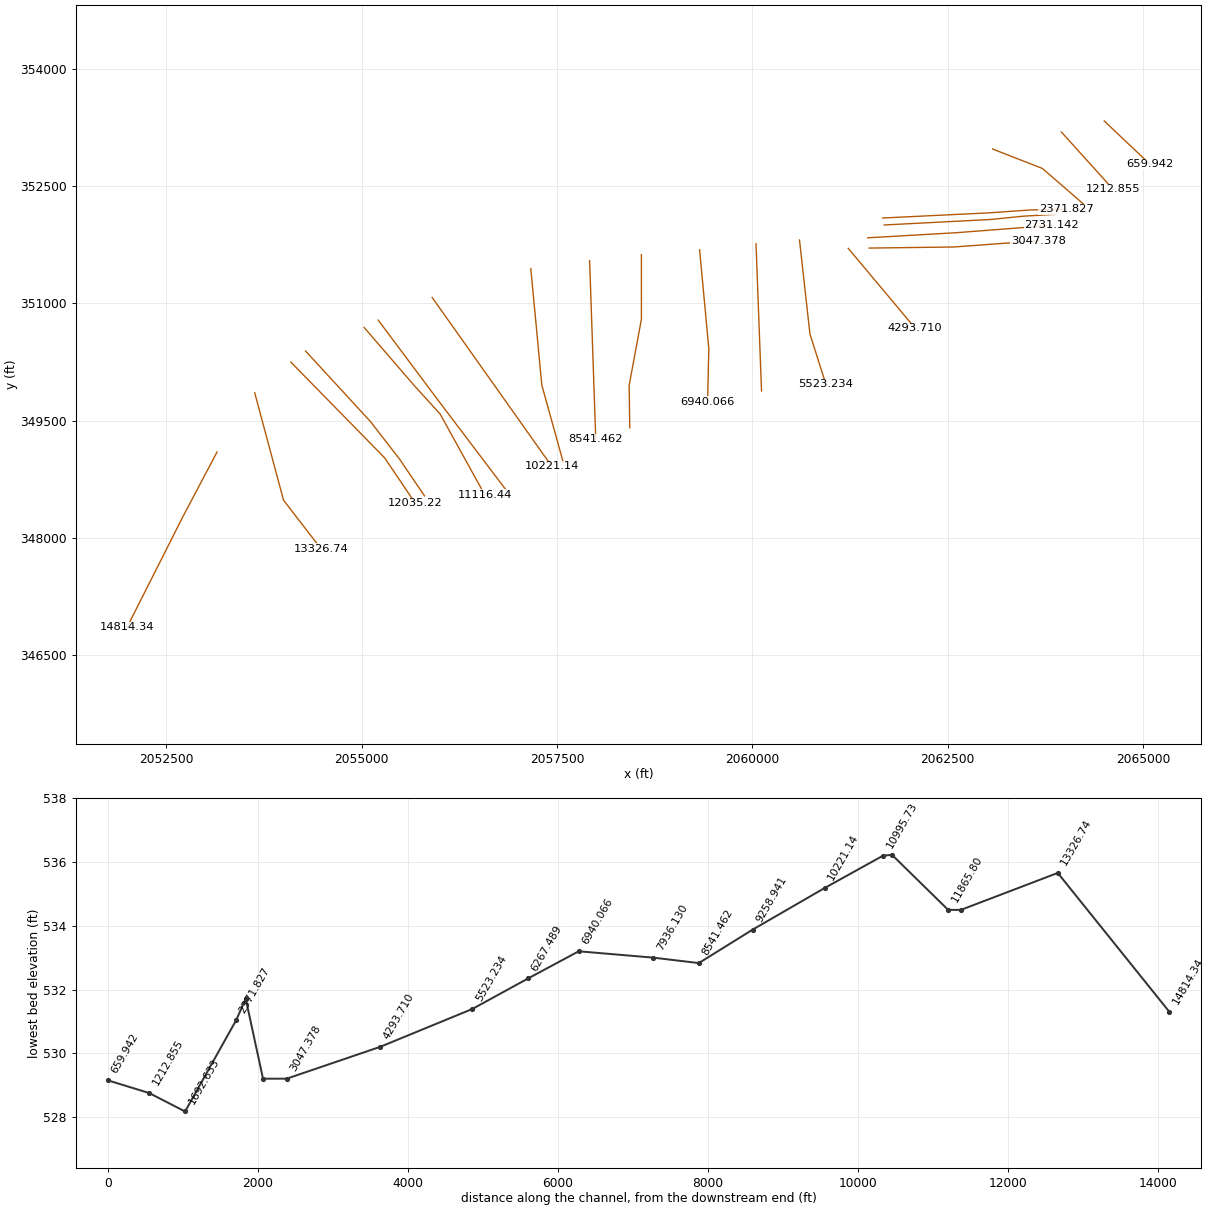
HEC-RAS study BaldEagle.prj: Bald Eagle Cr. for the WCDS Project

--- BaldEagle.g01 (geometry) --- (continued)

Type RM Length L Ch R = 3 ,15100   ,,,
Node Photo=mvc-012f.gif
BEGIN DESCRIPTION:
U.S. Route 220 Bridge - Upper End
END DESCRIPTION:
Bridge Culvert-0,0,0,-1, 0
Deck Dist Width WeirC Skew NumUp NumDn MinLoCord MaxHiCord MaxSubmerge Is_Ogee
240,210,2.6,0, 23, 23, , , 0.95, 0, 2,2,,
       0     230     270     310     350     390     430     440  440.04     504
   566.8     630   693.6     756  819.96     820     830     870     910     950
     990    1030    1268
     578   580.2   581.3   582.2   583.2   584.3   585.6   585.7   585.7   587.5
   589.3   591.1   592.9   594.5   596.4   596.4   596.6   597.8     599   600.4
   602.4   604.4     608
     530     530     530     530     530     530     530     530   574.5   576.4
     577   579.8   581.3   583.2     585     530     530     530     530     530
     530     530     530
       0     130     170     210     250     290     330     340  340.04     404
   466.8     530   593.6     656  719.96     720     730     770     810     850
     890     930    1268
     576   580.2   581.3   582.2   583.2   584.3   585.6   585.7   585.7   587.5
   589.3   591.1   592.9   594.5   596.4   596.4   596.6   597.8     599   600.4
   602.4   604.4     608
     530     530     530     530     530     530     530     530   574.5   576.4
     577   579.8   581.3   583.2     585     530     530     530     530     530
     530     530     530
Pier Skew, UpSta & Num, DnSta & Num=  ,470, 2 ,370, 2 , 0 , 0 , 0 ,,
       7       7
   531.3     585
       7       7
   531.3     585
Pier Skew, UpSta & Num, DnSta & Num=  ,550, 2 ,450, 2 , 0 , 0 , 0 ,,
       7       7
   531.3     585
       7       7
   531.3     585
Pier Skew, UpSta & Num, DnSta & Num=  ,630, 2 ,530, 2 , 0 , 0 , 0 ,,
       7       7
   531.3     585
       7       7
   531.3     585
Pier Skew, UpSta & Num, DnSta & Num=  ,710, 2 ,610, 2 , 0 , 0 , 0 ,,
       7       7
   531.3     585
       7       7
   531.3     585
Pier Skew, UpSta & Num, DnSta & Num=  ,790, 2 ,690, 2 , 0 , 0 , 0 ,,
       7       7
   531.3     585
       7       7
   531.3     585
BR Coef=-1 , 0 , 0 ,, 0 ,,,0.8,-1,,1,
WSPro=,,,, 1 ,,,, 0 ,,,, 0 ,,,,-1 ,-1 ,-1 , 0 , 0 , 0 , 0 , 0
BC Design=,, 0 ,, 0 ,,,,,,
BC HTab HWMax=580

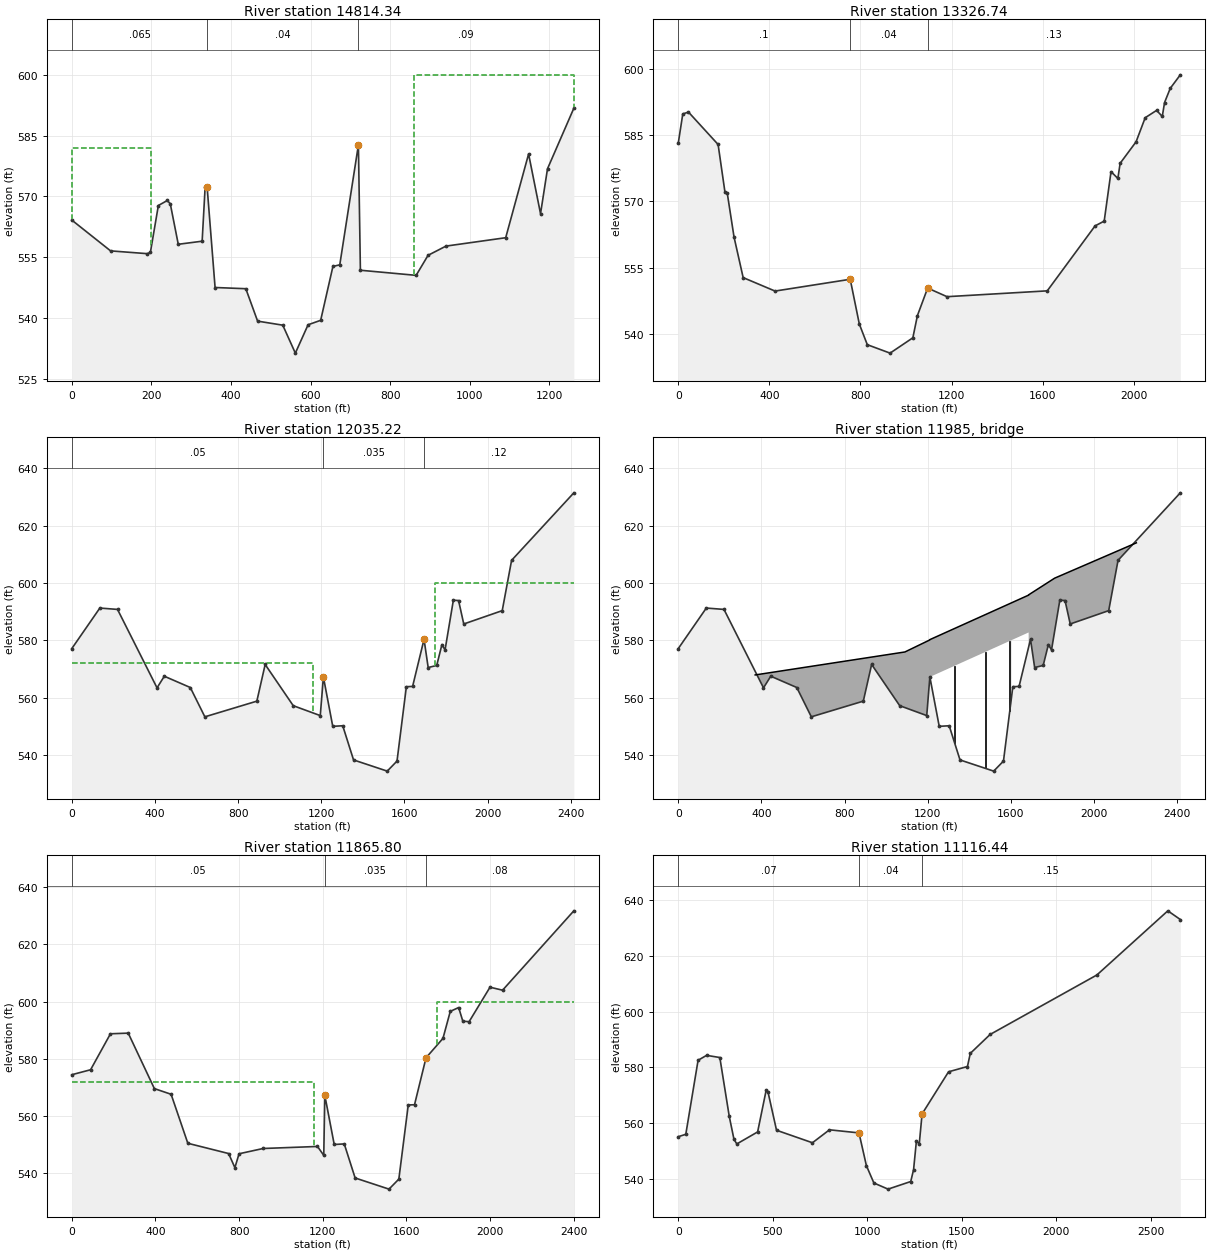
Type RM Length L Ch R = 1 ,14814.34,1187.4,1487.6,1934.2
XS GIS Cut Line= 3
      2053149.69       349099.05      2052710.45       348267.63
      2051996.68       346855.78
#Sta/Elev= 30
       0  564.15    97.5  556.54  189.99  555.85   197.5  556.17   217.5  567.74
     240  568.98   247.5  568.15   267.5  558.17   327.5  558.93     335   572.3
     340   572.3     360   547.5   437.2   547.2   466.8   539.2     530   538.2
   561.6   531.3   593.6   538.3   625.2   539.4     656   552.7   673.2   553.1
     720   582.7     725  551.76     865   550.5     895  555.45     940  557.72
    1090  559.79  1147.5  580.46 1177.49  565.72    1195  576.81 1261.17  591.76
#Mann= 3 , 0 , 0
       0    .065       0     340     .04       0     720     .09       0
Levee=-1,340,,-1,720,,0,0
#XS Ineff= 2 , 0
       0     200     582     860       0     600
Permanent Ineff=
       F       F
Bank Sta=340,720
XS Rating Curve= 0
Exp/Cntr=0.3,0.1

Type RM Length L Ch R = 1 ,13326.74,1213.11,1291.52,1379.69
XS GIS Cut Line= 3
      2053632.07       349855.96      2054000.72       348483.33
      2054479.18       347863.69
#Sta/Elev= 30
       0  583.15      20  589.82      45  590.23  175.01   582.9  205.01  572.15
  215.01  571.94  245.01  561.93     285  552.76  425.01  549.71     755  552.38
  795.01  542.24  830.01  537.57  930.01  535.66    1030  539.13 1050.01  544.16
 1095.01  550.39 1180.01  548.44 1620.01  549.76    1830  564.47    1870  565.55
    1900  576.75    1930  575.21 1940.01  578.64    2010  583.51 2050.01  588.96
    2100  590.62    2125  589.25    2135   592.4    2160  595.61 2204.14  598.67
#Mann= 3 , 0 , 0
       0      .1       0     755     .04       0 1095.01     .13       0
Levee=-1,210,,0,,,0,0
Bank Sta=755,1095.01
XS Rating Curve= 0
Exp/Cntr=0.3,0.1

Type RM Length L Ch R = 1 ,12035.22,205.2,169.43,145.04
XS GIS Cut Line= 3
      2054094.84       350248.13      2055294.91       349024.54
      2055687.09       348444.11
#Sta/Elev= 30
       0  577.16     135  591.29     220  590.82     410   563.5     445  567.55
     570  563.62     640  553.41     890  558.87     930  571.64    1065  557.29
    1195  553.84    1210   567.3    1255   550.1    1303   550.3    1355   538.4
    1517   534.5    1564     538    1609   563.9    1639     564    1694   580.4
 1713.87  570.58    1755   571.3    1780  578.58    1795  576.69    1835  594.02
    1860  593.91    1885  585.74    2070  590.39    2115  607.91 2414.37  631.42
#Mann= 3 , 0 , 0
       0     .05       0    1210    .035       0    1694     .12       0
Levee=-1,965,,0,,,0,0
#XS Ineff= 2 , 0
       0    1160     572    1746       0     600
Permanent Ineff=
       F       F
Bank Sta=1210,1694
XS Rating Curve= 0
Exp/Cntr=0.3,0.1

Type RM Length L Ch R = 3 ,11985   ,,,
Node Photo=mvc-010f.gif
BEGIN DESCRIPTION:
New Bridge
END DESCRIPTION:
Bridge Culvert-0,0,-1,-1, 0
Deck Dist Width WeirC Skew NumUp NumDn MinLoCord MaxHiCord MaxSubmerge Is_Ogee
50,50,2.6,0, 8, 8, , , 0.95, 0, 2,2,,
     370    1090    1210  1210.1    1685  1685.1    1810    2203
     568     576   580.2   580.3   595.8   595.9   601.7     614
     533     533     540   567.3   582.8     550     533     533
     370    1090    1210  1210.1    1685  1685.1    1810    2203
     568     576   580.2   580.3   595.8   595.9   601.7     614
     533     533     540   567.3   582.8     550     533     533
Pier Skew, UpSta & Num, DnSta & Num=  ,1329, 2 ,1329, 2 , 0 , 0 , 0 ,,
       4       4
     530     575
       4       4
     530     575
Pier Skew, UpSta & Num, DnSta & Num=  ,1476, 2 ,1476, 2 , 0 , 0 , 0 ,,
       4       4
     530     578
       4       4
     530     578
Pier Skew, UpSta & Num, DnSta & Num=  ,1594, 2 ,1594, 2 , 0 , 0 , 0 ,,
       4       4
     530     582
       4       4
     530     582
BR Coef=-1 , 0 , 0 ,, 0 ,,,0.8,-1,,1,
WSPro=,,,, 1 ,,,, 0 ,,,, 0 ,,,,-1 ,-1 ,-1 , 0 , 0 , 0 , 0 , 0
BC Design=,, 0 ,, 0 ,,,,,,
BC HTab HWMax=580

Type RM Length L Ch R = 1 ,11865.80,812.44,749.36,769.95
XS GIS Cut Line= 4
      2054283.09       350389.32      2055114.51       349487.31
        2055491.         349001.      2055804.74       348538.23
#Sta/Elev= 30
       0  574.48      90  576.22     185  588.79     270  589.02     395  569.63
     475  567.65     555  550.52     750  546.94     780     542     800  546.86
     915   548.7    1175  549.41    1205   546.3    1210   567.3    1255   550.1
    1303   550.3    1355   538.4    1517   534.5    1564     538    1609   563.9
    1639     564    1694   580.4    1775  587.18    1810  596.62    1850  597.96
    1870  593.19    1900  593.02    2000  605.07    2060  604.02 2400.85  631.76
#Mann= 3 , 0 , 0
       0     .05       0    1210    .035       0    1694     .08       0
Levee=-1,225,,0,,,0,0
#XS Ineff= 2 , 0
       0    1160     572    1746       0     600
Permanent Ineff=
       F       F
Bank Sta=1210,1694
XS Rating Curve= 0
Exp/Cntr=0.3,0.1

Type RM Length L Ch R = 1 ,11116.44,164.62,120.71,95.79
XS GIS Cut Line= 4
      2055032.15        350691.3      2055683.17       349938.31
      2056004.75       349585.35      2056577.34         348550.
#Sta/Elev= 30
       0  555.05      40  555.92     105   582.5     150  584.26  220.01  583.49
     270  562.31     295  554.07     310  552.46     420  556.77     465  571.68
     475  571.06  520.01  557.37     710  552.88     800  557.53  956.17  556.42
   995.4  544.66    1035  538.43    1110  536.23    1230  538.96 1245.01  543.25
    1260  553.54    1275  552.44    1290  563.24    1430  578.36    1530  580.26
    1545  584.97    1650  591.77    2215  613.14 2590.01  636.16 2656.02  633.04
#Mann= 3 , 0 , 0
       0     .07       0  956.17     .04       0    1290     .15       0
Levee=-1,465,,0,,,0,0
Bank Sta=956.17,1290
XS Rating Curve= 0
Exp/Cntr=0.3,0.1

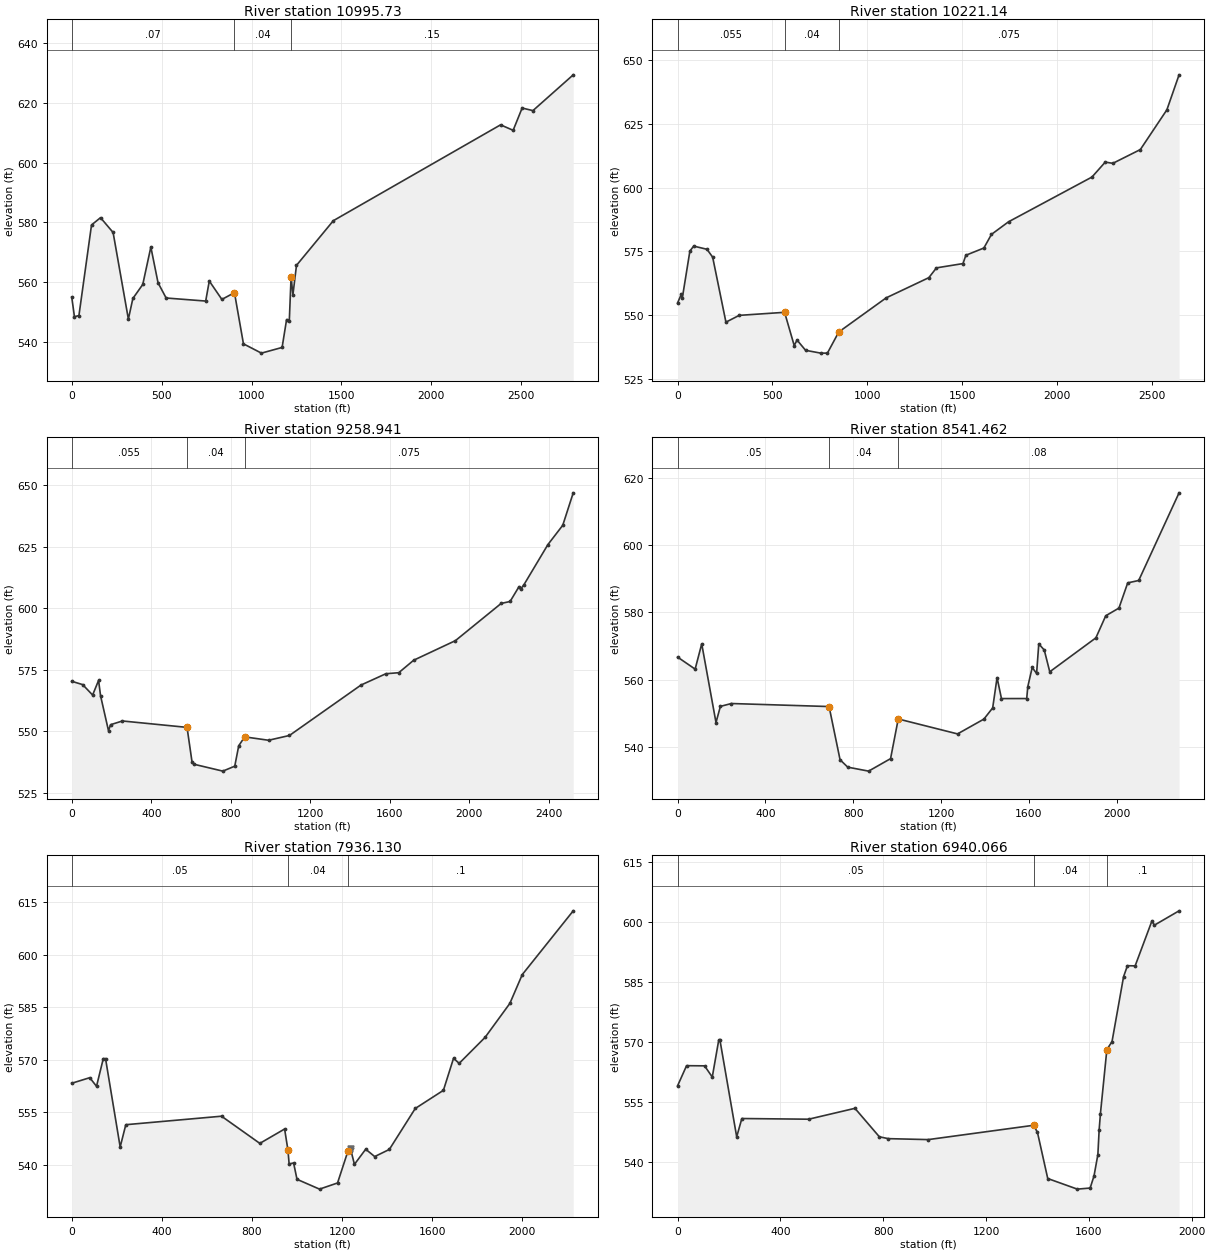
Type RM Length L Ch R = 1 ,10995.73,744.47,774.59,704.79
XS GIS Cut Line= 3
      2055212.55       350785.42      2055957.69       349789.28
      2056891.08       348557.84
#Sta/Elev= 30
       0  554.97      15  548.39      40  548.78     110   579.1     160  581.54
     230  576.59     315  547.59     340   554.5     395  559.18     440   571.7
     480  559.74     525  554.65     745  553.63     765  560.33     835  554.18
     905  556.44     955  539.31 1055.01   536.2    1170   538.1    1195  547.45
    1210  546.92    1220  561.78    1230  555.69    1250  565.58    1455  580.53
    2385  612.61 2455.01  610.78 2505.01  618.24    2565  617.37 2789.21  629.35
#Mann= 3 , 0 , 0
       0     .07       0     905     .04       0    1220     .15       0
Levee=-1,440,,0,,,0,0
Bank Sta=905,1220
XS Rating Curve= 0
Exp/Cntr=0.3,0.1

Type RM Length L Ch R = 1 ,10221.14,1162.44,962.2,764.27
XS GIS Cut Line= 2
      2055902.79       351075.63      2057432.29       348918.65
#Sta/Elev= 30
       0  554.82      20   558.3      25  556.77      65  575.17      85   577.1
     155  575.86     185  572.78     255  547.32     325  549.98  564.28  551.17
  614.99  538.16     630   540.3     675  536.29     755  535.19     790  535.19
     850  543.47 1099.99  556.84    1325  564.75 1364.99  568.58    1505  570.26
    1520  573.52    1615  576.35    1655  581.69    1745  586.62 2184.99  604.15
    2255     610 2294.99  609.52    2440  614.91    2580  630.48 2644.23  644.18
#Mann= 3 , 0 , 0
       0    .055       0  564.28     .04       0     850    .075       0
Levee=-1,85,,0,,,0,0
Bank Sta=564.28,850
XS Rating Curve= 0
Exp/Cntr=0.3,0.1

Type RM Length L Ch R = 1 ,9258.941,736.02,717.48,708.27
XS GIS Cut Line= 3
      2057165.61       351444.28      2057306.79         349954.
      2057581.32       348965.71
#Sta/Elev= 30
       0  570.35   54.99     569     105  564.77     135   570.7     145  564.47
  184.99  550.24     195  552.72     255  554.24     580  551.64     605  537.66
     615  536.67     760  533.88  819.99  535.89  839.99  544.17     870  547.79
     990  546.41    1095  548.35 1454.99  568.82    1580  573.41    1645  573.84
    1720   578.9    1930  586.85    2160  601.95    2205  602.75    2250  608.79
    2260  607.96    2275   609.6    2395  625.82    2470  633.69 2522.66  646.86
#Mann= 3 , 0 , 0
       0    .055       0     580     .04       0     870    .075       0
Levee=-1,135,,0,,,0,0
Bank Sta=580,870
XS Rating Curve= 0
Exp/Cntr=0.3,0.1

Type RM Length L Ch R = 1 ,8541.462,654.81,605.33,515.88
XS GIS Cut Line= 2
      2057918.59       351546.25      2057997.02       349263.76
#Sta/Elev= 30
       0  566.72   80.01  563.14     110  570.65     175  547.27  195.01  552.07
     245  552.92  690.01  552.02  740.01  536.21  775.01  534.01     870  532.83
     970  536.54    1005  548.33    1275  543.89    1395  548.29 1435.01  551.61
    1455  560.61    1475  554.39    1590   554.4    1595  557.94    1615  563.63
    1635  561.86    1645  570.64 1670.01  568.81    1695  562.35    1905  572.43
    1950     579 2010.01  581.28    2050  588.77    2100  589.48 2283.84  615.53
#Mann= 3 , 0 , 0
       0     .05       0  690.01     .04       0    1005     .08       0
Levee=-1,110,,0,,,0,0
Bank Sta=690.01,1005
XS Rating Curve= 0
Exp/Cntr=0.3,0.1

Type RM Length L Ch R = 1 ,7936.130,819.89,996.06,1053.25
XS GIS Cut Line= 4
      2058581.37       351620.76      2058581.37       350797.19
       2058424.5       349950.08      2058432.34       349408.87
#Sta/Elev= 30
       0  563.27      80  564.86     110   562.4     140   570.3     150  570.33
     215  545.05     240  551.42     665  553.85     835  546.08     945  550.19
     960  544.09  964.99  540.22     985  540.47    1000  535.81    1100     533
    1180  534.76 1226.05  543.84    1240  543.93    1255  540.08    1305  544.41
    1345  542.31 1409.99  544.35    1525  556.06    1650  561.25 1694.99  570.41
    1720  568.96    1835  576.39    1945   586.1    2000  594.33 2226.35  612.57
#Mann= 3 , 0 , 0
       0     .05       0     960     .04       0 1226.05      .1       0
Levee=-1,145,,-1,1240.02,544.39,0,0
Bank Sta=960,1226.05
XS Rating Curve= 0
Exp/Cntr=0.3,0.1

Type RM Length L Ch R = 1 ,6940.066,695.73,672.58,686.51
XS GIS Cut Line= 3
      2059326.51       351683.51      2059444.17       350420.69
      2059428.48        349738.3
#Sta/Elev= 30
       0  559.02      35  564.06     105  564.02     135  561.22     160   570.4
     165   570.4     230  546.27     250  550.85     510  550.68     690   553.4
  784.99  546.28     820  545.82     975  545.58    1385  549.16    1400  547.39
 1440.01  535.85 1555.01   533.2    1605  533.47    1620  536.49    1635  541.82
    1640  548.02    1645   552.1    1670   568.1    1690  570.06    1735  586.31
    1750  589.05 1780.01  589.01    1845  600.19 1855.01  599.19 1950.86  602.77
#Mann= 3 , 0 , 0
       0     .05       0    1385     .04       0    1670      .1       0
Levee=-1,165,,0,,,0,0
Bank Sta=1385,1670
XS Rating Curve= 0
Exp/Cntr=0.3,0.1

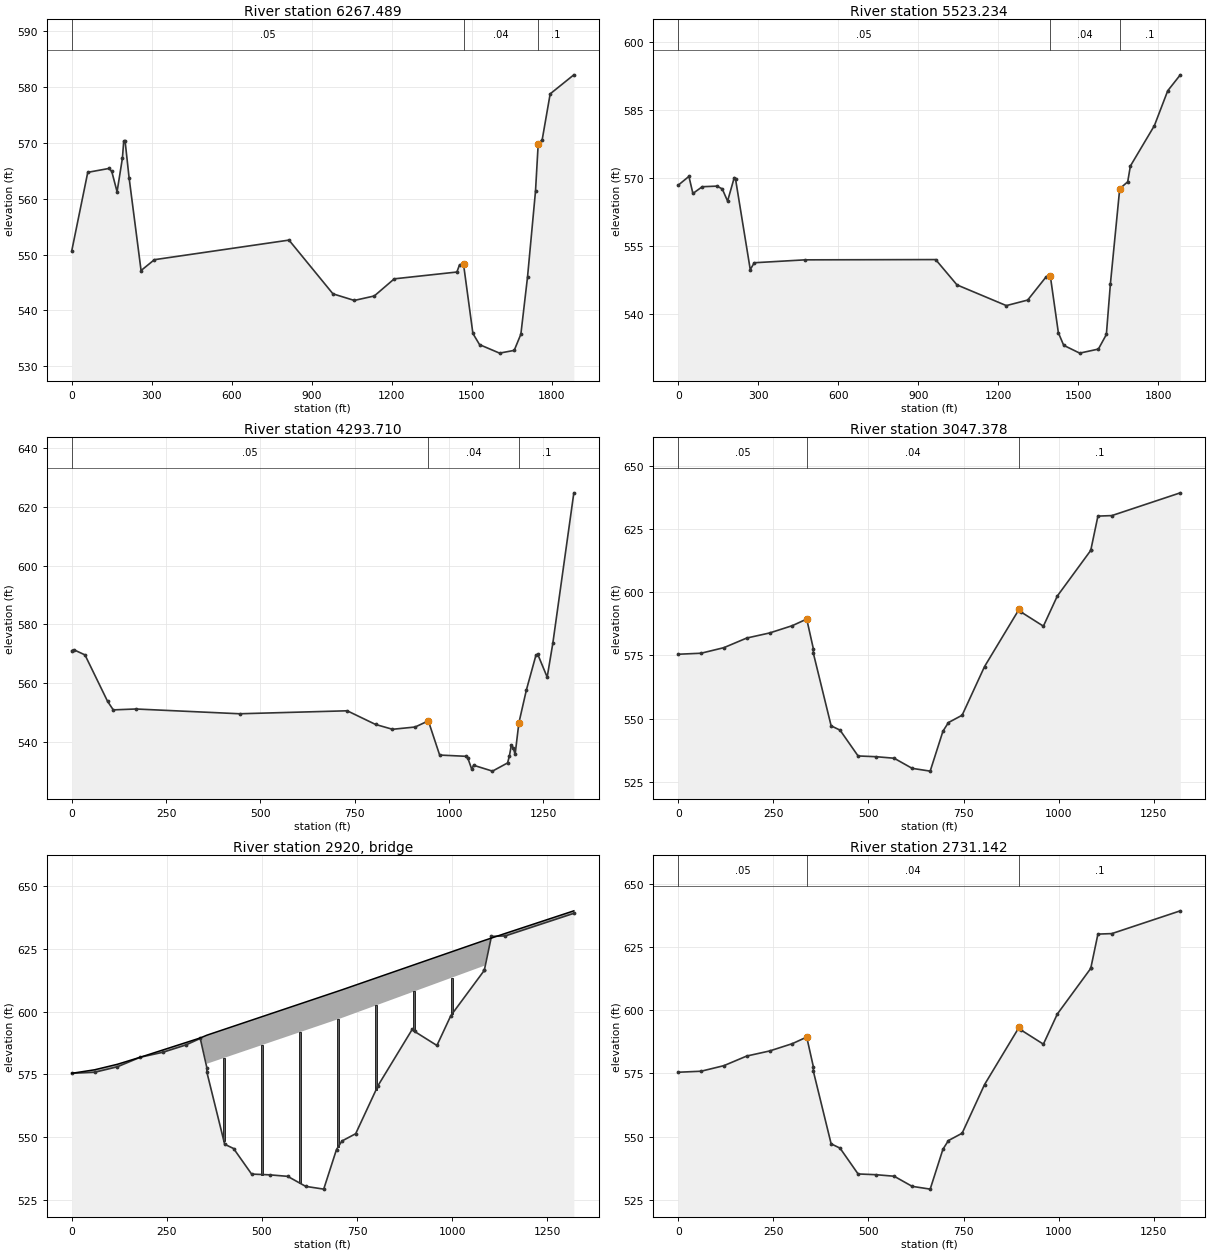
Type RM Length L Ch R = 1 ,6267.489,640.02,744.26,796.78
XS GIS Cut Line= 2
      2060048.12       351761.95      2060118.71       349879.49
#Sta/Elev= 30
       0  550.69      60  564.74  140.01  565.44  150.01   564.9     170  561.26
     190  567.27  195.01  570.36     200  570.36     215   563.8     260  547.15
  310.01  549.09     815   552.6  980.01  542.97    1060  541.79 1135.01  542.59
    1210  545.66 1445.01  546.88    1455  548.19    1470  548.24 1505.01  535.88
 1530.01  533.87 1605.01  532.35 1660.01  532.84    1685  535.74    1710  545.99
    1740  561.41    1750   569.8    1765  570.58    1795   578.8 1883.78  582.21
#Mann= 3 , 0 , 0
       0     .05       0    1470     .04       0    1750      .1       0
Levee=-1,200,,0,,,0,0
Bank Sta=1470,1750
XS Rating Curve= 0
Exp/Cntr=0.3,0.1

Type RM Length L Ch R = 1 ,5523.234,1081.77,1229.52,1305.95
XS GIS Cut Line= 3
      2060605.02       351809.01      2060738.36       350608.94
      2060942.29       349965.77
#Sta/Elev= 30
       0  568.39      40  570.32   55.01  566.56      90  568.05  145.01  568.18
     165  567.57     185  564.88     210  570.06     215  569.67     270  549.79
     285   551.3     475  551.94     965     552    1045  546.42    1230  541.86
    1310  543.08    1380  548.26    1395  548.33    1425  535.89    1445  533.11
    1505  531.39 1575.01  532.28    1605   535.5    1620  546.59 1655.01   567.6
    1685  569.14 1695.01  572.61 1785.01  581.51    1835  589.19 1882.18   592.7
#Mann= 3 , 0 , 0
       0     .05       0    1395     .04       0 1655.01      .1       0
Levee=-1,210,,0,,,0,0
Bank Sta=1395,1655.01
XS Rating Curve= 0
Exp/Cntr=0.3,0.1

Type RM Length L Ch R = 1 ,4293.710,936.79,1246.33,1616.91
XS GIS Cut Line= 2
      2061228.58       351703.12      2062083.53       350683.45
#Sta/Elev= 30
       0  571.13       5  571.45      35  569.67      95  553.87     110     551
     170   551.3     445  549.68     730  550.69     805  546.06     850  544.41
     910  545.18     945  547.27     975  535.66    1045  535.23    1050   534.5
    1060  530.87    1065  532.19    1115   530.2    1155  532.98    1160  535.42
    1165  539.07    1170  538.09 1175.01  535.88    1185  546.59    1205  557.82
    1230  569.47    1235  569.87    1260  562.11    1275  573.67 1330.66  624.71
#Mann= 3 , 0 , 0
       0     .05       0     945     .04       0    1185      .1       0
Levee=-1,5,,0,,,0,0
Bank Sta=945,1185
XS Rating Curve= 0
Exp/Cntr=0.3,0.1

Type RM Length L Ch R = 1 ,3047.378,295.93,316.24,289.68
XS GIS Cut Line= 3
      2061496.69       351706.28      2062584.71       351720.35
      2063663.35       351800.08
#Sta/Elev= 29
       0   575.4      60   575.8     120     578     180   581.8     240   583.8
     300   586.7   337.8   589.3   355.2   577.6  355.26   575.8     402   547.1
   425.4   545.4   472.8   535.2   520.2   534.9   567.6   534.3     615   530.3
   662.4   529.2     696     545   710.4   548.4   746.4   551.3   805.2   570.5
   895.8   593.1   901.2   592.1     960   586.5   996.6   598.4  1084.8   616.5
 1084.86   616.7  1103.4     630    1140   630.2    1320   639.2
#Mann= 3 , 0 , 0
       0     .05       0   337.8     .04       0   895.8      .1       0
Bank Sta=337.8,895.8
XS Rating Curve= 0
Exp/Cntr=0.3,0.1

Type RM Length L Ch R = 3 ,2920    ,,,
Node Photo=mvc-001f.gif
BEGIN DESCRIPTION:
U.S. Route 220 Bridge - Lower End
END DESCRIPTION:
Bridge Culvert-0,0,0,-1, 0
Deck Dist Width WeirC Skew NumUp NumDn MinLoCord MaxHiCord MaxSubmerge Is_Ogee
50,160,2.6,0, 12, 12, , , 0.95, 0, 0,0,,
       0      60     120     180   337.8   355.2   710.4  1084.8    1140    1200
    1260    1320
   575.4   576.8     579   581.8   589.5   590.6   608.7   628.4   631.2   634.2
   637.2   640.2
     525     525     525     525     525   579.2   597.5   618.3     525     525
     525     525
       0      60     120     180   337.8   355.2   710.4  1084.8    1140    1200
    1260    1320
   575.4   576.8     579   581.8   589.5   590.6   608.7   628.4   631.2   634.2
   637.2   640.2
     525     525     525     525     525   579.2   597.5   618.3     525     525
     525     525
Pier Skew, UpSta & Num, DnSta & Num=  ,400, 2 ,400, 2 , 0 , 0 , 0 ,,
       7       7
   529.2   618.3
       7       7
   529.2   618.3
Pier Skew, UpSta & Num, DnSta & Num=  ,500, 2 ,500, 2 , 0 , 0 , 0 ,,
       7       7
   529.2   618.3
       7       7
   529.2   618.3
Pier Skew, UpSta & Num, DnSta & Num=  ,600, 2 ,600, 2 , 0 , 0 , 0 ,,
       7       7
   529.2   618.3
       7       7
   529.2   618.3
Pier Skew, UpSta & Num, DnSta & Num=  ,700, 2 ,700, 2 , 0 , 0 , 0 ,,
       7       7
   529.2   618.3
       7       7
   529.2   618.3
Pier Skew, UpSta & Num, DnSta & Num=  ,800, 2 ,800, 2 , 0 , 0 , 0 ,,
       7       7
   529.2   618.3
       7       7
   529.2   618.3
Pier Skew, UpSta & Num, DnSta & Num=  ,900, 2 ,900, 2 , 0 , 0 , 0 ,,
       7       7
   529.2   618.3
       7       7
   529.2   618.3
Pier Skew, UpSta & Num, DnSta & Num=  ,1000, 2 ,1000, 2 , 0 , 0 , 0 ,,
       7       7
   529.2   618.3
       7       7
   529.2   618.3
BR Coef=-1 , 0 , 0 ,, 0 ,,,0.817,-1,,1,
WSPro=,,,, 1 ,,,, 0 ,,,, 0 ,,,,-1 ,-1 ,-1 , 0 , 0 , 0 , 0 , 0
BC Design=,, 0 ,, 0 ,,,,,,
BC HTab HWMax=580

Type RM Length L Ch R = 1 ,2731.142,347.29,230.13,241.66
XS GIS Cut Line= 3
      2061477.94        351837.6      2062617.54       351903.25
      2063832.18       351997.05
#Sta/Elev= 29
       0   575.4      60   575.8     120     578     180   581.8     240   583.8
     300   586.7   337.8   589.3   355.2   577.6  355.26   575.8     402   547.1
   425.4   545.4   472.8   535.2   520.2   534.9   567.6   534.3     615   530.3
   662.4   529.2     696     545   710.4   548.4   746.4   551.3   805.2   570.5
   895.8   593.1   901.2   592.1960.0001   586.5   996.6   598.4  1084.8   616.5
 1084.86   616.7  1103.4     630    1140   630.2    1320   639.2
#Mann= 3 , 0 , 0
       0     .05       0   337.8     .04       0   895.8      .1       0
Bank Sta=337.8,895.8
XS Rating Curve= 0
Exp/Cntr=0.3,0.1

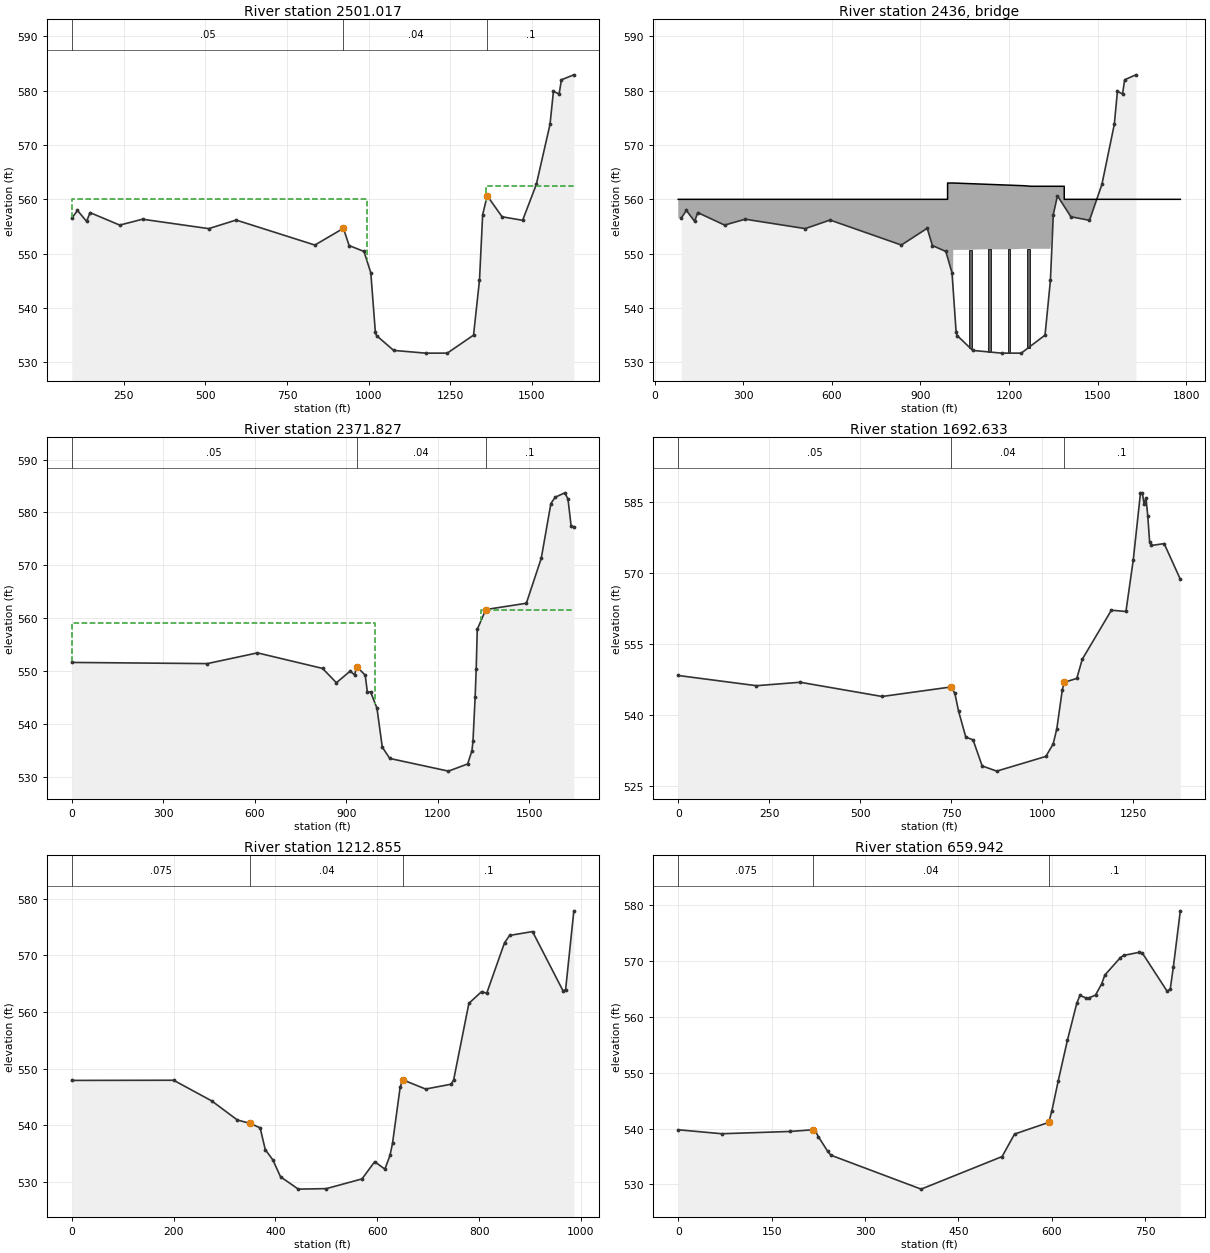
Type RM Length L Ch R = 1 ,2501.017,118.41,129.19,86.96
XS GIS Cut Line= 4
      2061688.97       352001.74      2063053.69       352072.08
      2063471.07       352114.29      2063883.77       352137.74
#Sta/Elev= 30
      90  556.52   107.5  557.95  135.51  555.94  146.01  557.56     237  555.26
     307  556.34  510.01  554.61     594  556.19   835.5  551.59  923.01  554.67
   940.5   551.5  986.01  550.41 1007.01  546.48    1021  535.51  1024.5  534.94
    1077  532.21    1175  531.71 1241.51  531.71    1322  535.02 1340.23  545.11
    1350   557.2 1364.01  560.65  1409.5  556.79 1472.51  556.14  1514.5  562.73
 1556.51  573.79    1567  579.84  1584.5  579.38  1591.5  581.99 1629.59   582.9
#Mann= 3 , 0 , 0
      90     .05       0  923.01     .04       0 1364.01      .1       0
#XS Ineff= 2 , 0
       0     995     560    1360       0   562.4
Permanent Ineff=
       F       F
Bank Sta=923.01,1364.01
XS Rating Curve= 0
Exp/Cntr=0.3,0.1

Type RM Length L Ch R = 3 ,2436    ,,,
BEGIN DESCRIPTION:
Lower Conrail Railroad Bridge
END DESCRIPTION:
Bridge Culvert-0,0,-1,-1, 0
Deck Dist Width WeirC Skew NumUp NumDn MinLoCord MaxHiCord MaxSubmerge Is_Ogee
15,100,2.6,0, 19, 19, , , 0.95, 0, 2,2,,
      80     992     992  1010.6  1011.2  1059.8  1107.8  1155.8  1203.8  1251.8
    1274    1335    1335    1348    1366    1378    1387    1387    1780
     560     560     563     563     563   562.9   562.8   562.7   562.6   562.5
   562.4   562.4   562.4   562.4   562.4   562.4   562.4     560     560
     500     500     540   538.5   550.7   550.7   550.8   550.8   550.8   550.9
   550.9   550.9   550.9   550.9     555     555     555     500     500
       0     992     992  1010.6  1011.2  1059.8  1107.8  1155.8  1203.8  1251.8
    1274    1335    1335    1348    1366    1378    1387    1387    1700
     560     560     563     563     563   562.9   562.8   562.7   562.6   562.5
   562.4   562.4   562.4   562.4   562.4   562.4   562.4     560     560
     500     500     540   538.5   550.7   550.7   550.8   550.8   550.8   550.9
   550.9   550.9   550.9     555     555     555     555     500     500
Pier Skew, UpSta & Num, DnSta & Num=  ,1070, 2 ,1070, 2 , 0 , 0 , 0 ,,
      10       7
   531.7     551
      10       7
   531.7     551
Pier Skew, UpSta & Num, DnSta & Num=  ,1135, 2 ,1135, 2 , 0 , 0 , 0 ,,
      10       7
   531.7     551
      10       7
   531.7     551
Pier Skew, UpSta & Num, DnSta & Num=  ,1200, 2 ,1200, 2 , 0 , 0 , 0 ,,
      10       7
   531.7     551
      10       7
   531.7     551
Pier Skew, UpSta & Num, DnSta & Num=  ,1265, 2 ,1265, 2 , 0 , 0 , 0 ,,
      10       7
   531.7     551
      10       7
   531.7     551
BR Coef=-1 , 0 , 0 ,, 0 ,,,0.8,-1,,1,
WSPro=,,,, 1 ,,,, 0 ,,,, 0 ,,,,-1 ,-1 ,-1 , 0 , 0 , 0 , 0 , 0
BC Design=,, 0 ,, 0 ,,,,,,
BC HTab HWMax=570

Type RM Length L Ch R = 1 ,2371.827,876.88,679.19,422.71
XS GIS Cut Line= 4
      2061670.21       352090.84      2063025.55        352156.5
      2063564.87       352194.02      2064019.77        352203.4
#Sta/Elev= 30
       0   551.6   444.5  551.38  609.01  553.41  822.51  550.47     868  547.76
  913.51  549.97   927.5  549.23   934.5  550.81   962.5   549.2  969.51  545.99
     980  546.03 1001.01  542.94 1018.51  535.57    1043  533.43  1235.5  531.03
  1298.5  532.39 1312.51  534.88    1316  536.75 1323.01     545 1326.51  550.36
    1330  557.85    1358  561.61    1491   562.8 1540.01  571.33 1571.51  581.68
  1585.5  582.86    1617   583.7  1627.5  582.54 1638.01  577.37 1646.79  577.27
#Mann= 3 , 0 , 0
       0     .05       0   934.5     .04       0    1358      .1       0
#XS Ineff= 2 , 0
       0     995     559    1341       0   561.5
Permanent Ineff=
       F       F
Bank Sta=934.5,1358
XS Rating Curve= 0
Exp/Cntr=0.3,0.1

Type RM Length L Ch R = 1 ,1692.633,576.94,479.78,449.2
XS GIS Cut Line= 3
      2063077.13       352972.51      2063714.94       352723.96
      2064240.19       352269.05
#Sta/Elev= 30
       0   548.4     215  546.24     335  546.97     560  543.96     750  545.98
     760  544.61     770  540.92     790  535.37  810.01  534.78     835  529.27
     875  528.17    1010  531.28 1030.01  533.91    1040  537.08 1055.01  545.26
 1060.01  546.93    1095  547.79    1110  551.83    1190  562.21    1230  561.94
    1250  572.76 1270.01  587.04 1275.01  587.03    1280  584.59 1285.01  585.99
    1290  582.15    1295   576.7    1300   575.9    1335   576.3 1379.39  568.76
#Mann= 3 , 0 , 0
       0     .05       0     750     .04       0 1060.01      .1       0
Bank Sta=750,1060.01
XS Rating Curve= 0
Exp/Cntr=0.3,0.1

Type RM Length L Ch R = 1 ,1212.855,526.27,552.91,604.83
XS GIS Cut Line= 2
      2063956.46       353190.59      2064617.71       352458.99
#Sta/Elev= 30
       0  547.93  200.01  547.96     275  544.31     325  540.96  350.38  540.34
  370.01  539.56  380.01  535.73     395   533.9     410  530.93     445  528.75
     500  528.84     570  530.55     595  533.59     615  532.28  625.01  534.69
     630  536.83     645  546.73     650  548.04  695.01  546.41     745  547.26
     750     548  780.01  561.53     805   563.6     815   563.3  850.01  572.22
     860  573.51     905  574.19     965  563.72     970  563.96  986.15  577.85
#Mann= 3 , 0 , 0
       0    .075       0  350.38     .04       0     650      .1       0
Bank Sta=350.38,650
XS Rating Curve= 0
Exp/Cntr=0.3,0.1

Type RM Length L Ch R = 1 ,659.942 ,259.47,659.94,675.31
XS GIS Cut Line= 2
      2064505.16       353331.28      2065091.38       352777.89
#Sta/Elev= 30
       0  539.78      70  539.07     180  539.48  216.13  539.78     220   539.6
     225  538.55     240  535.91     245  535.23     390  529.15     520  534.98
     540  539.01     595  541.11     600  543.21  610.01  548.47     625  555.87
     640  562.48     645  563.85     655  563.37     660  563.42  670.01  563.91
     680  565.94     685  567.49     710  570.62     715     571     740  571.56
     745  571.46     785  564.59     790  564.97     795  568.95  806.16  578.99
#Mann= 3 , 0 , 0
       0    .075       0  216.13     .04       0     595      .1       0
Bank Sta=216.13,595
XS Rating Curve= 0
Exp/Cntr=0.3,0.1

Chan Stop Cuts=-1